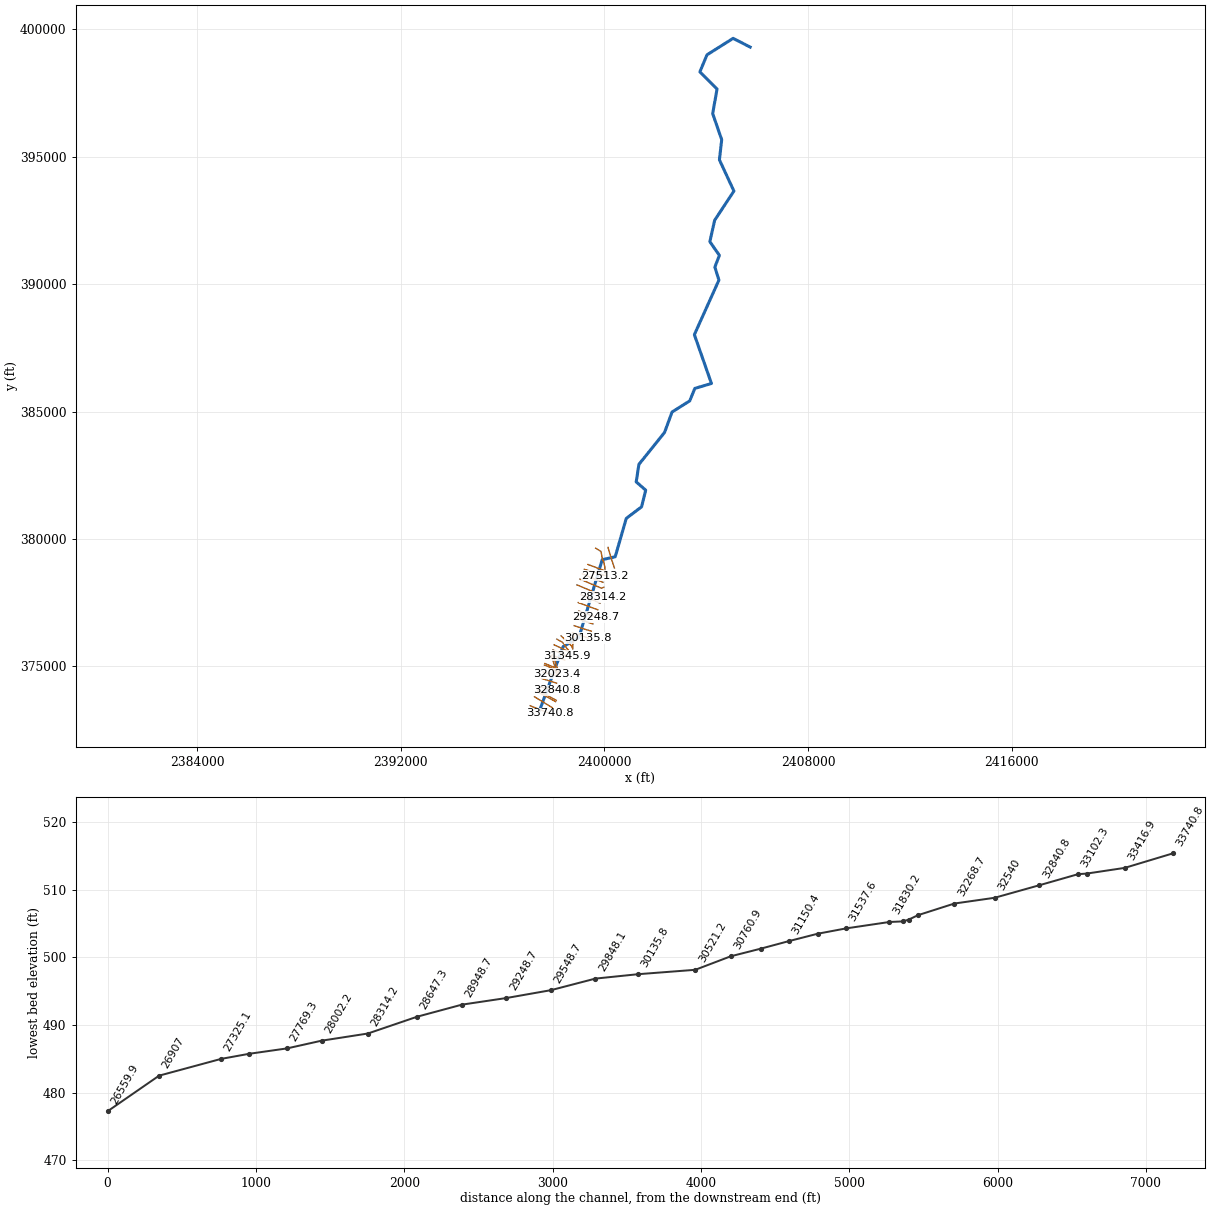
--- HARLANRUN.prj (project) ---

Proj Title=HARLANRUN
Current Plan=p01
Default Exp/Contr=0,0
English Units
Geom File=g01
Flow File=f01
Plan File=p01
BEGIN DESCRIPTION:
END DESCRIPTION:
DSS Export Rating Curves= 0
DSS Export Rating Curve Sorted= 0
DSS Export Volume Flow Curves= 0
DXF Filename=.\backup\HARLANRUN.
DXF OffsetX= 0
DXF OffsetY= 0
DXF ScaleX= 0
DXF ScaleY= 0

--- HARLANRUN.p01 (plan) ---

Plan Title=Floodplain
Program Version=4.00
Geom File=g01
Flow File=f01
K Sum by GR=0
Std Step Tol=0.01
Critical Tol=0.01
Num of Std Step Trials=20
Max Error Tol=0.3
Flow Tol Ratio=0.001
Split Flow NTrial=30
Split Flow Tol=0.02
Split Flow Ratio=0.02
Log Output Level=0
Friction Slope Method=1
Unsteady Friction Slope Method=2
Unsteady Bridges Friction Slope Method=1
Global Log Level=0
CheckData=False
Run HTab=0
Run UNet=0
Run PostProcess=0
UNET Theta=0
UNET Theta Warmup=0
UNET ZTol=0
UNET ZSATol=0
UNET MxIter=0
UNET MaxInSteps=0
UNET DtIC=0
UNET DtMin=0
UNET MaxCRTS=0
UNET WFStab=0
UNET SFStab=0
UNET WFX=0
UNET SFX=0
UNET DSS MLevel=0
UNET DZMax Abort=0
UNET Convert EG Bridges=0
UNET Use Existing IB Tables=0
UNET Froude Limit=0
UNET Froude Power=0
Write IC File=0
Echo Input=False
Echo Output=False
Write Detailed=0

--- HARLANRUN.f01 (steady flow) ---

Flow Title=NFF Regression Equation
Program Version=4.00
Number of Profiles=1
Profile Names=P100yr
River Rch & RM=HARLANRUN,Main      ,33740.8
549.4356
River Rch & RM=HARLANRUN,Main      ,33102.3
610.1316
River Rch & RM=HARLANRUN,Main      ,30967.3
669.9011
River Rch & RM=HARLANRUN,Main      ,28002.2
720.6391
River Rch & RM=HARLANRUN,Main      ,27325.1
806.1619
River Rch & RM=HARLANRUN,Main      ,23783.4
868.9041
River Rch & RM=HARLANRUN,Main      ,23159.2
1245.997
River Rch & RM=HARLANRUN,Main      ,22908.3
1252.453
River Rch & RM=HARLANRUN,Main      ,17443.8
1387.738
River Rch & RM=HARLANRUN,Main      ,17060.9
1630.624
River Rch & RM=HARLANRUN,Main      ,13503.4
1694.889
River Rch & RM=HARLANRUN,Main      ,13253.5
2620.308
River Rch & RM=HARLANRUN,Main      ,8250.7
2762.670
River Rch & RM=HARLANRUN,Main      ,2374.5
3006.470
River Rch & RM=HARLANRUN,Main      ,2096.5
3355.021
River Rch & RM=HARLANRUN,Main      ,167.4
3363.618
Boundary for River Rch & Prof#=HARLANRUN,Main      ,1
Up Type=0
Dn Type=3
Dn Slope=0.006172

--- HARLANRUN.g01 (geometry) ---

Geom Title=USGS 10m DEM
Program Version=4.10

River Reach=HARLANRUN       ,Main
Reach XY= 30
     2397465.059        373292.7      2398379.99      375771.867
     2398998.508      376125.744     2399916.678      379184.368
     2400426.747      379299.646     2400861.267      380805.679
     2401462.569      381259.238      2401624.78         381913.
     2401250.648      382239.388     2401358.894      382928.017
     2402364.624      384177.843     2402659.301      384980.192
     2403354.831       385418.56     2403553.398      385906.842
      2404206.61      386101.069     2403536.222      388016.633
     2404500.901      390157.771     2404341.547      390671.129
     2404519.498      391128.594     2404145.018      391667.674
     2404332.866      392506.199     2405090.061      393653.683
     2404520.018       394879.48     2404610.187      395668.839
      2404255.37       396694.23     2404427.896      397658.856
     2403752.982      398332.684     2404031.845      399000.002
     2405059.406      399647.789     2405728.894      399303.821

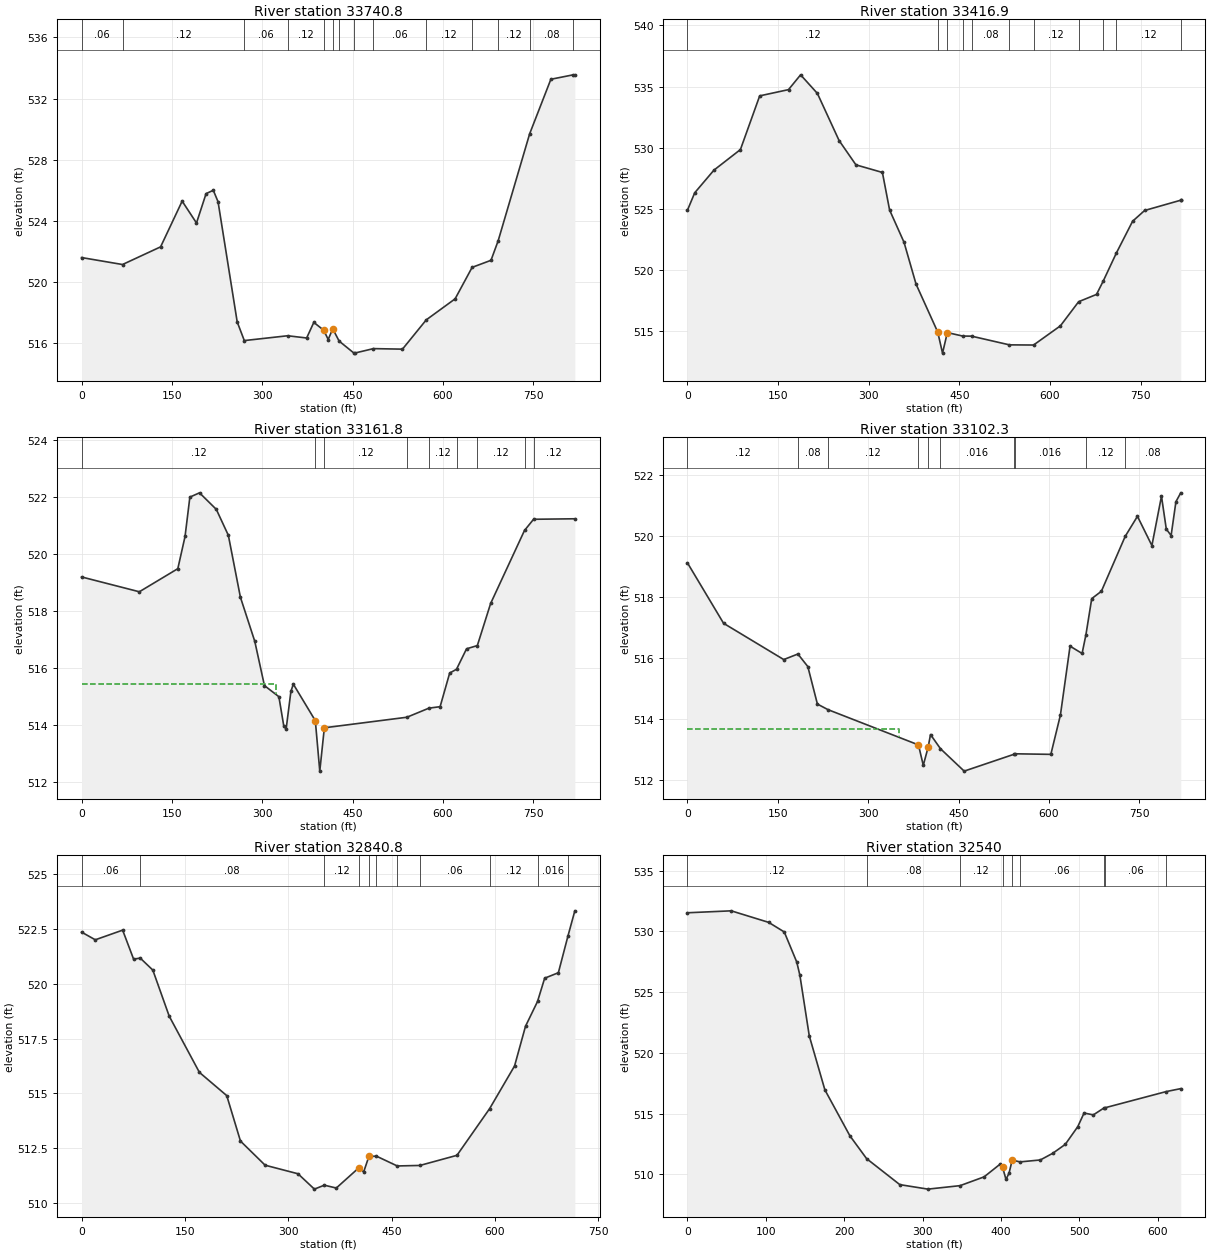
Type RM Length L Ch R = 1 ,33740.8 ,327.6,323.9,319.8
XS GIS Cut Line= 3
     2397087.476      373451.513      2397468.71       373302.01
     2397849.943      373152.506
#Sta/Elev= 30
       0   521.6   67.97521.1447   131.2   522.3     167  525.29   190.8  523.86
   206.7  525.78   218.7     526   226.6  525.25   258.4  517.39  270.18516.1704
  342.14516.4864   373.7  516.34   385.6  517.36     402  516.85   409.5  516.24
     417  516.94  427.62516.1378  452.22515.3525   453.2  515.35  484.62515.6449
   532.8  515.61   572.3517.5255   620.2   518.9  648.45520.9595   679.8  521.42
  691.78522.7074  743.97529.6931   779.2  533.26  816.26533.5505     819  533.53
#Mann= 14 ,-1 , 0
       0     .06       0   67.97     .12       0  270.18     .06       0
  342.14     .12       0     402    .045       0     417     .12       0
  427.62     .06       0  452.22     .08       0  484.62     .06       0
   572.3     .12       0  648.45    .016       0  691.78     .12       0
  743.97     .08       0  816.26     .12       0
Bank Sta=402,417
XS Rating Curve= 0 ,0
Exp/Cntr=0.3,0.1

Type RM Length L Ch R = 1 ,33416.9 ,254.3,255.1,256.1
XS GIS Cut Line= 2
     2397254.248      373804.919     2397950.803        373379.2
#Sta/Elev= 30
       0   524.9      12  526.32    43.8  528.17    87.6  529.85   119.5  534.24
   167.2  534.75   187.2  535.96     215  534.44   250.9  530.59   278.8   528.6
   322.6  527.98   334.5  524.91   358.4  522.27   378.3  518.85   414.2  514.93
   422.1  513.21   430.1  514.89  455.41514.6059  470.07514.5983  532.85513.8856
   572.8 513.872   617.2  515.44   647.4517.4133     677  518.01  688.15519.1063
  709.78 521.388   736.7  523.99   756.6  524.87     816 525.705   816.4  525.71
#Mann= 11 ,-1 , 0
       0     .12       0   414.2    .045       0   430.1     .12       0
  455.41     .06       0  470.07     .08       0  532.85     .06       0
   572.8     .12       0   647.4    .016       0  688.15     .06       0
  709.78     .12       0     816     .06       0
Bank Sta=414.2,430.1
XS Rating Curve= 0 ,0
Exp/Cntr=0.3,0.1

Type RM Length L Ch R = 1 ,33161.8 ,59.5,59.5,59.5
XS GIS Cut Line= 2
     2397367.002      374006.688     2398084.963      373612.616
#Sta/Elev= 30
       0  519.18    95.9  518.66   159.8  519.47   171.8   520.6   179.8  521.98
   195.8  522.13   223.7  521.55   243.7  520.64   263.7  518.47   287.6  516.92
   303.6  515.37   327.6  514.98   335.6  513.97   339.6  513.84   347.6  515.17
   351.6  515.42   388.1  514.14   395.5  512.37   403.1  513.89  540.19  514.26
  576.73514.5786   595.3  514.63   611.2  515.81  622.52515.9419   639.2  516.66
   657.1516.7725   679.2  518.25  735.42520.8104  750.49521.2024     819  521.22
#Mann= 9 ,-1 , 0
       0     .12       0   388.1    .045       0   403.1     .12       0
  540.19     .08       0  576.73     .12       0  622.52    .016       0
   657.1     .12       0  735.42     .08       0  750.49     .12       0
#XS Ineff= 2 , 0
          322.21  515.41
Permanent Ineff=
       F       F
Bank Sta=388.1,403.1
XS Rating Curve= 0 ,0
Exp/Cntr=0.3,0.1

Type RM Length L Ch R = 1 ,33102.3 ,255,261.6,267.9
XS GIS Cut Line= 2
     2397390.439      374061.376       2398108.4      373667.304
#Sta/Elev= 30
       0  519.11    59.9  517.13   159.8  515.94  183.31516.1224   199.8  515.71
   215.7  514.48  233.34514.2964   383.5  513.14   391.5  512.47   399.5  513.06
   403.5  513.48  420.02513.0157   459.4  512.28  542.44 512.835  543.56512.8487
   603.3  512.83   619.2  514.12   635.2  516.38   655.2  516.14  661.54516.7525
   671.2  517.94   687.2  518.18  726.79 519.983   747.1  520.64   771.1  519.68
     787   521.3     795  520.22     803  520.01     811  521.12     819  521.41
#Mann= 10 ,-1 , 0
       0     .12       0  183.31     .08       0  233.34     .12       0
   383.5    .045       0   399.5     .12       0  420.02    .016       0
  542.44     .08       0  543.56    .016       0  661.54     .12       0
  726.79     .08       0
#XS Ineff= 2 , 0
          350.45  513.67
Permanent Ineff=
       F       F
Bank Sta=383.5,399.5
XS Rating Curve= 0 ,0
Exp/Cntr=0.3,0.1

Type RM Length L Ch R = 1 ,32840.8 ,302.7,300.8,299
XS GIS Cut Line= 3
      2397423.42      374204.703     2397823.596      374117.816
     2398122.547      374050.605
#Sta/Elev= 30
       0  522.35    19.9     522    59.6  522.44    75.5  521.12   85.16521.1658
   103.4  520.62   127.2  518.52     171  515.96   210.7   514.9   230.6  512.83
   266.4  511.73   314.1  511.34   337.9  510.64  352.29510.8194   369.7  510.69
     402   511.6   409.5  511.43     417  512.13  428.01512.1417  458.15511.6956
  491.03 511.719   544.8  512.18  592.27514.3094   628.4  516.25   644.3  518.06
  661.74519.1895   672.1  520.25     692   520.5  706.04522.1883   715.9  523.32
#Mann= 11 ,-1 , 0
       0     .06       0   85.16     .08       0  352.29     .12       0
     402    .045       0     417     .12       0  428.01     .06       0
  458.15     .08       0  491.03     .06       0  592.27     .12       0
  661.74    .016       0  706.04     .06       0
Bank Sta=402,417
XS Rating Curve= 0 ,0
Exp/Cntr=0.3,0.1

Type RM Length L Ch R = 1 ,32540   ,270.6,271.2,271.8
XS GIS Cut Line= 2
     2397523.585      374524.923     2398125.152      374339.667
#Sta/Elev= 30
       0  531.53    55.8  531.69   103.6  530.74   123.5  529.95   139.4  527.48
   143.4  526.39   155.4   521.4   175.3  516.96   207.2  513.18  228.56511.2982
   270.9  509.16   306.8  508.79  347.85509.0769   378.5   509.8   398.4  510.82
     402   510.6   406.4  509.59   410.3   510.1   414.3  511.17  424.48511.0319
   450.2  511.19   466.1  511.74     482  512.47     498  513.93     506  515.05
   517.9   514.9  531.27 515.462  532.74515.4841  610.83516.8166   629.4  517.06
#Mann= 9 ,-1 , 0
       0     .12       0  228.56     .08       0  347.85     .12       0
     402    .045       0   414.3     .12       0  424.48     .06       0
  531.27     .12       0  532.74     .06       0  610.83     .12       0
Bank Sta=402,414.3
XS Rating Curve= 0 ,0
Exp/Cntr=0.3,0.1

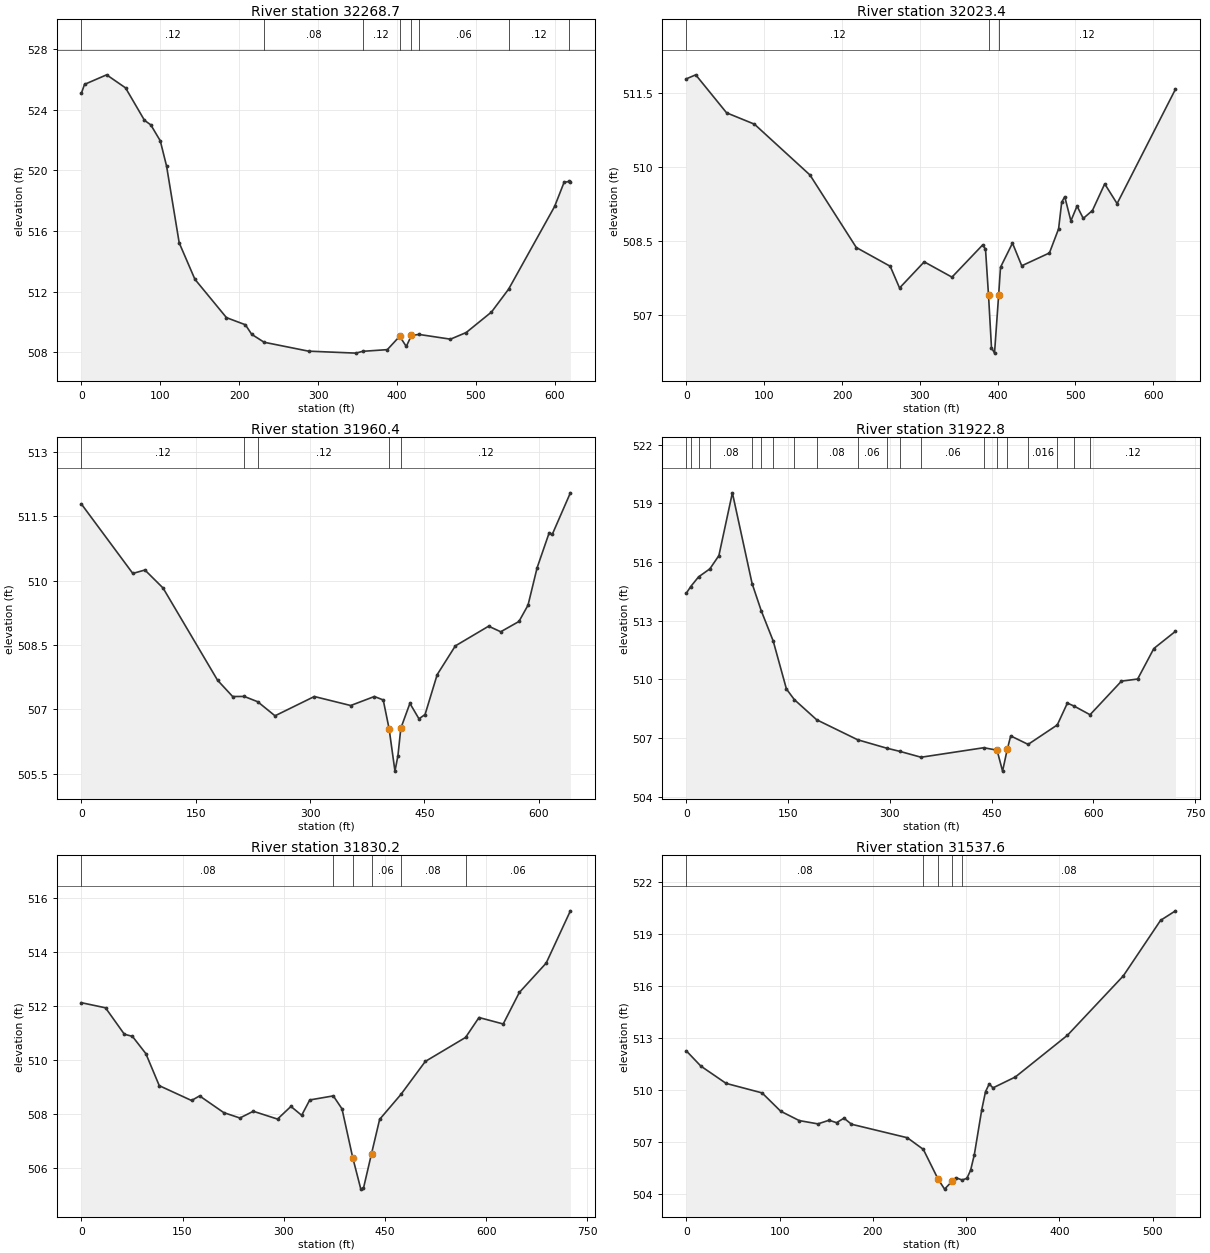
Type RM Length L Ch R = 1 ,32268.7 ,253.5,245.3,171.9
XS GIS Cut Line= 2
     2397601.028      374772.855     2398198.198      374607.065
#Sta/Elev= 30
       0  525.07       4  525.66      32  526.29      56  525.43      80  523.29
      88  522.99     100  521.94     108  520.27     124  515.21   143.9  512.81
   183.9  510.28   207.9  509.81   215.9  509.18  231.59508.6577   287.9  508.07
   347.9  507.94  356.48508.0587   387.8  508.17   403.4  509.05   411.8  508.38
   418.4  509.11  427.99509.1719   467.8  508.86   487.8   509.3   519.8  510.65
   541.5512.1577   599.8  517.61   611.8   519.2  618.36519.2608   619.8  519.25
#Mann= 8 ,-1 , 0
       0     .12       0  231.59     .08       0  356.48     .12       0
   403.4    .045       0   418.4     .12       0  427.99     .06       0
   541.5     .12       0  618.36    .016       0
Bank Sta=403.4,418.4
XS Rating Curve= 0 ,0
Exp/Cntr=0.3,0.1

Type RM Length L Ch R = 1 ,32023.4 ,61.8,63,122.8
XS GIS Cut Line= 4
     2397644.483      375051.069     2397983.025      374913.916
     2398028.164      374884.402     2398129.379      374700.867
#Sta/Elev= 30
       0  511.78    11.9  511.86    51.6  511.09    87.4  510.86   158.8  509.83
   218.4  508.36     262  507.98     274  507.54   305.7  508.07   341.4  507.76
   380.7  508.41   384.5  508.33   388.4  507.39   392.2  506.33   396.1  506.22
  401.38  507.39   403.8  507.96   419.2  508.45   431.1  507.99   466.7  508.25
   478.5  508.74   482.5  509.28   486.4  509.39   494.3   508.9   502.2   509.2
   510.2  508.95     522  509.11   537.8  509.65   553.7  509.25   628.8  511.57
#Mann= 3 ,-1 , 0
       0     .12       0   388.4    .045       0  401.38     .12       0
Bank Sta=388.4,401.38
XS Rating Curve= 0 ,0
Exp/Cntr=0.3,0.1

Type RM Length L Ch R = 1 ,31960.4 ,55.9,37.6,22.7
XS GIS Cut Line= 4
       2397667.4      375108.708     2398005.941      374971.555
      2398051.08      374942.041     2398128.685      374733.505
#Sta/Elev= 30
       0  511.79    67.5  510.17    83.4  510.25   107.2  509.83   178.7  507.68
   198.5   507.3  213.76507.3016  231.35507.1785   254.1  506.85   305.7   507.3
   353.4  507.09   384.5   507.3   396.1  507.22   403.8  506.55   411.5  505.56
   415.4  505.92   419.2  506.56   431.1  507.14     443  506.78     451  506.88
   466.9  507.81   490.7  508.48   534.4  508.94   550.3  508.81   574.2  509.05
   586.1  509.43     598   510.3   613.9  511.12   617.9  511.08   641.7  512.05
#Mann= 5 ,-1 , 0
       0     .12       0  213.76     .06       0  231.35     .12       0
   403.8    .045       0   419.2     .12       0
Bank Sta=403.8,419.2
XS Rating Curve= 0 ,0
Exp/Cntr=0.3,0.1

Type RM Length L Ch R = 1 ,31922.8 ,97.6,92.5,90.4
XS GIS Cut Line= 2
     2397916.818      375425.605     2398135.803      374738.569
#Sta/Elev= 30
       0  514.41    6.33514.7398   17.85515.2329   34.48515.6419    47.8  516.32
    67.7  519.53   96.77514.8913  110.22513.5042  127.91511.9526   147.4   509.5
  159.06508.9561  191.99507.9263  252.49506.9027  294.97 506.477  314.79506.3091
  345.93  506.01  438.44506.4966     458  506.37   466.1   505.3     473  506.41
   478.1   507.1  503.82506.6673  546.79 507.662   561.7  508.78  572.09508.6165
   595.1508.1837   641.4   509.9   665.3  510.01   689.2  511.57   721.1  512.45
#Mann= 20 ,-1 , 0
       0     .08       0    6.33     .06       0   17.85    .016       0
   34.48     .08       0   96.77     .06       0  110.22    .016       0
  127.91     .08       0  159.06     .06       0  191.99     .08       0
  252.49     .06       0  294.97    .016       0  314.79     .08       0
  345.93     .06       0  438.44     .12       0     458    .045       0
     473     .12       0  503.82    .016       0  546.79     .12       0
  572.09     .08       0   595.1     .12       0
Bank Sta=458,473
XS Rating Curve= 0 ,0
Exp/Cntr=0.3,0.1

Type RM Length L Ch R = 1 ,31830.2 ,264.6,292.6,320.6
XS GIS Cut Line= 2
     2397981.922      375459.459     2398200.039      374768.083
#Sta/Elev= 30
       0  512.13    35.8  511.94    63.7  510.96    75.7  510.88    95.6  510.24
   115.5  509.05   163.3   508.5   175.3  508.67   211.1  508.05     235  507.85
   254.9   508.1   290.8  507.81   310.7  508.28   326.6  507.95   338.6  508.52
  373.51508.6711   386.4  508.19   402.3  506.38   414.3  505.21   418.2  505.24
   430.2  506.53   442.2   507.8  473.71 508.724   509.9  509.95  569.58510.8401
   589.5  511.58   625.4  511.34   649.3  512.51   689.1   513.6     725  515.54
#Mann= 6 ,-1 , 0
       0     .08       0  373.51     .06       0   402.3    .045       0
   430.2     .06       0  473.71     .08       0  569.58     .06       0
Bank Sta=402.3,430.2
XS Rating Curve= 0 ,0
Exp/Cntr=0.3,0.1

Type RM Length L Ch R = 1 ,31537.6 ,192.8,191.7,190.7
XS GIS Cut Line= 3
     2397997.547      375477.688     2398029.112      375402.982
      2398442.86      375243.313
#Sta/Elev= 30
       0  512.24    15.4  511.37    42.5  510.37    81.1  509.82   101.1  508.76
     121  508.22     141  508.03     153  508.24     161   508.1     169  508.36
     177  508.01   236.9  507.23   254.1 506.556     270  504.83   276.9  504.26
     285  504.72   288.9  504.92  295.65504.7906   300.8  504.88   304.8  505.35
   308.8  506.25   316.8  508.86   320.8  509.89   324.8  510.34   328.8  510.11
   352.8  510.74   408.7  513.15   468.6  516.58   508.6  519.79   524.6  520.34
#Mann= 5 ,-1 , 0
       0     .08       0   254.1     .12       0     270    .045       0
     285     .12       0  295.65     .08       0
Bank Sta=270,285
XS Rating Curve= 0 ,0
Exp/Cntr=0.3,0.1

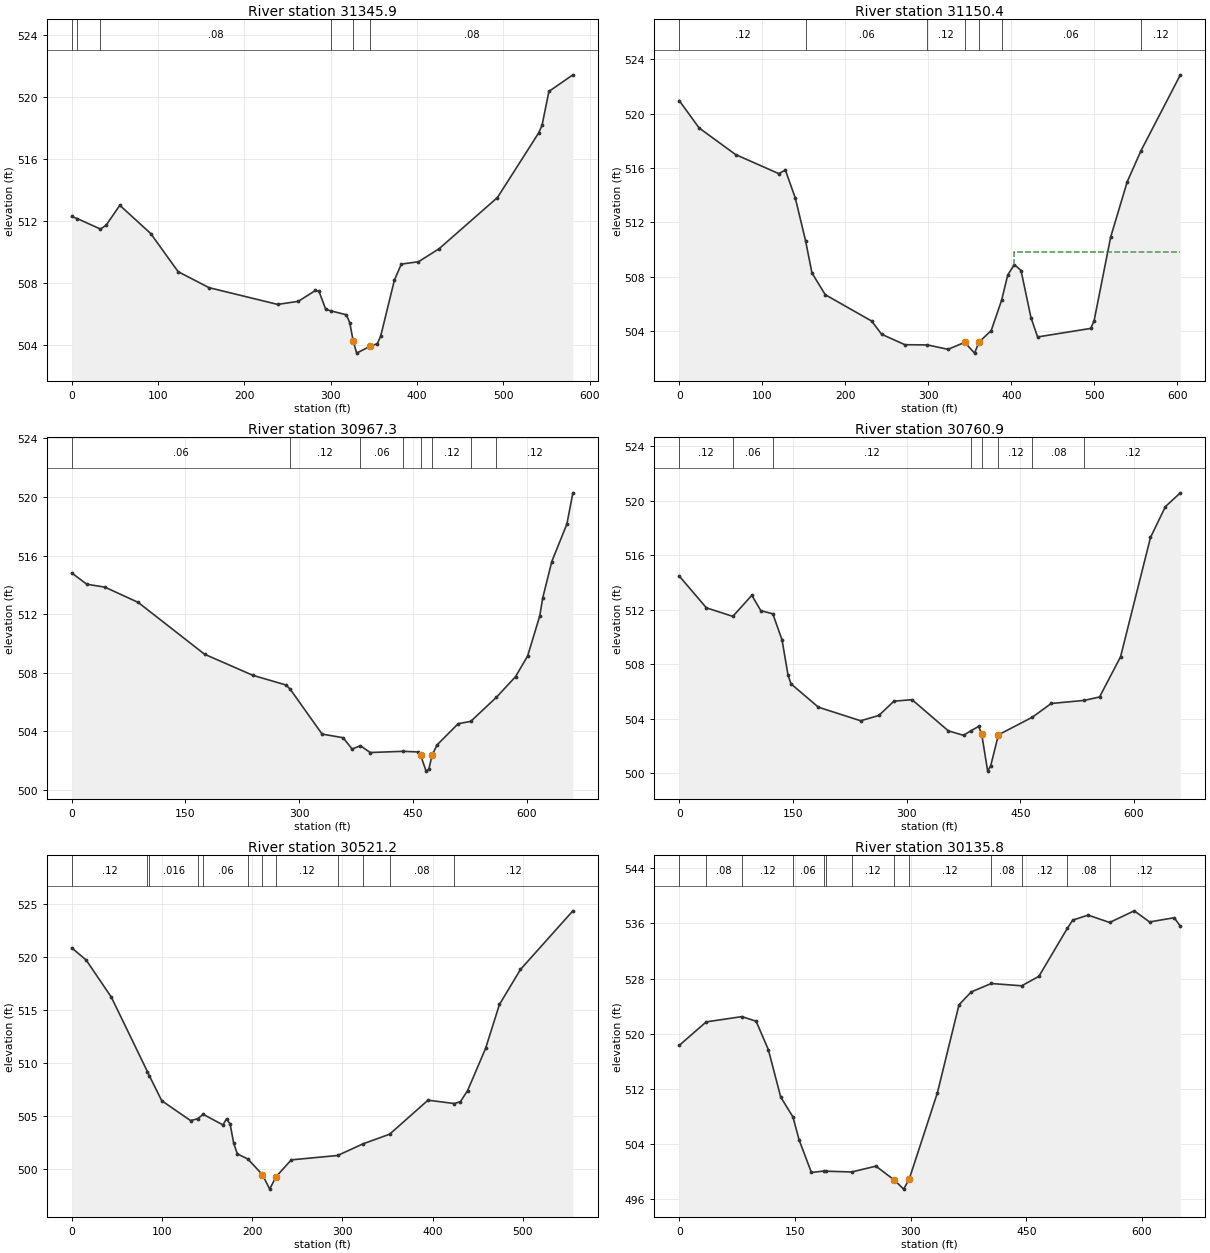
Type RM Length L Ch R = 1 ,31345.9 ,195.9,195.5,195.2
XS GIS Cut Line= 2
     2397979.318      375644.355     2398510.568       375409.98
#Sta/Elev= 30
       0  512.28    6.38512.1445   33.31511.4676    39.8  511.71    55.7     513
    91.5  511.18   123.3  508.72   159.1  507.69   238.6  506.61   262.5  506.81
   282.4  507.51   286.4  507.46   294.3  506.29  300.11506.1972   318.2  505.94
   322.1  505.43   326.1  504.25   330.1  503.47     346  503.92     354  504.08
   357.9  504.56   373.8  508.17   381.8  509.21   401.7  509.36   425.6   510.2
   493.2   513.5   540.9  517.66   544.9  518.16   552.8  520.34   580.6  521.41
#Mann= 6 ,-1 , 0
       0     .06       0    6.38     .12       0   33.31     .08       0
  300.11     .12       0   326.1    .045       0     346     .08       0
Bank Sta=326.1,346
XS Rating Curve= 0 ,0
Exp/Cntr=0.3,0.1

Type RM Length L Ch R = 1 ,31150.4 ,201.3,183.1,166.4
XS GIS Cut Line= 2
     2398026.428      375842.736     2398575.039         375591.
#Sta/Elev= 30
       0  520.96      24  518.94      68  516.98   119.9  515.58   127.9  515.84
   139.9  513.77   152.2510.6418   159.9  508.27   175.9  506.67   231.8  504.73
   243.8  503.76   271.8  502.99  299.05502.9731   323.8  502.65   343.8  503.16
   355.8  502.37  360.88  503.17   375.8  504.03  388.33506.2684   395.7  508.12
   403.7  508.89   411.7  508.45   423.7  504.98   431.7  503.56   495.7  504.19
   499.7  504.75   519.7  510.92   539.6  514.98  556.12517.2585   603.6  522.85
#Mann= 7 ,-1 , 0
       0     .12       0   152.2     .06       0  299.05     .12       0
   343.8    .045       0  360.88     .12       0  388.33     .06       0
  556.12     .12       0
#XS Ineff= 2 , 0
                          403.47          509.82
Permanent Ineff=
       F       F
Bank Sta=343.8,360.88
XS Rating Curve= 0 ,0
Exp/Cntr=0.3,0.1

Type RM Length L Ch R = 1 ,30967.3 ,196.3,206.4,213.8
XS GIS Cut Line= 5
     2398130.594       376068.43     2398356.289      375941.694
     2398479.318      375786.542     2398477.582      375765.709
     2398597.608      375627.458
#Sta/Elev= 30
       0  514.82    19.9  514.05    43.8  513.85    87.6  512.81   175.2  509.27
   238.9  507.83   282.6  507.17  288.19506.8758   330.1  503.82   357.8  503.57
   369.7   502.8  380.69503.0259   393.5  502.56  436.86502.6425   456.8   502.6
   460.1  502.36   467.3  501.29   470.8  501.41   475.1  502.37   481.7  503.08
   509.6  504.53  526.14504.6872  559.91506.3287   585.2  507.74   601.1  509.15
   617.1  511.88     621  513.11     633   515.6   652.9  518.16   660.8  520.29
#Mann= 8 ,-1 , 0
       0     .06       0  288.19     .12       0  380.69     .06       0
  436.86     .12       0   460.1    .045       0   475.1     .12       0
  526.14     .06       0  559.91     .12       0
Bank Sta=460.1,475.1
XS Rating Curve= 0 ,0
Exp/Cntr=0.3,0.1

Type RM Length L Ch R = 1 ,30760.9 ,259.8,239.7,220
XS GIS Cut Line= 3
     2398302.213      376193.087     2398705.247      375806.277
     2398746.914      375712.527
#Sta/Elev= 30
       0  514.48    35.9  512.14   70.74  511.51    95.8  513.06   107.7  511.93
   123.5511.7005   135.7  509.78   143.6  507.19   147.6  506.55   183.6  504.84
   239.4  503.84   263.4  504.23   283.3  505.28   307.2  505.39   355.1   503.1
   375.1  502.77  385.34503.1244     395  503.42     399  502.89     407  500.14
     411  500.54   421.2  502.81  465.88504.1005   490.8  505.11  534.68505.3395
   554.6  505.59   582.3  508.54   621.8  517.31   641.5  519.58   661.2  520.59
#Mann= 8 ,-1 , 0
       0     .12       0   70.74     .06       0   123.5     .12       0
  385.34    .016       0     399    .045       0   421.2     .12       0
  465.88     .08       0  534.68     .12       0
Bank Sta=399,421.2
XS Rating Curve= 0 ,0
Exp/Cntr=0.3,0.1

Type RM Length L Ch R = 1 ,30521.2 ,356,385.5,411.9
XS GIS Cut Line= 3
     2398798.997      376231.625     2398759.066        375778.5
      2398757.33      375677.805
#Sta/Elev= 30
       0   520.9      16  519.75    43.9  516.25   83.99509.2148   86.14508.8171
    99.8  506.48   131.7  504.61  139.61504.7737  145.73505.1952   167.6   504.2
   171.6  504.77   175.6  504.28   179.6  502.46   183.6  501.47  195.26500.9802
   211.4  499.51   219.5  498.14   226.4   499.3   243.4   500.9  294.76501.3133
  322.84502.4074  352.43503.3199     395  506.53  424.18506.2141   430.9  506.39
   438.9  507.44   458.8  511.41   474.2  515.56   497.5  518.86   555.6  524.39
#Mann= 12 ,-1 , 0
       0     .12       0   83.99     .06       0   86.14    .016       0
  139.61     .12       0  145.73     .06       0  195.26     .12       0
   211.4    .045       0   226.4     .12       0  294.76     .08       0
  322.84    .016       0  352.43     .08       0  424.18     .12       0
Bank Sta=211.4,226.4
XS Rating Curve= 0 ,0
Exp/Cntr=0.3,0.1

Type RM Length L Ch R = 1 ,30135.8 ,287.7,287.7,287.8
XS GIS Cut Line= 2
     2398747.547       376316.23     2399364.735      376113.105
#Sta/Elev= 30
       0  518.31   35.01521.7177   81.32522.4838    99.7  521.82   115.6   517.7
   131.6  510.84  147.49507.9424   155.5  504.62   171.4   499.9  187.28500.1064
  190.31500.0876  223.68499.9784   255.1  500.82     279   498.8     291  497.49
   298.3  498.96   334.8  511.45   362.8   524.2   378.7  526.06  404.53527.2817
  444.04526.9485   466.4  528.32  503.23535.2727   510.2  536.46   530.2  537.19
  558.14  536.12     590  537.81   609.9   536.2   641.8  536.81   649.8  535.59
#Mann= 13 ,-1 , 0
       0     .12       0   35.01     .08       0   81.32     .12       0
  147.49     .06       0  187.28     .08       0  190.31     .06       0
  223.68     .12       0     279    .045       0   298.3     .12       0
  404.53     .08       0  444.04     .12       0  503.23     .08       0
  558.14     .12       0
Bank Sta=279,298.3
XS Rating Curve= 0 ,0
Exp/Cntr=0.3,0.1

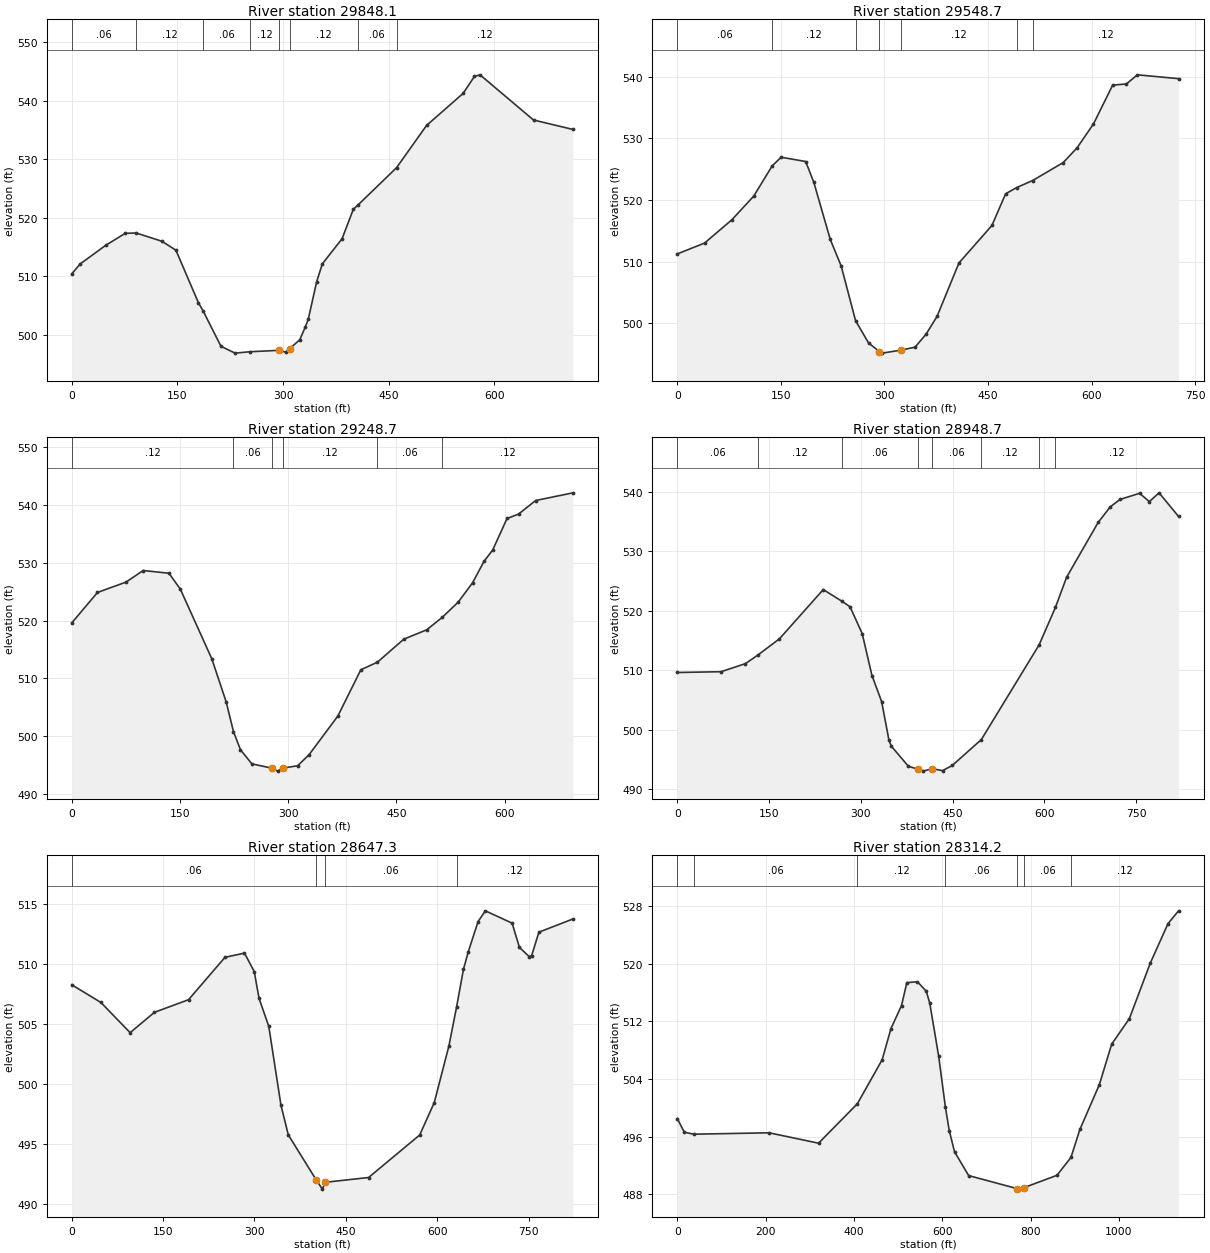
Type RM Length L Ch R = 1 ,29848.1 ,299.5,299.4,299.1
XS GIS Cut Line= 2
     2398812.652      376594.876     2399489.464      376375.845
#Sta/Elev= 30
       0  510.37      12  512.08      48  515.24    75.9  517.31   91.42517.3656
   127.9  515.96   147.9  514.42   179.8  505.45   186.2 504.118   211.8  498.01
   231.8  496.84  252.65497.0736   294.5  497.32   303.7     497   309.5  497.61
   323.7  499.14   331.7  501.36   335.7  502.63   347.7  509.07   355.7   512.1
   383.7  516.38   399.6   521.4  406.26522.1462  461.06528.5308   503.6  535.74
   555.5  541.22   571.5  544.11   579.5  544.39   655.4  536.67   711.4  535.06
#Mann= 8 ,-1 , 0
       0     .06       0   91.42     .12       0   186.2     .06       0
  252.65     .12       0   294.5    .045       0   309.5     .12       0
  406.26     .06       0  461.06     .12       0
Bank Sta=294.5,309.5
XS Rating Curve= 0 ,0
Exp/Cntr=0.3,0.1

Type RM Length L Ch R = 1 ,29548.7 ,300.3,300,299.3
XS GIS Cut Line= 3
     2398859.469      376893.429     2399159.958      376793.931
     2399548.013       376663.15
#Sta/Elev= 30
       0  511.24    39.6  513.01    79.1  516.79   110.8  520.64  137.46 525.543
   150.4  526.95     186  526.25   197.8  522.86   221.6  513.59   237.4  509.28
  258.24500.4013     277  496.79   292.8  495.38   296.8  495.13     324  495.62
   344.4   496.1   360.3   498.2   376.2  501.08     408  509.78   455.7  515.86
   475.6  521.01  491.59522.0214  514.55523.1525     559  526.08   578.9  528.45
   602.8  532.35   630.6  538.65   650.5  538.85   666.4  540.33     726  539.71
#Mann= 7 ,-1 , 0
       0     .06       0  137.46     .12       0  258.24     .06       0
   292.8    .045       0     324     .12       0  491.59     .06       0
  514.55     .12       0
Bank Sta=292.8,324
XS Rating Curve= 0 ,0
Exp/Cntr=0.3,0.1

Type RM Length L Ch R = 1 ,29248.7 ,300.4,300,300
XS GIS Cut Line= 3
     2398989.677      377171.207     2399259.069      377077.021
      2399643.12      376935.095
#Sta/Elev= 30
       0  519.61    35.7  524.88    75.3  526.68    99.1  528.68   134.8  528.21
   150.6  525.44   194.2   513.4     214  505.98  224.22500.8127   233.9  497.66
   249.7  495.23   277.9  494.47   285.4  493.97   292.9   494.5   313.2   494.9
   329.1  496.83   368.9   503.5   400.7   511.5  423.72512.8186   460.3   516.8
   492.1  518.42  513.42520.5565   535.8  523.22   555.7  526.57   571.6  530.29
   583.5  532.22   603.4  537.68   619.3  538.44   643.1  540.79   694.8  542.12
#Mann= 6 ,-1 , 0
       0     .12       0  224.22     .06       0   277.9    .045       0
   292.9     .12       0  423.72     .06       0  513.42     .12       0
Bank Sta=277.9,292.9
XS Rating Curve= 0 ,0
Exp/Cntr=0.3,0.1

Type RM Length L Ch R = 1 ,28948.7 ,302.9,301.4,299.9
XS GIS Cut Line= 3
     2398976.513       377500.66     2399360.815       377359.23
     2399745.117        377217.8
#Sta/Elev= 30
       0  509.61    71.6  509.74   111.3   511.1  131.33512.5194     167  515.29
   238.5  523.58  269.06521.6105   282.3  520.68   302.2  516.15   318.1   509.1
     334  504.68   345.9  498.18   349.9  497.17   377.7   493.8   393.6  493.31
   401.6  492.99     417   493.4   433.4  493.07   449.3  493.94   496.9498.3182
  591.23514.2643  617.86520.5654   636.1  525.65   687.8  534.91   707.7  537.54
   723.6  538.77   755.4   539.8   771.3   538.4   787.2  539.88     819  535.91
#Mann= 8 ,-1 , 0
       0     .06       0  131.33     .12       0  269.06     .06       0
   393.6    .045       0     417     .06       0   496.9     .12       0
  591.23     .06       0  617.86     .12       0
Bank Sta=393.6,417
XS Rating Curve= 0 ,0
Exp/Cntr=0.3,0.1

Type RM Length L Ch R = 1 ,28647.3 ,331.6,333.1,334.1
XS GIS Cut Line= 2
     2399077.446      377813.302     2399828.565      377477.466
#Sta/Elev= 30
       0  508.27    47.9  506.79    95.9  504.27   135.8  505.97   191.7  507.02
   251.6  510.56   283.6  510.91   299.6  509.37   307.5  507.13   323.5  504.79
   343.5   498.2   355.5  495.74   401.2  491.99   411.4  491.21   416.2  491.78
   487.3  492.18   571.2  495.73   595.1  498.43   619.1  503.15  631.68506.3922
     643  509.55     651  511.03     667  513.54     679  514.44   722.9  513.41
   734.9  511.39   750.9  510.62   754.9  510.69   766.9  512.66   822.8  513.76
#Mann= 4 ,-1 , 0
       0     .06       0   401.2    .045       0   416.2     .06       0
  631.68     .12       0
Bank Sta=401.2,416.2
XS Rating Curve= 0 ,0
Exp/Cntr=0.3,0.1

Type RM Length L Ch R = 1 ,28314.2 ,313.1,312,310.9
XS GIS Cut Line= 3
     2398922.244      378197.089      2399851.08      377806.277
     2399944.379      377719.659
#Sta/Elev= 30
       0  498.52      16  496.62   37.58496.3481   207.9  496.54   319.9   495.1
  407.78500.5704   463.9  506.68   483.9  511.02   507.8  514.21   519.8  517.39
   543.8  517.51   563.8   516.2   571.8  514.52   591.8  507.21  607.22500.0699
   615.8  496.86   627.8  493.91   659.8   490.6   770.2  488.78   775.8  488.72
   785.2  488.93   859.8  490.64  891.44493.1208   911.7  497.01   955.7  503.22
   983.7  508.86  1023.6  512.38  1071.4  520.15  1111.1  525.57    1135  527.36
#Mann= 7 ,-1 , 0
       0     .12       0   37.58     .06       0  407.78     .12       0
  607.22     .06       0   770.2    .045       0   785.2     .06       0
  891.44     .12       0
Bank Sta=770.2,785.2
XS Rating Curve= 0 ,0
Exp/Cntr=0.3,0.1

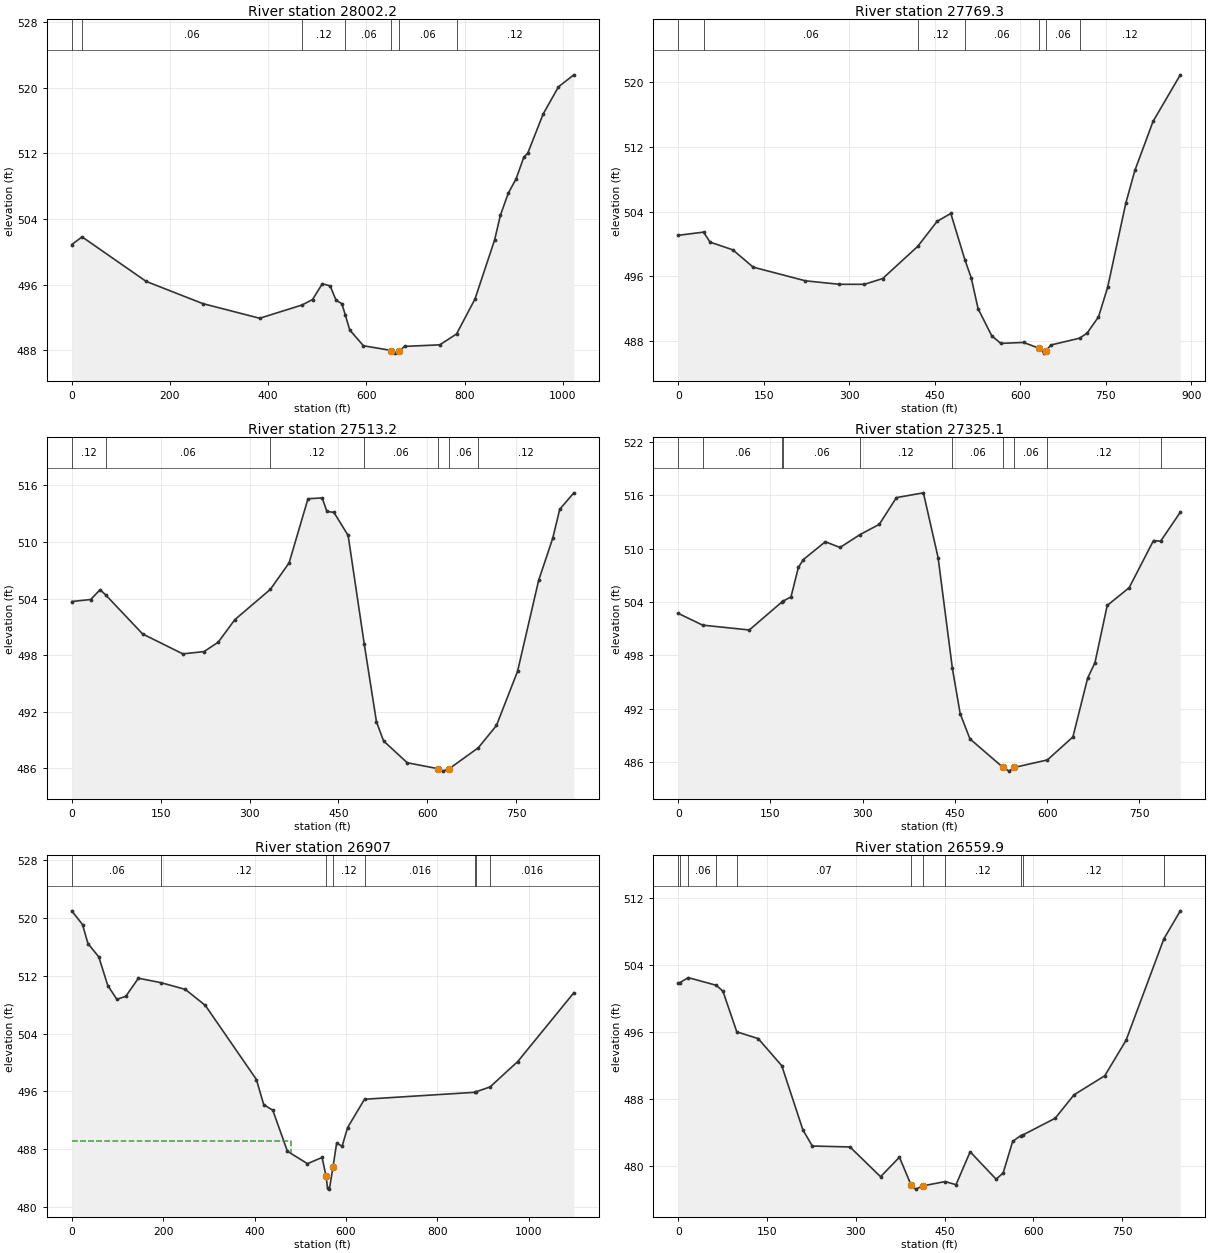
Type RM Length L Ch R = 1 ,28002.2 ,232.2,232.9,233.6
XS GIS Cut Line= 3
     2399037.261      378422.784      2399882.33      378066.694
     2399981.271      378103.773
#Sta/Elev= 30
       0  500.89   21.02501.8248   151.5   496.4   267.1  493.69   382.8  491.91
  468.99493.5228   490.4  494.19   510.4  496.12   526.3  495.85   538.3  494.11
   550.2  493.68  557.23492.3013   566.2  490.48   594.1  488.56   651.2  487.98
   657.9  487.66   666.2  487.87   677.8  488.48   749.6  488.67  783.72489.9922
   821.3  494.25   861.2  501.43   873.2  504.48   889.1  507.14   905.1   508.9
   920.9  511.55   928.8  512.02   960.1  516.79   991.4  520.11  1022.7  521.57
#Mann= 7 ,-1 , 0
       0     .12       0   21.02     .06       0  468.99     .12       0
  557.23     .06       0   651.2    .045       0   666.2     .06       0
  783.72     .12       0
Bank Sta=651.2,666.2
XS Rating Curve= 0 ,0
Exp/Cntr=0.3,0.1

Type RM Length L Ch R = 1 ,27769.3 ,254.4,256.1,257.9
XS GIS Cut Line= 3
     2399134.066      378632.666     2399550.733      378452.111
     2399948.719      378299.086
#Sta/Elev= 30
       0  501.07   44.46501.4656    55.8  500.23    95.6  499.28   131.4  497.14
   223.1  495.45   282.8  495.02   326.6  495.02   358.5  495.73  419.86499.6985
   454.1   502.8     478  503.77  502.63498.0666   513.9   495.8   525.8  492.02
   549.7  488.67   565.7  487.72   605.5  487.84   633.4  487.11   641.4  486.52
   645.4  486.83   653.4  487.52  703.97488.3669   717.1     489     737  490.99
     753  494.63   784.9  505.04   800.8  509.08   832.7  515.14   880.5  520.89
#Mann= 7 ,-1 , 0
       0     .12       0   44.46     .06       0  419.86     .12       0
  502.63     .06       0   633.4    .045       0   645.4     .06       0
  703.97     .12       0
Bank Sta=633.4,645.4
XS Rating Curve= 0 ,0
Exp/Cntr=0.3,0.1

Type RM Length L Ch R = 1 ,27513.2 ,189.6,188.1,186.4
XS GIS Cut Line= 3
     2399215.664      378806.277     2399803.053      378627.789
     2400026.844      378561.672
#Sta/Elev= 30
       0   503.7    31.9  503.91    47.8  504.95   57.74504.3669   119.6  500.26
   187.4  498.15   223.2  498.39   247.2  499.39   275.1  501.77  335.17504.9902
   366.8   507.8   398.6  514.59   422.6  514.68   430.5  513.26   442.5  513.14
   466.4   510.7  493.66 499.164   514.2  490.95   526.2  488.92   566.1  486.61
   617.9  485.98   625.8  485.72  635.93  485.93  686.02488.1922   716.7  490.56
   752.3   496.3   787.9  505.94   811.7  510.41   823.5  513.48   847.3  515.22
#Mann= 7 ,-1 , 0
       0     .12       0   57.74     .06       0  335.17     .12       0
  493.66     .06       0   617.9    .045       0  635.93     .06       0
  686.02     .12       0
Bank Sta=617.9,635.93
XS Rating Curve= 0 ,0
Exp/Cntr=0.3,0.1

Type RM Length L Ch R = 1 ,27325.1 ,441.9,418.1,370.5
XS GIS Cut Line= 3
      2399356.94       378997.25     2400006.228      378752.645
      2400043.12      378635.457
#Sta/Elev= 30
       0  502.73   39.67501.4069   115.6  500.86  169.32504.0547  169.98504.0926
   183.4  504.58   195.4   507.9   203.4  508.78   239.2  510.79   263.2  510.15
  295.71511.5985     327  512.75   354.9  515.76   398.8   516.3   422.7  509.01
  445.93496.5434   458.6  491.45   474.5   488.6  528.26  485.39   538.3  484.97
   546.3  485.38  600.48486.2314     642  488.82   665.9  495.43   677.9  497.19
   697.8  503.62   733.5  505.62   773.1  510.93  784.56510.8488   816.7  514.12
#Mann= 10 ,-1 , 0
       0     .12       0   39.67     .06       0  169.32     .12       0
  169.98     .06       0  295.71     .12       0  445.93     .06       0
  528.26    .045       0   546.3     .06       0  600.48     .12       0
  784.56    .016       0
Bank Sta=528.26,546.3
XS Rating Curve= 0 ,0
Exp/Cntr=0.3,0.1

Type RM Length L Ch R = 1 ,26907   ,344.2,347.1,374
XS GIS Cut Line= 6
     2399659.165      379637.569     2399870.145      379506.564
     2399932.511      379152.924     2399969.386      379128.538
     2400021.469      378881.142     2400035.358      378687.566
#Sta/Elev= 30
       0  520.98    23.6  519.07    35.5  516.44    59.1  514.61    78.8  510.65
    98.6  508.74   118.3  509.16   145.8  511.66  195.06511.0446   248.3  510.12
   292.2   507.9     404  497.65   419.9  494.19   439.9  493.39   471.8  487.73
   515.7  486.01   547.6  486.87   556.4  484.29   559.6  482.63   563.6  482.49
   571.4   485.5   579.5  488.84   591.5  488.43   603.4  490.99   640.5494.9211
  882.16495.8819  885.18495.9672  915.22496.6258   975.8  500.14  1098.5  509.65
#Mann= 8 ,-1 , 0
       0     .06       0  195.06     .12       0   556.4    .045       0
   571.4     .12       0   640.5    .016       0  882.16     .08       0
  885.18     .12       0  915.22    .016       0
#XS Ineff= 2 , 0
          479.08  489.12
Permanent Ineff=
       F       F
Bank Sta=556.4,571.4
XS Rating Curve= 0 ,0
Exp/Cntr=0.3,0.1

Type RM Length L Ch R = 1 ,26559.9 ,259.2,269.4,277.9
XS GIS Cut Line= 3
     2400142.747      379667.823     2400262.539      379268.083
     2400395.204      378858.214
#Sta/Elev= 30
       0  501.83    2.57501.8557   16.96502.4518   64.48501.5358    75.5  500.83
   98.93495.9894   135.1  495.18   174.9  491.95   210.6  484.29   226.5  482.37
   290.1  482.26   341.8  478.71   373.6  481.04   393.5  477.69   401.4  477.23
   413.3  477.62  450.84478.1323   469.2  477.76   493.1  481.68     537  478.41
   548.9  479.17   564.9  482.92  578.51483.6107   582.8 483.715   636.7  485.68
   668.6  488.48   720.5  490.75   756.4  494.97  820.27507.0698   848.1  510.42
#Mann= 11 ,-1 , 0
       0     .06       0    2.57     .12       0   16.96     .06       0
   64.48     .12       0   98.93     .07       0   393.5    .045       0
   413.3     .07       0  450.84     .12       0  578.51     .06       0
   582.8     .12       0  820.27     .06       0
Bank Sta=393.5,413.3
XS Rating Curve= 0 ,0
Exp/Cntr=0.3,0.1