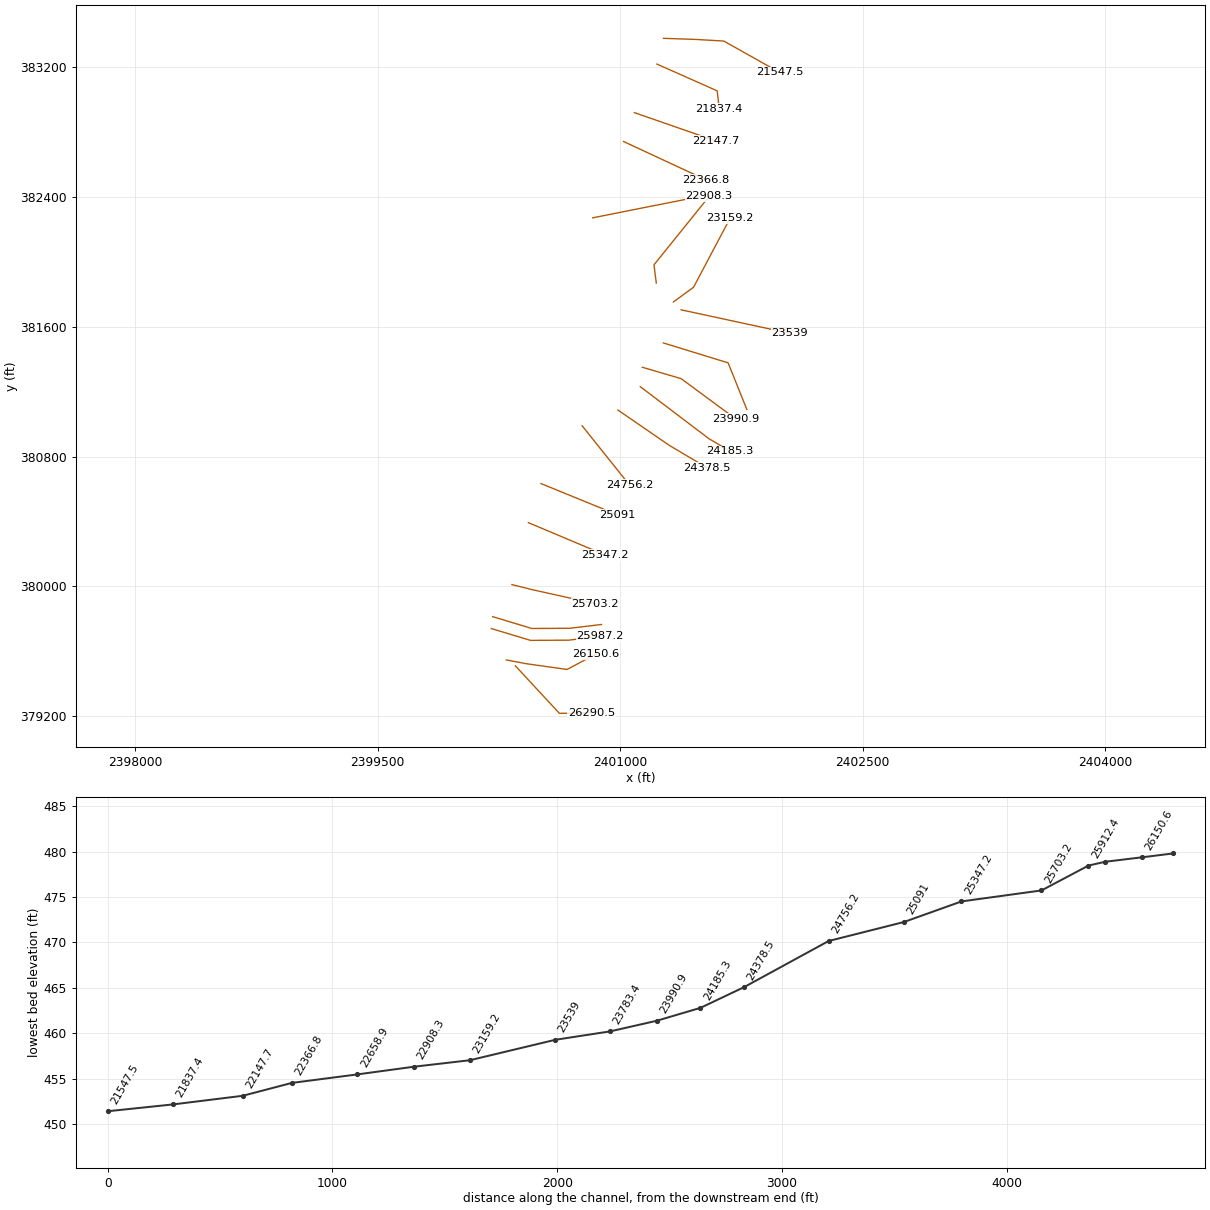
HEC-RAS study HARLANRUN.prj: HARLANRUN

--- HARLANRUN.g01 (geometry) --- (continued)

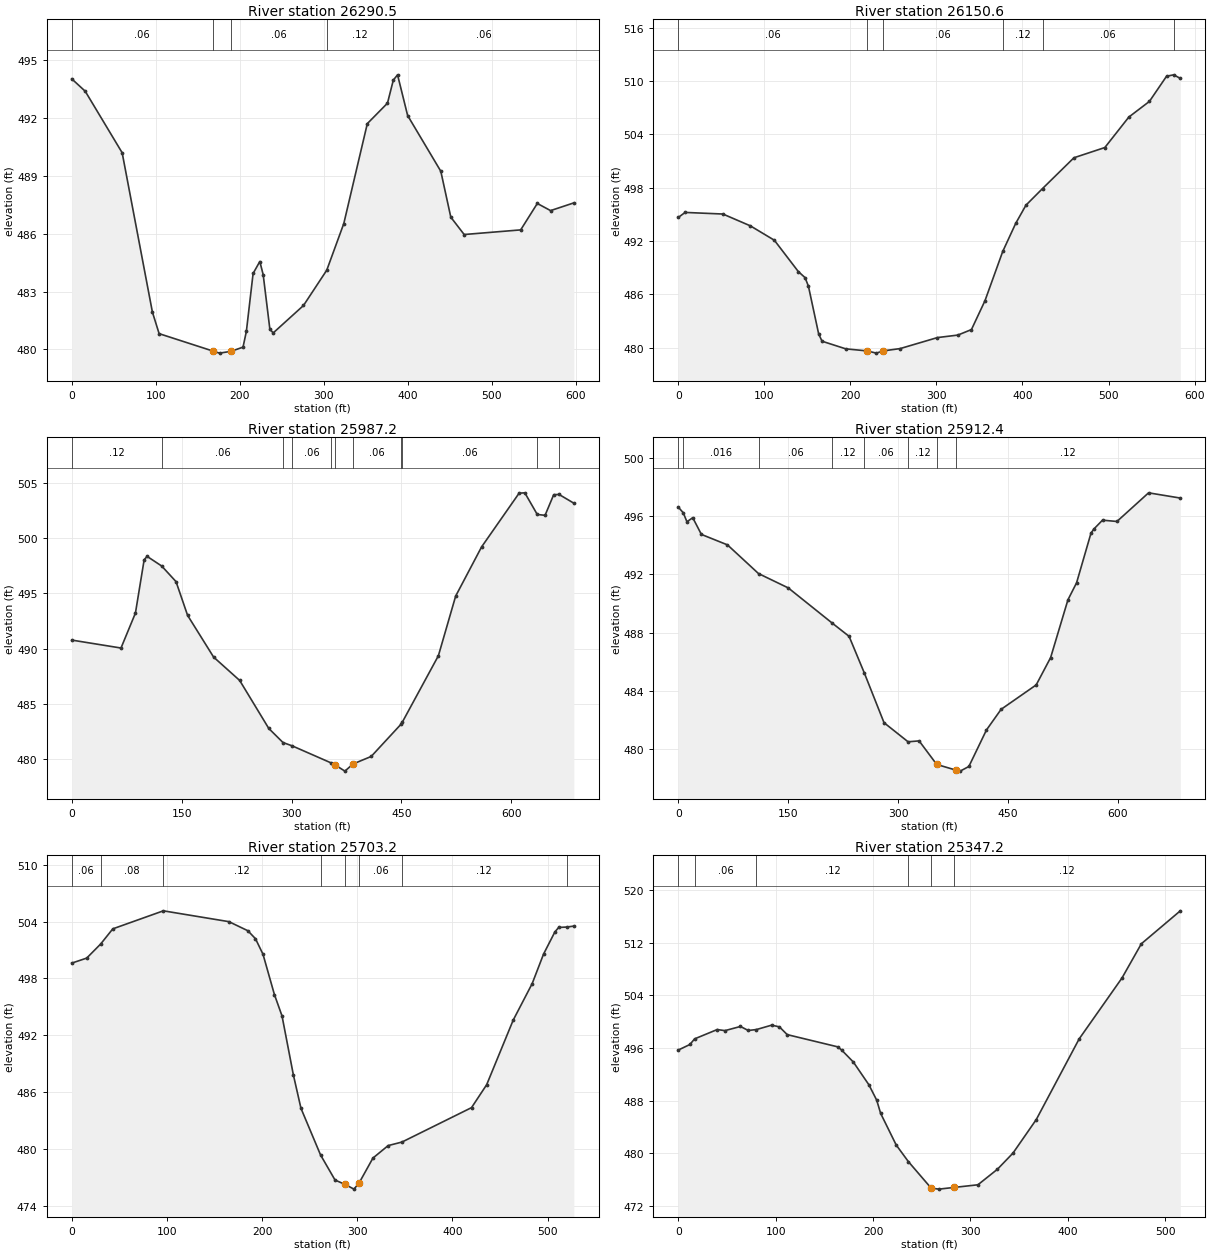
Type RM Length L Ch R = 1 ,26290.5 ,124,139.9,155.4
XS GIS Cut Line= 3
     2400352.382      379510.271     2400624.518      379217.302
     2400822.435      379221.208
#Sta/Elev= 30
       0  494.03      16  493.39      60   490.2      96  481.94     104  480.82
   167.9  479.92   175.9  479.81   189.3   479.9   203.9  480.12   207.9  480.94
   215.9  483.94   223.9  484.56   227.9  483.88   235.9  481.04   239.9  480.86
   275.9  482.28  303.59 484.109   323.9  486.53   351.9  491.71   375.9  492.77
  382.86493.9666   387.9  494.24   399.9  492.13   439.4  489.24   451.3  486.86
   467.2  485.96   534.5   486.2   554.3  487.57   570.1   487.2   597.8   487.6
#Mann= 5 ,-1 , 0
       0     .06       0   167.9    .045       0   189.3     .06       0
  303.59     .12       0  382.86     .06       0
Bank Sta=167.9,189.3
XS Rating Curve= 0 ,0
Exp/Cntr=0.3,0.1

Type RM Length L Ch R = 1 ,26150.6 ,160.3,163.5,167
XS GIS Cut Line= 4
     2400295.941      379546.915     2400421.393      379523.291
     2400671.393      379488.135      2400851.08      379583.187
#Sta/Elev= 30
       0  494.64       8  495.21    51.9  495.03    83.8   493.7   111.7  492.08
   139.5  488.56   147.4  487.87   151.3   486.9   163.2  481.53   167.1  480.72
   194.7  479.86   219.4  479.63   230.2  479.38   238.1  479.63   257.8  479.89
   301.2  481.13   324.9  481.41   340.7  482.03   356.4  485.27  377.04490.8138
   392.1  493.97     404  496.02  423.35497.8996   459.8  501.36   495.7  502.51
   523.6  505.94   547.5   507.7   567.4  510.53  575.69510.6906   583.4  510.29
#Mann= 6 ,-1 , 0
       0     .06       0   219.4    .045       0   238.1     .06       0
  377.04     .12       0  423.35     .06       0  575.69     .08       0
Bank Sta=219.4,238.1
XS Rating Curve= 0 ,0
Exp/Cntr=0.3,0.1

Type RM Length L Ch R = 1 ,25987.2 ,74.9,74.7,74.9
XS GIS Cut Line= 4
     2400203.511      379740.305     2400445.698      379667.389
     2400681.375      379668.691     2400876.688      379692.128
#Sta/Elev= 30
       0  490.77    67.2  490.05    86.9  493.22    98.8  498.05   102.8  498.36
   122.7497.4865   142.3  496.07   158.1  493.01   193.6  489.23   229.2  487.11
   268.9  482.76  288.26481.4848  300.97481.1777  353.34479.6538     359  479.47
   372.8  478.89  383.87479.5365   408.7  480.22  449.38483.1414  451.17483.3293
   500.4  489.35     524  494.76   559.4  499.22   610.6  504.09   618.4  504.12
  635.36502.1584     646  502.08   657.8  503.95  665.15503.9715   685.3  503.18
#Mann= 11 ,-1 , 0
       0     .12       0   122.7     .06       0  288.26     .12       0
  300.97     .06       0  353.34     .12       0     359    .045       0
  383.87     .06       0  449.38     .12       0  451.17     .06       0
  635.36     .08       0  665.15     .06       0
Bank Sta=359,383.87
XS Rating Curve= 0 ,0
Exp/Cntr=0.3,0.1

Type RM Length L Ch R = 1 ,25912.4 ,214,209.2,203.8
XS GIS Cut Line= 4
     2400211.757      379813.656     2400453.945      379740.739
     2400689.622      379742.041     2400884.935      379765.479
#Sta/Elev= 30
       0  496.63    6.78496.2421    11.9  495.62    19.8   495.9    31.6  494.75
    67.2  494.03  109.58492.0568   150.2  491.07  210.33488.6444   233.2  487.74
  253.96485.2257   280.9   481.8  313.72 480.487   328.8  480.55   352.8  478.93
   379.7  478.53   384.8  478.47   396.7  478.79   420.7   481.3   440.7  482.72
   488.6   484.4   508.3  486.28   531.9  490.25   543.7  491.42   563.4  494.84
   567.3  495.12   579.1  495.73   598.8  495.64     642  497.61   685.3  497.25
#Mann= 8 ,-1 , 0
       0     .08       0    6.78    .016       0  109.58     .06       0
  210.33     .12       0  253.96     .06       0  313.72     .12       0
   352.8    .045       0   379.7     .12       0
Bank Sta=352.8,379.7
XS Rating Curve= 0 ,0
Exp/Cntr=0.3,0.1

Type RM Length L Ch R = 1 ,25703.2 ,360.2,356,351.7
XS GIS Cut Line= 3
     2400330.664      380011.325     2400452.191      379980.943
     2400844.987      379894.138
#Sta/Elev= 30
       0  499.61    15.7  500.14   30.35501.6274    43.1  503.23   96.22505.1342
   165.1  503.99     185  503.03     193  502.19   200.9  500.55   212.9  496.29
   220.9  494.03   232.8  487.81   240.8  484.27  261.37479.3428   276.6  476.69
   287.1  476.23   296.5  475.73   302.1  476.42   316.4  479.01   332.4  480.33
   346.9 480.703     420  484.34   435.9  486.76   463.8  493.59   483.7  497.44
   495.7  500.57   507.6  502.91   511.6  503.38  519.95503.4209   527.5  503.52
#Mann= 8 ,-1 , 0
       0     .06       0   30.35     .08       0   96.22     .12       0
  261.37     .06       0   287.1    .045       0   302.1     .06       0
   346.9     .12       0  519.95     .06       0
Bank Sta=287.1,302.1
XS Rating Curve= 0 ,0
Exp/Cntr=0.3,0.1

Type RM Length L Ch R = 1 ,25347.2 ,256,256.3,256.5
XS GIS Cut Line= 2
      2400432.66       380393.27     2400907.921      380193.617
#Sta/Elev= 30
       0  495.67      12  496.52   16.77497.3728      40  498.79      48  498.63
    63.9  499.26    71.9  498.65   80.32498.7947    95.9  499.46   103.9   499.2
   111.9  498.02   163.8  496.16   167.8  495.67   179.8  493.85   195.8  490.38
   203.8  488.04   207.8  486.05   223.8  481.23   236.3478.7038   259.7  474.67
   267.7  474.52   282.7  474.77   307.7  475.18   327.7  477.54   343.7     480
   367.6   485.1   411.6  497.36   455.6  506.63   475.5  511.84   515.5  516.85
#Mann= 6 ,-1 , 0
       0     .12       0   16.77     .06       0   80.32     .12       0
   236.3     .06       0   259.7    .045       0   282.7     .12       0
Bank Sta=259.7,282.7
XS Rating Curve= 0 ,0
Exp/Cntr=0.3,0.1

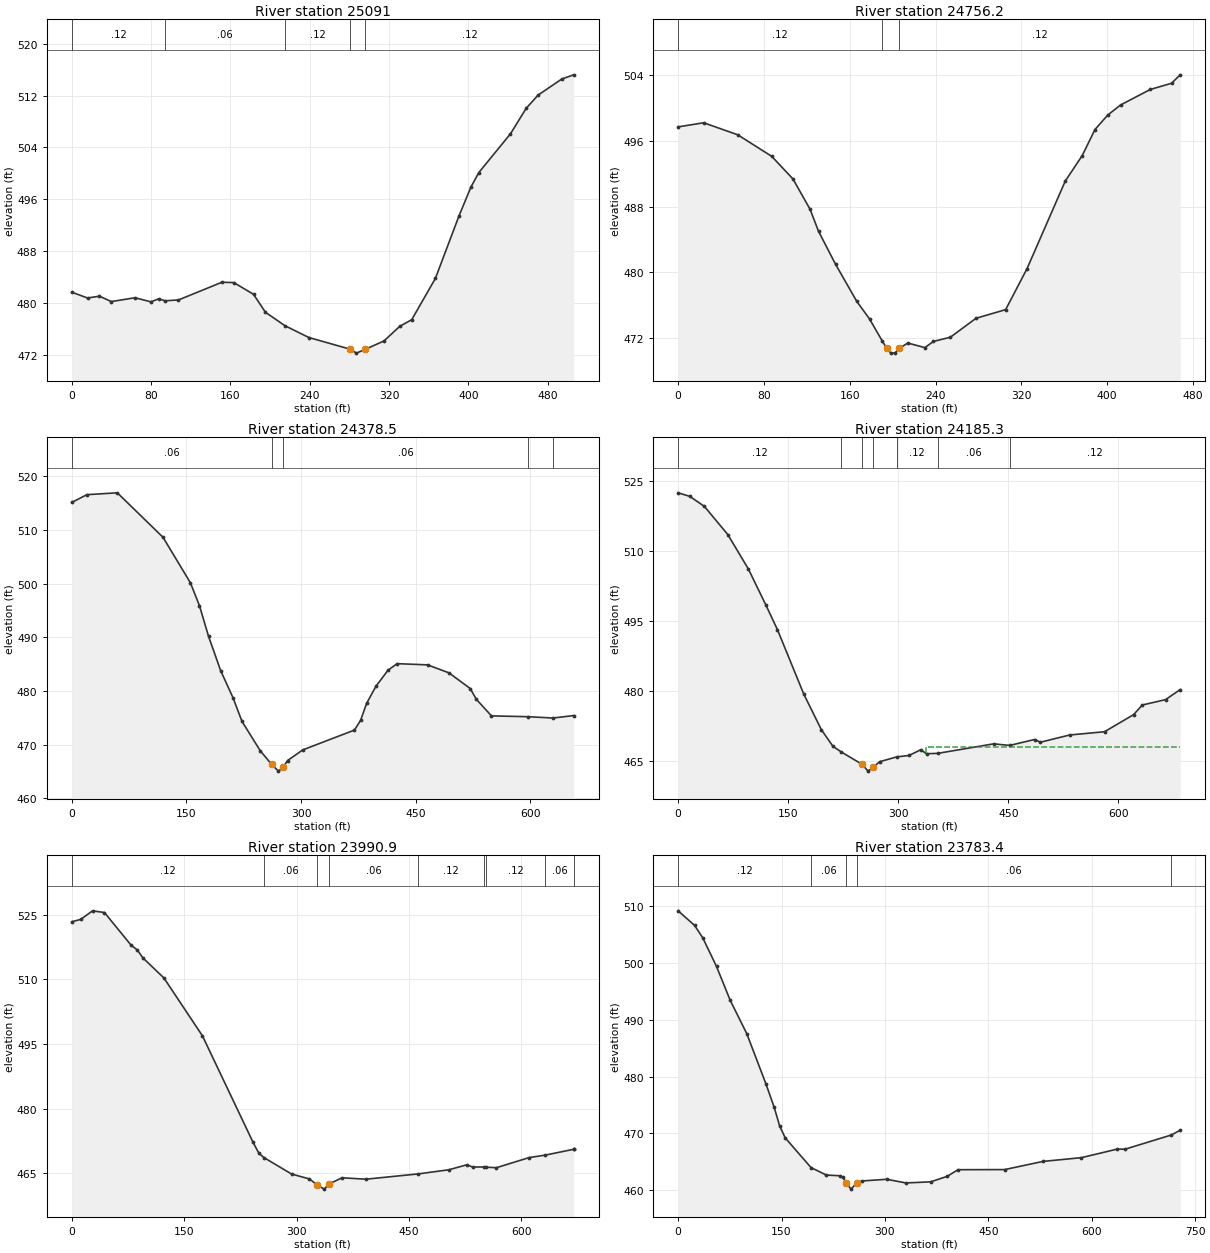
Type RM Length L Ch R = 1 ,25091   ,346.2,334.8,323.2
XS GIS Cut Line= 2
     2400510.785      380634.155     2400979.535      380443.183
#Sta/Elev= 30
       0  481.66    15.9  480.76    27.9  481.04    39.9  480.21    63.8   480.8
    79.7  480.17    87.7  480.63   94.16480.3295   107.6  480.46   151.4  483.19
   163.4  483.14   183.3  481.33   195.3  478.56  215.13476.4682   239.1  474.66
   280.9  472.85     287  472.25   295.9  472.83   314.8  474.13   330.8  476.39
   342.8  477.41   366.7  483.79   390.6  493.48   402.5  497.88   410.5  500.13
   442.4  506.11   458.3  510.05   470.3  512.09   494.2  514.57   506.2  515.21
#Mann= 5 ,-1 , 0
       0     .12       0   94.16     .06       0  215.13     .12       0
   280.9    .045       0   295.9     .12       0
Bank Sta=280.9,295.9
XS Rating Curve= 0 ,0
Exp/Cntr=0.3,0.1

Type RM Length L Ch R = 1 ,24756.2 ,371,377.7,384.7
XS GIS Cut Line= 2
     2400764.851      380990.651      2401057.66      380625.475
#Sta/Elev= 30
       0  497.72    23.8  498.22    55.5  496.76    87.3  494.13   107.1  491.37
     123  487.69   130.9  485.01   146.8  480.98   166.6  476.46   178.5  474.32
   190.2  471.67   194.4  470.77   198.3  470.16   202.3  470.19   206.3  470.75
   214.2  471.39   230.1  470.83     238  471.58   253.9   472.1   277.7   474.4
   305.4  475.46   325.3  480.44     361  491.12   376.8  494.22   388.7   497.4
   400.6  499.16   412.5  500.38   440.3  502.28   460.1  503.03   468.1  504.06
#Mann= 3 ,-1 , 0
       0     .12       0   190.2    .045       0   206.3     .12       0
Bank Sta=194.4,206.3
XS Rating Curve= 0 ,0
Exp/Cntr=0.3,0.1

Type RM Length L Ch R = 1 ,24378.5 ,194.1,193.2,191.8
XS GIS Cut Line= 3
     2400986.046      381087.714     2401304.205      380869.646
     2401537.278      380731.625
#Sta/Elev= 30
       0  515.16    19.9  516.61    59.6  516.95   119.3  508.67   155.1   500.2
     167  495.92   178.9   490.2   194.8  483.78   210.8  478.78   222.7  474.32
   246.5  468.87   261.5   466.3   270.4  465.06   276.5   465.8   282.3  467.04
   302.2  469.02   369.8  472.72   377.8  474.53   385.7   477.7   397.7  480.84
   413.6  483.87   425.6   485.1   465.4  484.87   493.3  483.39   521.2  480.46
   529.1  478.47     549  475.36   596.7475.2095  629.35474.9627   656.6  475.42
#Mann= 5 ,-1 , 0
       0     .06       0   261.5    .045       0   276.5     .06       0
   596.7     .12       0  629.35     .06       0
Bank Sta=261.5,276.5
XS Rating Curve= 0 ,0
Exp/Cntr=0.3,0.1

Type RM Length L Ch R = 1 ,24185.3 ,194,194.3,194.6
XS GIS Cut Line= 3
     2401124.518      381231.625     2401550.299       380910.01
     2401680.507      380834.489
#Sta/Elev= 30
       0  522.54    15.9  521.78    35.8  519.62    67.7  513.58    95.6  506.22
   119.5  498.48   135.4  493.14   171.2  479.34   195.1  471.71     211  468.11
  222.19466.9192   250.9  464.23   258.8  462.79   265.9  463.68   274.8  464.82
  297.89  465.85   314.6  466.15   330.5  467.37   338.5  466.53  353.76466.6052
   430.1  468.65  451.69468.3042   485.8  469.58   493.8     469   533.6  470.55
   581.1  471.25   620.7  474.92   632.6  476.99   664.3  478.14   684.1  480.29
#Mann= 7 ,-1 , 0
       0     .12       0  222.19     .06       0   250.9    .045       0
   265.9     .06       0  297.89     .12       0  353.76     .06       0
  451.69     .12       0
#XS Ineff= 2 , 0
                          337.87          467.95
Permanent Ineff=
       F       F
Bank Sta=250.9,265.9
XS Rating Curve= 0 ,0
Exp/Cntr=0.3,0.1

Type RM Length L Ch R = 1 ,23990.9 ,200,207.6,215.2
XS GIS Cut Line= 3
     2401137.539      381351.416     2401377.122      381281.104
     2401715.664      381032.406
#Sta/Elev= 30
       0  523.33    11.9  523.87    27.7  525.86    43.6  525.47    79.3  517.87
    87.2  516.84    95.1  514.92   122.9  510.32   174.4  496.88   241.8  472.25
   249.7  469.68  256.37468.6845   293.3  464.87   317.1  463.73   327.8   462.3
   336.9  461.37   342.8  462.52   360.6     464   392.4  463.67   462.6464.9037
   503.3  465.86   527.1  467.01     535  466.48  549.42466.5122  552.44466.4505
   566.7  466.34   610.3  468.68  632.09469.2598  669.51470.5984   669.8  470.61
#Mann= 9 ,-1 , 0
       0     .12       0  256.37     .06       0   327.8    .045       0
   342.8     .06       0   462.6     .12       0  549.42     .06       0
  552.44     .12       0  632.09     .06       0  669.51     .12       0
Bank Sta=327.8,342.8
XS Rating Curve= 0 ,0
Exp/Cntr=0.3,0.1

Type RM Length L Ch R = 1 ,23783.4 ,242.4,244.4,246.2
XS GIS Cut Line= 3
     2401267.747      381501.156     2401667.487       381378.76
     2401783.372         381091.
#Sta/Elev= 30
       0  509.19    23.9  506.62    35.8  504.42    55.7  499.39    75.6  493.42
    99.5  487.59   127.4  478.72   139.4  474.59   147.3  471.32   155.3  469.23
  192.77463.9955     215  462.68   234.9  462.55   238.9   462.3   243.9  461.29
   250.8   460.2   258.9  461.26   266.8  461.64   302.6  461.93   330.5  461.29
   366.3  461.48   390.2  462.44   406.1  463.62   473.7  463.64   529.4  465.08
   585.1  465.74   636.8  467.24   648.7  467.24  715.39469.7256   728.3  470.56
#Mann= 5 ,-1 , 0
       0     .12       0  192.77     .06       0   243.9    .045       0
   258.9     .06       0  715.39     .12       0
Bank Sta=243.9,258.9
XS Rating Curve= 0 ,0
Exp/Cntr=0.3,0.1

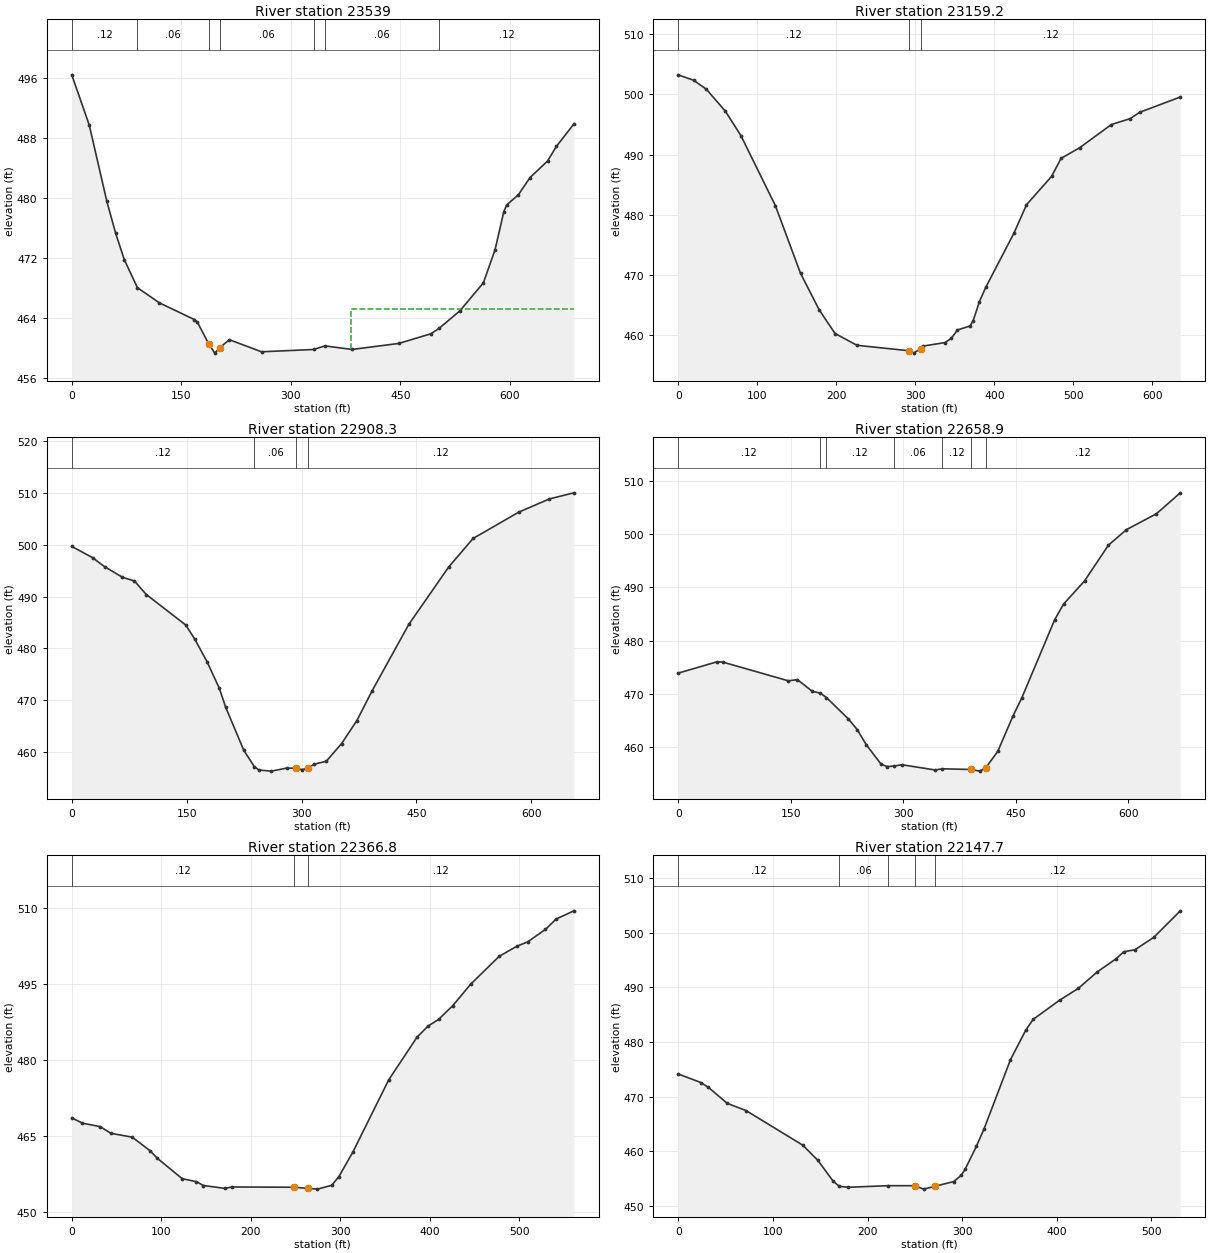
Type RM Length L Ch R = 1 ,23539   ,349.8,379.7,409.3
XS GIS Cut Line= 2
     2401377.122      381705.583     2402049.414      381560.804
#Sta/Elev= 30
       0   496.4      24  489.68      48  479.53      60   475.3      72  471.73
   89.89 468.001     120  465.98   167.9  463.75   171.9  463.43   187.6   460.5
   195.9  459.27   202.6  459.99   215.9  461.06   259.9  459.45  331.22459.7549
  346.71460.2364   383.8  459.76   447.8  460.56   491.8  461.85  503.23462.5829
   531.8  464.93   563.8  468.65   579.8  473.07   591.8  478.15   595.7  479.04
   611.7  480.39   627.7   482.7   651.7   484.9   663.7  486.84   687.7  489.84
#Mann= 7 ,-1 , 0
       0     .12       0   89.89     .06       0   187.6    .045       0
   202.6     .06       0  331.22     .12       0  346.71     .06       0
  503.23     .12       0
#XS Ineff= 2 , 0
                           382.8           465.1
Permanent Ineff=
       F       F
Bank Sta=187.6,202.6
XS Rating Curve= 0 ,0
Exp/Cntr=0.3,0.1

Type RM Length L Ch R = 1 ,23159.2 ,255.4,250.9,246.6
XS GIS Cut Line= 3
     2401328.945       381753.76     2401453.945      381844.906
     2401679.205      382269.385
#Sta/Elev= 30
       0  503.25    19.8  502.33    35.7  500.84    59.5  497.23    79.3  493.15
     123  481.49   154.7  470.28   178.5  464.17   198.4  460.28   226.2  458.32
   291.7  457.42   297.7  457.02   306.7  457.75   309.6  458.19   337.4  458.77
   345.3  459.46   353.3  460.87   369.2  461.53   373.1   462.4   381.1  465.59
     389  467.94   424.8  476.97   440.6  481.67   472.4  486.39   484.3  489.37
   508.2  491.17   547.9  494.99   571.7  495.97   583.6  497.01   635.2  499.57
#Mann= 3 ,-1 , 0
       0     .12       0   291.7    .045       0   306.7     .12       0
Bank Sta=291.7,306.7
XS Rating Curve= 0 ,0
Exp/Cntr=0.3,0.1

Type RM Length L Ch R = 1 ,22908.3 ,265.1,249.4,233.6
XS GIS Cut Line= 3
     2401223.476      381870.948     2401209.153      381982.927
     2401550.299      382404.802
#Sta/Elev= 30
       0   499.7    27.2  497.53    42.8  495.79    66.2  493.74    81.8  493.02
    97.3  490.41   148.8  484.52   160.8  481.73   176.7   477.4   192.7  472.27
   200.7  468.71   224.6  460.31  238.48457.1251   244.5  456.51   260.5   456.3
   280.4  456.88   293.1  456.87   300.4  456.59   308.1  456.84   316.4  457.64
   332.3  458.21   352.2  461.63   372.2  466.07   392.1  471.83     440  484.65
   491.9   495.7   523.8  501.23   583.6  506.33   623.5  508.87   655.4  510.05
#Mann= 4 ,-1 , 0
       0     .12       0  238.48     .06       0   293.1    .045       0
   308.1     .12       0
Bank Sta=293.1,308.1
XS Rating Curve= 0 ,0
Exp/Cntr=0.3,0.1

Type RM Length L Ch R = 1 ,22658.9 ,306.3,292.2,277.9
XS GIS Cut Line= 3
     2400830.702      382272.921     2400970.855      382300.822
     2401487.348      382402.818
#Sta/Elev= 30
       0  473.89    51.6  476.01    59.5  475.96   146.9  472.44   158.9  472.66
   178.8  470.46  189.56470.1192  197.51469.3043   226.7   465.3   238.6  463.28
   250.6  460.45   270.5  456.76   278.5  456.32  287.71456.4224   298.4  456.66
   342.3  455.68  352.22455.8984   390.2  455.77   402.2  455.46   410.1   456.1
   426.1   459.2     446  465.74     458  469.21   501.9  483.93   513.8  486.88
   541.7  491.22   573.6  497.96   597.6  500.87   637.5  503.85   669.4  507.79
#Mann= 7 ,-1 , 0
       0     .12       0  189.56     .06       0  197.51     .12       0
  287.71     .06       0  352.22     .12       0   390.2    .045       0
   410.1     .12       0
Bank Sta=390.2,410.1
XS Rating Curve= 0 ,0
Exp/Cntr=0.3,0.1

Type RM Length L Ch R = 1 ,22366.8 ,216.8,219,221.3
XS GIS Cut Line= 2
     2401020.768       382743.53     2401529.466      382507.666
#Sta/Elev= 30
       0   468.6    11.9  467.56    31.8  466.87    43.7  465.55    67.6  464.79
    87.5   462.1    95.4  460.64   123.3  456.59   139.2  455.99   147.1  455.23
     171  454.67     179  454.95   248.5  454.89   263.5  454.67   274.4  454.52
   290.3  455.28   298.2  456.97   314.2  461.94   353.9  476.11   385.7  484.58
   397.7  486.71   409.6  488.06   425.5  490.78   445.4  495.01   477.2  500.51
   497.1  502.53     509  503.37   528.9  505.84   540.8  507.88   560.7  509.52
#Mann= 3 ,-1 , 0
       0     .12       0   248.5    .045       0   263.5     .12       0
Bank Sta=248.5,263.5
XS Rating Curve= 0 ,0
Exp/Cntr=0.3,0.1

Type RM Length L Ch R = 1 ,22147.7 ,312.3,310.3,308.5
XS GIS Cut Line= 2
     2401088.042      382921.481     2401589.344       382747.87
#Sta/Elev= 30
       0  474.17    23.9  472.61    31.9  471.72    51.8   468.8    71.8  467.46
   131.6  461.14   147.6  458.35   163.5   454.6  170.12453.6215   179.5  453.44
  221.32453.7296     250  453.73   259.3   453.1   271.2  453.62   291.2  454.49
   299.2  455.67   303.2  456.77   315.1  460.96   323.1  464.11     351  476.77
     367  482.13     375  484.16   402.9  487.67   422.8  489.85   442.8  492.86
   462.7  495.26   470.7  496.53   482.6  496.91   502.6   499.2   530.5  504.03
#Mann= 5 ,-1 , 0
       0     .12       0  170.12     .06       0  221.32     .12       0
     250    .045       0   271.2     .12       0
Bank Sta=250,271.2
XS Rating Curve= 0 ,0
Exp/Cntr=0.3,0.1

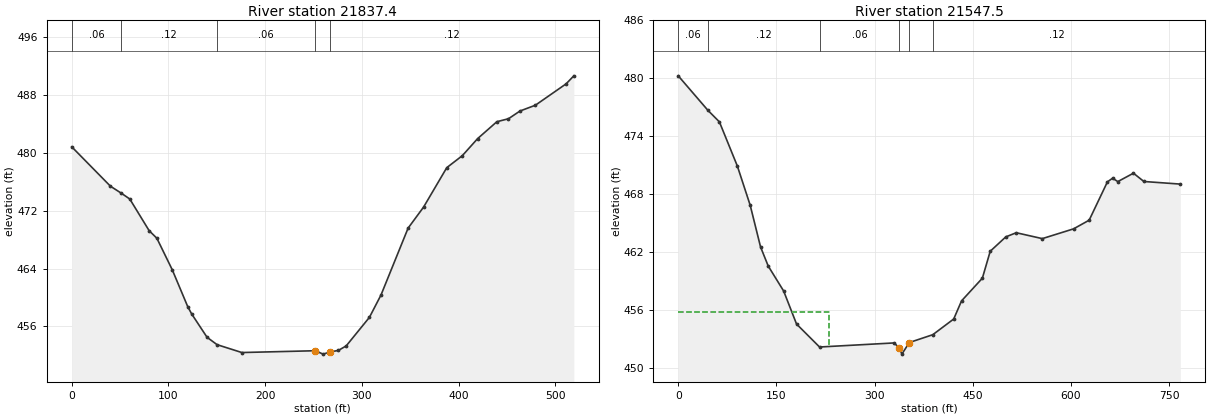
Type RM Length L Ch R = 1 ,21837.4 ,281.3,289.9,299.4
XS GIS Cut Line= 3
     2401226.931      383220.961     2401599.778      383055.843
     2401612.799      382945.166
#Sta/Elev= 30
       0  480.84      40  475.39   51.36474.4132      60  473.62      80  469.24
      88  468.19   103.9  463.83   119.9  458.73   123.9  457.73   139.9  454.48
  150.26453.4594   175.9  452.37   251.9  452.62   259.9  452.15   266.9  452.44
   275.8  452.67   283.8  453.29   307.8  457.24   319.8  460.34   347.8  469.59
   363.8   472.5   387.8  477.96   403.8  479.61   419.7  481.98   439.6  484.32
   451.6  484.73   463.5   485.8   479.4   486.6   511.2  489.56   519.2  490.67
#Mann= 5 ,-1 , 0
       0     .06       0   51.36     .12       0  150.26     .06       0
   251.9    .045       0   266.9     .12       0
Bank Sta=251.9,266.9
XS Rating Curve= 0 ,0
Exp/Cntr=0.3,0.1

Type RM Length L Ch R = 1 ,21547.5 ,63,62,51.6
XS GIS Cut Line= 4
     2401268.164      383379.554     2401468.466       383372.81
     2401641.011      383362.788     2401984.761       383170.08
#Sta/Elev= 30
       0  480.24   45.43476.6593    62.9  475.47    90.4  470.88     110  466.82
   125.8  462.51   137.5  460.53   161.1  457.94   180.8  454.52  215.96452.1379
     330  452.56   338.1  452.01   341.8   451.4   353.1   452.6  389.03453.4132
     421  455.04     433  456.92   464.8  459.27   476.8  462.06   500.6  463.55
   516.6  463.98   556.4  463.37   604.1  464.38     628  465.28   655.9  469.25
   663.8  469.63   671.8  469.28   695.7  470.15   711.6  469.29   767.3  469.02
#Mann= 6 ,-1 , 0
       0     .06       0   45.43     .12       0  215.96     .06       0
   338.1    .045       0   353.1     .06       0  389.03     .12       0
#XS Ineff= 2 , 0
          231.07  455.76
Permanent Ineff=
       F       F
Bank Sta=338.1,353.1
XS Rating Curve= 0 ,0
Exp/Cntr=0.3,0.1