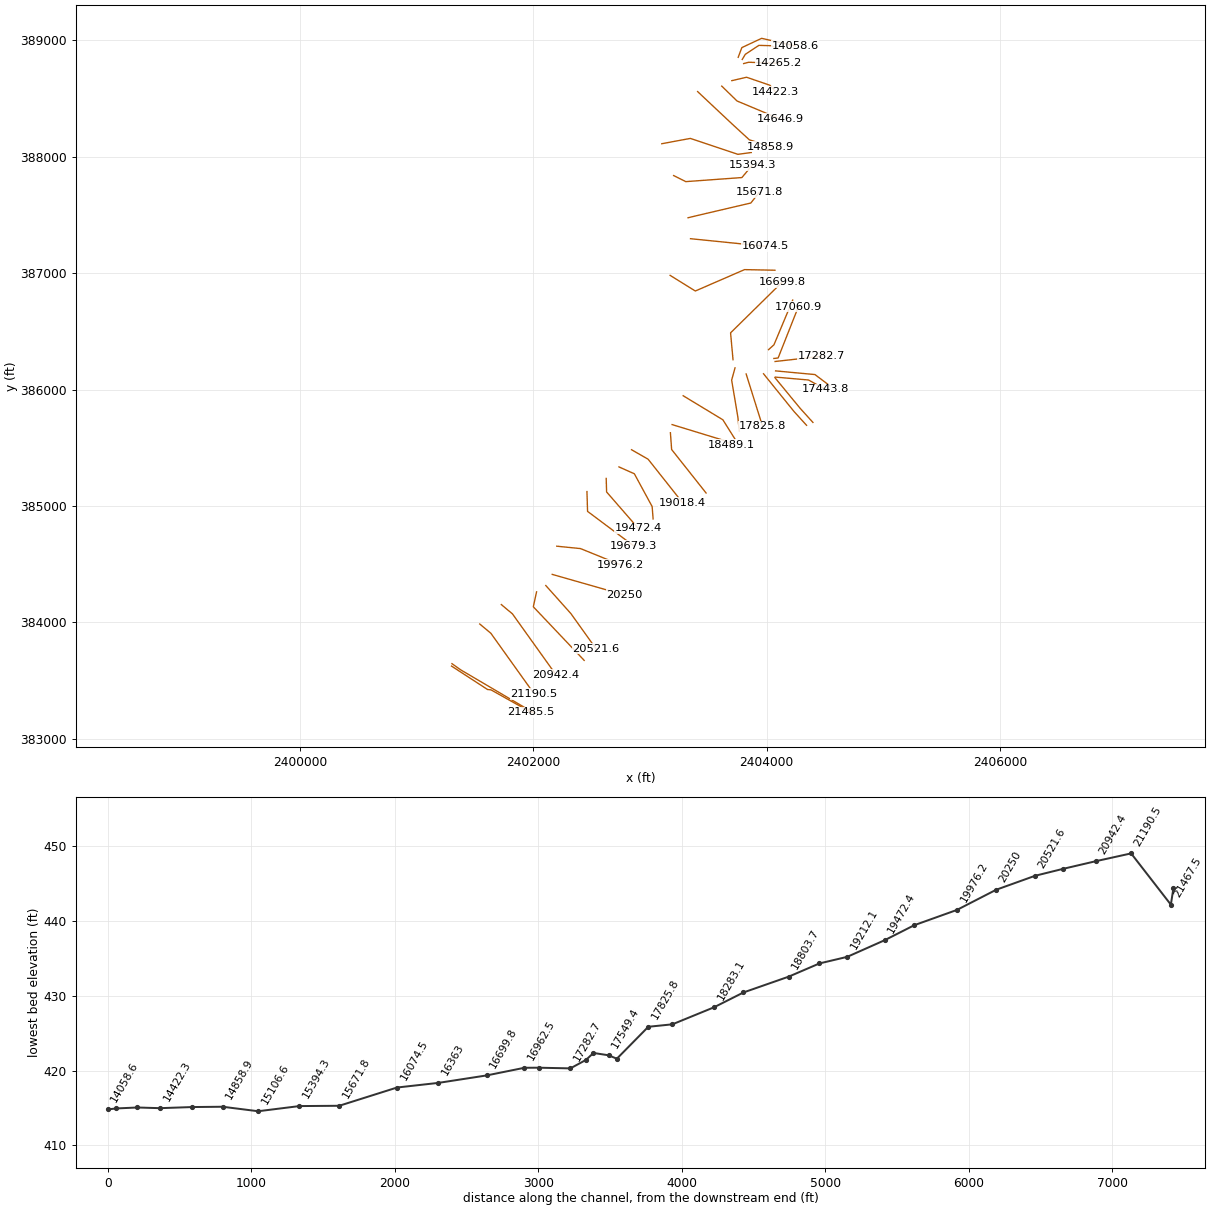
HEC-RAS study HARLANRUN.prj: HARLANRUN

--- HARLANRUN.g01 (geometry) --- (continued)

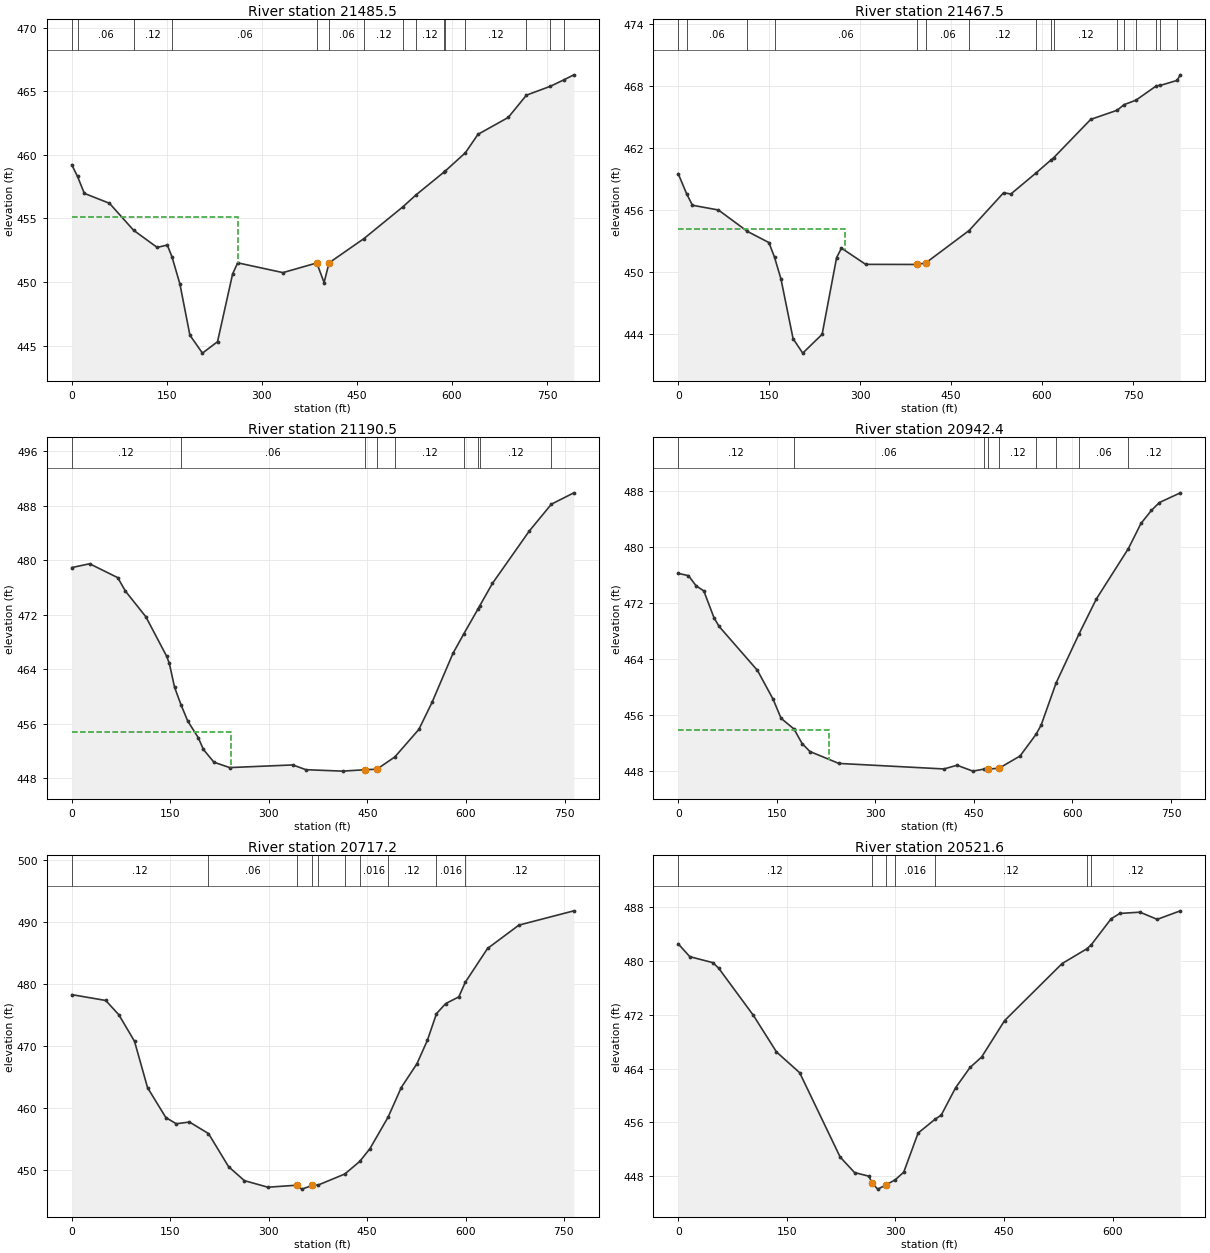
Type RM Length L Ch R = 1 ,21485.5 ,28,18,16
XS GIS Cut Line= 4
     2401299.426      383625.161     2401608.454      383423.772
     2401637.539      383420.948     2401981.289      383228.239
#Sta/Elev= 30
       0  459.22    9.04458.3047    19.8  456.97    59.5  456.19    97.5454.0723
   134.8  452.72   150.7  452.91  158.17451.9739   170.6  449.85   186.4  445.82
   206.2  444.41     230  445.31   253.8  450.64   261.8  451.51   333.2  450.74
   386.6   451.5   398.1  449.96     406  451.51  460.92453.4114  522.59455.9182
  543.32 456.856  587.86458.6664  589.54458.7374  621.03460.1608   640.9  461.61
   688.7  462.94  717.42464.6924  755.13  465.39  776.17465.8884   792.2  466.29
#Mann= 15 ,-1 , 0
       0     .12       0    9.04     .06       0    97.5     .12       0
  158.17     .06       0   386.6    .045       0     406     .06       0
  460.92     .12       0  522.59     .08       0  543.32     .12       0
  587.86     .06       0  589.54     .08       0  621.03     .12       0
  717.42     .08       0  755.13     .12       0  776.17     .08       0
#XS Ineff= 2 , 0
          261.87  455.08
Permanent Ineff=
       F       F
Bank Sta=386.6,406
XS Rating Curve= 0 ,0
Exp/Cntr=0.3,0.1

Type RM Length L Ch R = 1 ,21467.5 ,286.4,277,267.6
XS GIS Cut Line= 3
     2401303.109      383645.855     2401379.582      383591.926
     2402012.223      383218.929
#Sta/Elev= 30
       0  459.54   13.71457.6165    23.4  456.49    66.3  456.03  114.05453.9594
   149.5  452.88  158.78451.4609   169.4  449.36   189.4  443.58   205.3  442.18
   237.3     444   261.2  451.43   269.2  452.34   309.1  450.77     393  450.76
     408   450.9  479.69454.0449   536.6   457.7   548.6  457.58   590.6459.6393
  615.37460.9037  619.04 461.082   680.3   464.8  723.99465.6842  734.99466.2195
  754.77466.6552   788.7468.0505   794.8 468.083  822.63468.5696     828  469.11
#Mann= 16 ,-1 , 0
       0     .12       0   13.71     .06       0  114.05     .12       0
  158.78     .06       0     393    .045       0     408     .06       0
  479.69     .12       0   590.6     .06       0  615.37     .08       0
  619.04     .12       0  723.99     .06       0  734.99     .08       0
  754.77     .12       0   788.7     .06       0   794.8     .08       0
  822.63     .12       0
#XS Ineff= 2 , 0
          274.71  454.23
Permanent Ineff=
       F       F
Bank Sta=393,408
XS Rating Curve= 0 ,0
Exp/Cntr=0.3,0.1

Type RM Length L Ch R = 1 ,21190.5 ,248.1,248.1,248.1
XS GIS Cut Line= 3
     2401541.474      383986.457      2401636.96      383906.596
     2402008.488      383385.762
#Sta/Elev= 30
       0  478.93    27.2  479.49      70  477.45    81.7  475.47   112.8   471.7
   144.5  465.89   148.5  464.85   156.5  461.34  166.11458.8157   176.5  456.39
   192.5  453.95   200.4  452.21   216.4  450.34   240.4  449.55   336.4  449.94
   356.4  449.24   412.4  449.03   446.9  449.24   464.4  449.31  491.79451.1204
   528.3  455.16   548.3  459.12   580.3  466.35  596.95 469.236  618.36472.8557
  620.62473.2592   640.3  476.61   696.3  484.29  729.97488.2419   764.2  489.91
#Mann= 9 ,-1 , 0
       0     .12       0  166.11     .06       0   446.9    .045       0
   464.4     .06       0  491.79     .12       0  596.95     .06       0
  618.36    .016       0  620.62     .12       0  729.97     .08       0
#XS Ineff= 2 , 0
          242.36  454.73
Permanent Ineff=
       F       F
Bank Sta=446.9,464.4
XS Rating Curve= 0 ,0
Exp/Cntr=0.3,0.1

Type RM Length L Ch R = 1 ,20942.4 ,222,225.2,228.4
XS GIS Cut Line= 3
      2401726.37      384153.124     2401821.856      384073.262
     2402193.384      383552.429
#Sta/Elev= 30
       0   476.2    15.6  475.87    27.2  474.42    38.9   473.7    54.5  469.85
    62.2  468.63   120.6  462.35   144.5  458.22   156.5  455.52  176.25453.9844
   188.5  451.92   200.4  450.78   244.4  449.08   404.4  448.29   424.4  448.82
   448.4  447.98  464.86448.2612   470.9  448.26   488.4   448.4   520.3  450.14
  544.59  453.23   552.3  454.53  575.12 460.558  609.92467.5356   636.3  472.53
   685.2479.7418   704.3  483.32   720.3  485.19   732.3   486.3   764.2  487.69
#Mann= 9 ,-1 , 0
       0     .12       0  176.25     .06       0  464.86     .12       0
   470.9    .045       0   488.4     .12       0  544.59    .016       0
  575.12     .12       0  609.92     .06       0   685.2     .12       0
#XS Ineff= 2 , 0
          230.04  453.84
Permanent Ineff=
       F       F
Bank Sta=470.9,488.4
XS Rating Curve= 0 ,0
Exp/Cntr=0.3,0.1

Type RM Length L Ch R = 1 ,20717.2 ,196.3,195.7,195
XS GIS Cut Line= 3
     2402028.453      384262.499     2402000.675      384134.026
     2402436.439      383673.957
#Sta/Elev= 30
       0   478.3    51.8  477.36    71.7  475.06    95.6  470.79   115.5  463.31
   143.4  458.49   159.3   457.5   179.3  457.78  208.34455.9232     239  450.58
     263  448.34   298.8  447.28   342.7   447.6   350.6  446.97   366.6  447.56
  375.67447.6394  416.16449.4092  438.81451.4337   454.3  453.48  482.14 458.588
   502.1  463.34     526  467.17   541.9  470.94  555.77475.2354   569.8  476.86
   589.8  477.94  599.57480.2769   633.6  485.74   681.4   489.5   765.1   491.8
#Mann= 10 ,-1 , 0
       0     .12       0  208.34     .06       0   342.7    .045       0
   366.6     .06       0  375.67     .12       0  416.16     .06       0
  438.81    .016       0  482.14     .12       0  555.77    .016       0
  599.57     .12       0
Bank Sta=342.7,366.6
XS Rating Curve= 0 ,0
Exp/Cntr=0.3,0.1

Type RM Length L Ch R = 1 ,20521.6 ,258.3,271.5,284.8
XS GIS Cut Line= 3
     2402107.663      384316.752     2402322.941      384075.433
      2402537.84      383774.285
#Sta/Elev= 30
       0  482.57      16  480.66    47.9  479.77    55.9  478.94   103.8  471.92
   135.7  466.47   167.7  463.38   223.6  450.82   243.5  448.51   263.5  447.96
   267.5  446.96   275.5  446.04   286.7  446.64  300.02447.4672   311.4  448.56
   331.3   454.4   355.2  456.49   363.2  457.06   383.1  461.15     403  464.16
   418.9   465.7   450.7  471.14   530.2  479.64  564.05 481.815  570.19482.4042
   597.9  486.31   609.8   487.1   637.7  487.29   661.5  486.22   693.4  487.49
#Mann= 7 ,-1 , 0
       0     .12       0   267.5    .045       0   286.7     .12       0
  300.02    .016       0   355.2     .12       0  564.05     .06       0
  570.19     .12       0
Bank Sta=267.5,286.7
XS Rating Curve= 0 ,0
Exp/Cntr=0.3,0.1

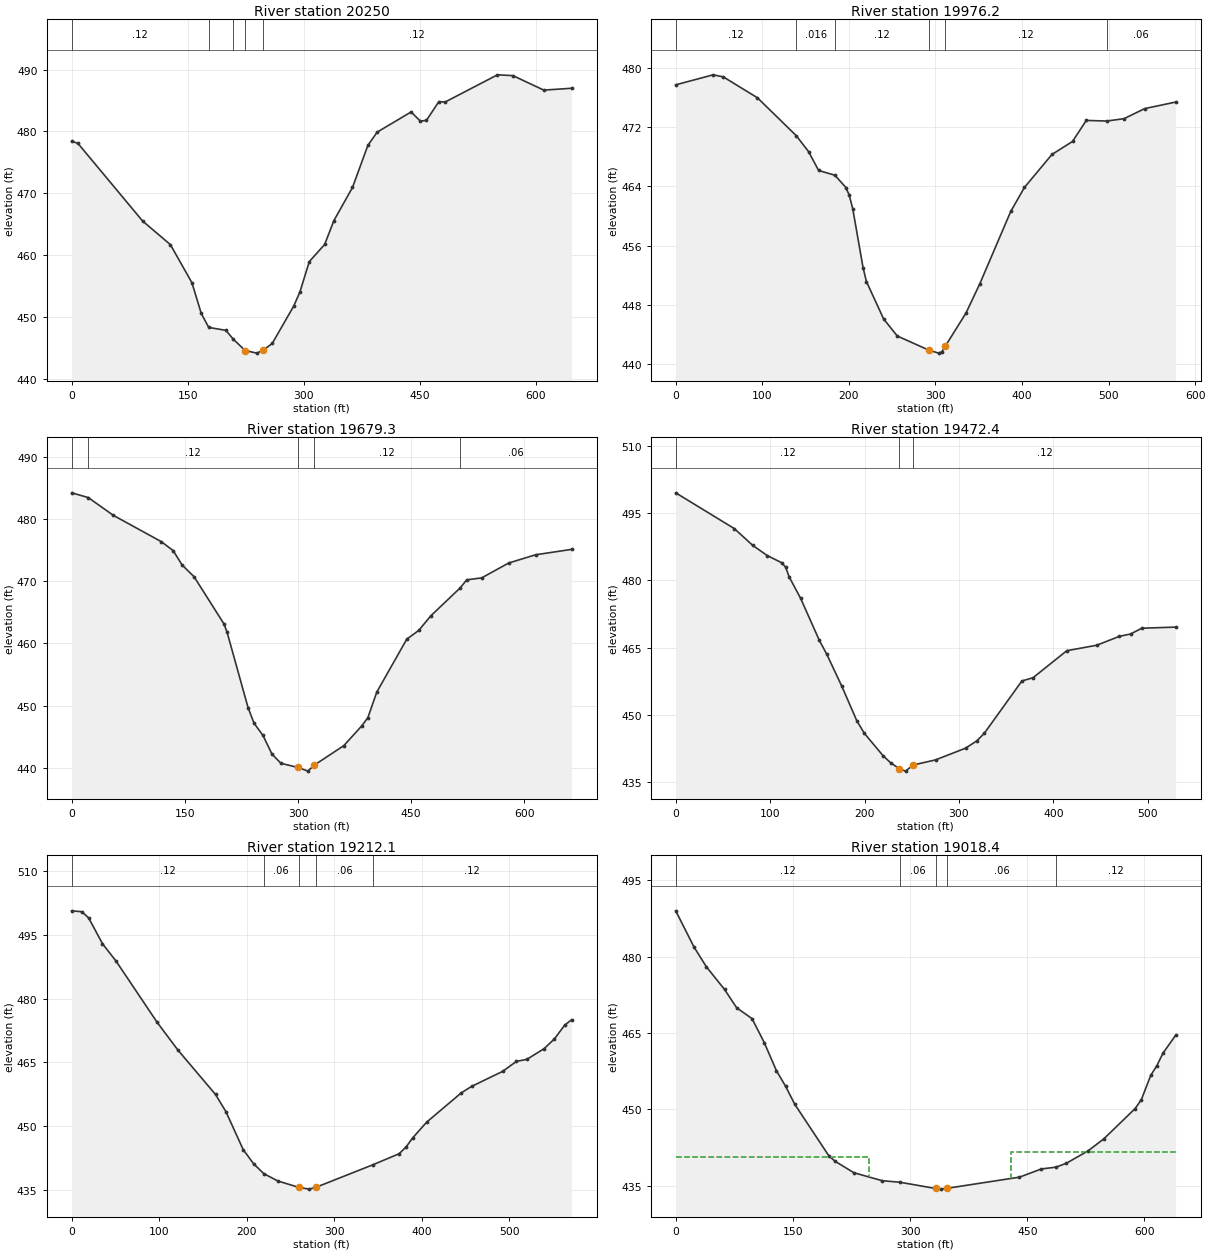
Type RM Length L Ch R = 1 ,20250   ,276,273.8,270.9
XS GIS Cut Line= 2
     2402162.695      384412.367     2402784.344      384234.862
#Sta/Elev= 30
       0   478.4       8  478.08    91.8  465.51   127.7   461.7   155.6  455.53
   167.6  450.58  177.28448.3226   199.5  447.85  209.28446.3872   224.4  444.59
   239.4  444.17   247.4  444.62   259.4  445.73   287.3   451.8   295.3  454.09
   307.3  458.96   327.2  461.73   339.2   465.6   363.2  470.94   383.1  477.74
   395.1  479.88     439  483.14     451  481.65   458.9  481.79   474.9  484.81
   482.9  484.74   550.7  489.14   570.7  489.01   610.6  486.67   646.5  486.97
#Mann= 5 ,-1 , 0
       0     .12       0  177.28    .016       0  209.28     .12       0
   224.4    .045       0   247.4     .12       0
Bank Sta=224.4,247.4
XS Rating Curve= 0 ,0
Exp/Cntr=0.3,0.1

Type RM Length L Ch R = 1 ,19976.2 ,302.8,297,291.5
XS GIS Cut Line= 3
     2402201.757      384654.554     2402405.189      384634.026
     2402750.675      384493.401
#Sta/Elev= 30
       0  477.71    43.2  479.06      55  478.78    94.4  475.96  139.24470.8414
   153.4   468.7   165.1  466.14  183.83465.4996   196.6  463.84   200.5  462.78
   204.5  460.97   216.4  453.03   220.3  451.14   240.2  446.08     256  443.78
   292.5  441.87   303.7  441.47   307.5  441.65   311.6  442.44   335.4   446.9
   351.3  450.84     387   460.6   402.9  463.86   434.6   468.3   458.4  470.06
   474.3   472.9  497.99472.8192     518  473.14   541.8   474.5   577.5  475.38
#Mann= 6 ,-1 , 0
       0     .12       0  139.24    .016       0  183.83     .12       0
   292.5    .045       0   311.6     .12       0  497.99     .06       0
Bank Sta=292.5,311.6
XS Rating Curve= 0 ,0
Exp/Cntr=0.3,0.1

Type RM Length L Ch R = 1 ,19679.3 ,211.6,206.9,202
XS GIS Cut Line= 3
     2402460.311       385123.61     2402465.519      384953.471
     2402859.616      384658.332
#Sta/Elev= 30
       0  484.26   21.94483.5009    55.4  480.62   118.8   476.4   134.6  474.94
   146.5  472.62   162.3  470.74     202  463.12     206  461.81   233.8  449.67
   241.7  447.16   253.6  445.18   265.5  442.18   277.4  440.69     300  440.02
   313.2  439.43   321.1  440.36   360.8  443.54   384.6  446.73   392.6  448.04
   404.5  452.18   444.2  460.69   460.1   462.1     476  464.44  515.13468.9631
   523.6  470.24   543.5  470.56   579.2  472.95   614.9  474.28   662.6  475.15
#Mann= 5 ,-1 , 0
       0     .08       0   21.94     .12       0     300    .045       0
   321.1     .12       0  515.13     .06       0
Bank Sta=300,321.1
XS Rating Curve= 0 ,0
Exp/Cntr=0.3,0.1

Type RM Length L Ch R = 1 ,19472.4 ,265.4,260.3,255.2
XS GIS Cut Line= 3
     2402625.241      385236.457     2402628.713      385120.137
     2402899.674        384808.2
#Sta/Elev= 30
       0  499.55    62.1  491.56    81.5  487.83      97  485.54   112.5  483.92
   116.4  482.95   120.3  480.74   132.3     476   152.1  466.63   160.1  463.48
     176  456.35   191.9  448.64   199.8  445.87   219.7  440.85   227.6   439.3
   236.6     438   243.5  437.42   251.6  438.79   275.3  439.93   307.1  442.55
     319  444.18   326.9  445.86   366.7  457.54   378.6  458.28   414.3   464.3
   446.1  465.53     470  467.51   481.9  468.04   493.8  469.33   529.6  469.57
#Mann= 3 ,-1 , 0
       0     .12       0   236.6    .045       0   251.6     .12       0
Bank Sta=236.6,251.6
XS Rating Curve= 0 ,0
Exp/Cntr=0.3,0.1

Type RM Length L Ch R = 1 ,19212.1 ,189.7,193.6,197.6
XS GIS Cut Line= 4
     2402734.616      385335.415     2402866.561      385276.387
     2403019.004      384994.812     2403027.278      384888.929
#Sta/Elev= 30
       0  500.69    11.7  500.48    19.5  498.99    35.2  492.95    50.8  488.83
    97.7  474.43   121.1  467.99   164.3  457.47   176.2  453.42   195.9   444.5
   207.8  441.16  219.52438.8344   235.5  437.11   259.2  435.63     271   435.2
     279  435.63  343.82440.9156   373.8  443.51   381.7  445.06   389.6  447.29
   405.4  450.96     445  457.86   456.8  459.38   492.3  462.92     508  465.27
   519.8  465.73   539.5  468.25   551.3  470.54   563.1   473.8   570.9  475.05
#Mann= 5 ,-1 , 0
       0     .12       0  219.52     .06       0   259.2    .045       0
     279     .06       0  343.82     .12       0
Bank Sta=259.2,279
XS Rating Curve= 0 ,0
Exp/Cntr=0.3,0.1

Type RM Length L Ch R = 1 ,19018.4 ,214.6,214.7,214.6
XS GIS Cut Line= 3
     2402842.255      385482.985     2402984.616      385401.387
     2403279.755      385028.124
#Sta/Elev= 30
       0  488.98    23.4  481.87    39.1  478.02    62.5  473.53    78.1  469.92
    97.7  467.81   113.3  463.11   128.9  457.58   140.6  454.53   152.4  450.98
   196.1  440.84   204.1  439.78   228.1  437.54   264.1  435.98  287.05435.6714
   332.6  434.45     340  434.32   347.6  434.49     440  436.67     468  438.28
  486.78438.6382     500   439.4     528  441.85     548   444.2     588  450.13
     596  451.88     608  456.64   615.9  458.58   623.9  461.07   639.9  464.53
#Mann= 5 ,-1 , 0
       0     .12       0  287.05     .06       0   332.6    .045       0
   347.6     .06       0  486.78     .12       0
#XS Ineff= 2 , 0
          248.01  440.64  428.63          441.56
Permanent Ineff=
       F       F
Bank Sta=332.6,347.6
XS Rating Curve= 0 ,0
Exp/Cntr=0.3,0.1

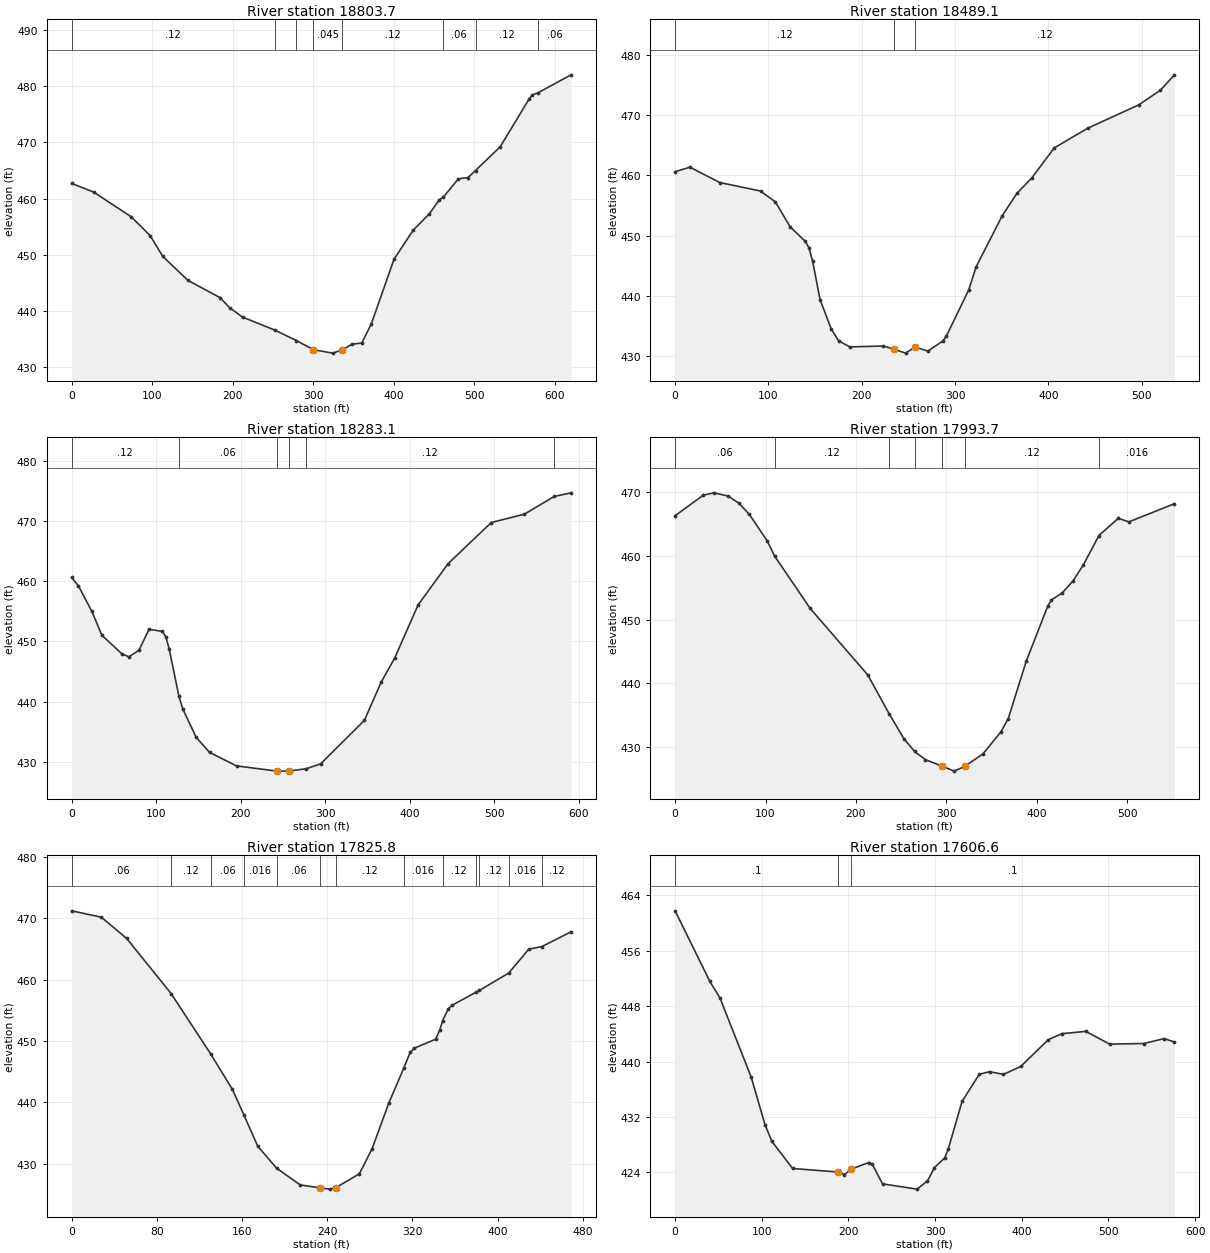
Type RM Length L Ch R = 1 ,18803.7 ,301.2,314.7,328.1
XS GIS Cut Line= 3
     2403175.588      385628.818     2403186.005      385484.721
     2403481.144      385111.457
#Sta/Elev= 30
       0  462.71    27.3  461.18    74.2  456.76    97.6  453.42   113.2  449.74
   144.5  445.48   184.5   442.4   196.5  440.59   212.4  438.95   252.3436.6478
   279.1434.7937   300.4  433.16   324.4  432.55   336.4  433.14   348.4  434.14
   360.4  434.35   372.4  437.79   400.4  449.22   424.4  454.43   444.4  457.31
   456.4  459.75   461.4 460.225   480.4  463.52   492.4  463.76  501.71465.0068
   532.4  469.23   568.3  477.72   572.3  478.43  579.48478.8308   620.3  482.01
#Mann= 8 ,-1 , 0
       0     .12       0   252.3     .06       0   279.1     .12       0
   300.4    .045       0   336.4     .12       0   461.4     .06       0
  501.71     .12       0  579.48     .06       0
Bank Sta=300.4,336.4
XS Rating Curve= 0 ,0
Exp/Cntr=0.3,0.1

Type RM Length L Ch R = 1 ,18489.1 ,211.4,206,200.7
XS GIS Cut Line= 3
     2403190.159       385698.72     2403643.244      385560.046
     2403694.004       385525.93
#Sta/Elev= 30
       0  460.63    15.9  461.38    47.8  458.83    91.6  457.41   107.5  455.59
   123.4  451.42   139.4  449.06   143.3     448   147.3  445.77   155.3  439.35
   167.2  434.48   175.2  432.49   187.1  431.48     223  431.62   234.9  431.08
   246.9  430.44   257.2  431.44   270.8  430.78   286.7  432.44   290.7  433.29
   314.6  440.98   322.5  444.79   350.4   453.3   366.3  457.04   382.2   459.6
   406.1  464.58     442  467.86   496.8  471.76   519.7  474.16     535  476.75
#Mann= 3 ,-1 , 0
       0     .12       0   234.9    .045       0   257.2     .12       0
Bank Sta=234.9,257.2
XS Rating Curve= 0 ,0
Exp/Cntr=0.3,0.1

Type RM Length L Ch R = 1 ,18283.1 ,308.9,289.4,270.4
XS GIS Cut Line= 3
     2403284.963      385946.526     2403625.241      385739.929
     2403727.672      385576.735
#Sta/Elev= 30
       0  460.61       8  459.22    23.9  454.99    35.8  451.01    59.7   447.9
    67.7  447.44    79.6  448.51    91.6  452.01   107.5  451.64   111.5  450.74
   115.4  448.76  126.91440.9012   131.4  438.81   147.3  434.08   163.2  431.56
   195.1  429.32   242.5  428.46   242.8  428.45   257.5  428.47  277.65428.8489
   294.6  429.66   346.3  436.87   366.2  443.23   382.2  447.23   409.9  456.05
   445.3  462.89   496.4  469.73   535.7  471.13  570.99 474.069   590.8  474.67
#Mann= 6 ,-1 , 0
       0     .12       0  126.91     .06       0   242.5    .045       0
   257.5     .06       0  277.65     .12       0  570.99    .016       0
Bank Sta=242.5,257.5
XS Rating Curve= 0 ,0
Exp/Cntr=0.3,0.1

Type RM Length L Ch R = 1 ,17993.7 ,165,167.9,170.3
XS GIS Cut Line= 4
     2403729.408       386186.11     2403700.395      386080.407
      2403753.87      385762.299     2403765.866      385642.707
#Sta/Elev= 30
       0  466.31    31.3  469.54    43.1   469.9    58.7  469.39    70.5  468.28
    82.2   466.5   101.8  462.37   110.1 459.955   149.4  451.74   213.2  441.28
  236.64435.2251     253  431.29  264.94429.2658   276.9  427.98   295.1  426.98
   308.7  426.18   320.7  426.95   340.6   428.9   360.5  432.37   368.5  434.43
   388.4  443.43   412.3  452.14   416.2  453.06   428.2  454.18   439.9  456.01
   451.6  458.58  468.81463.1926   490.3   465.9     502  465.34   552.4  468.19
#Mann= 7 ,-1 , 0
       0     .06       0   110.1     .12       0  236.64    .016       0
  264.94     .06       0   295.1    .045       0   320.7     .12       0
  468.81    .016       0
Bank Sta=295.1,320.7
XS Rating Curve= 0 ,0
Exp/Cntr=0.3,0.1

Type RM Length L Ch R = 1 ,17825.8 ,210.6,219.2,227.5
XS GIS Cut Line= 2
     2403824.739      386133.306     2403964.778      385685.804
#Sta/Elev= 30
       0  471.19    27.8  470.16    51.7  466.69   93.45457.7031   130.7447.8339
     151  442.09   161.8437.9187   174.8  432.82  192.69429.2316   214.6  426.54
   233.3  426.06   242.4  425.85   248.3  426.11   270.2  428.35   282.1  432.42
     298  439.95  311.89445.5663   317.9  448.14   321.9  448.83   341.7  450.26
   345.7  451.76  348.34453.2912   353.7  455.23   357.6  455.85  379.43457.8875
  382.95458.2253  410.52461.0647   429.2  464.94  441.61465.3717   468.9  467.77
#Mann= 13 ,-1 , 0
       0     .06       0   93.45     .12       0   130.7     .06       0
   161.8    .016       0  192.69     .06       0   233.3    .045       0
   248.3     .12       0  311.89    .016       0  348.34     .12       0
  379.43     .06       0  382.95     .12       0  410.52    .016       0
  441.61     .12       0
Bank Sta=233.3,248.3
XS Rating Curve= 0 ,0
Exp/Cntr=0.3,0.1

Type RM Length L Ch R = 1 ,17606.6 ,56.9,57.1,57.3
XS GIS Cut Line= 3
     2403973.697       386134.99     2404234.113      385812.074
     2404342.441      385692.421
#Sta/Elev= 30
       0  461.77    39.9  451.62    51.8  449.17    87.8  437.75   103.7   430.9
   111.7  428.47   135.6  424.56   188.1  424.05   195.4  423.68   203.1  424.46
   223.4  425.42   227.4  425.19   239.3  422.34   279.2  421.58   291.2  422.76
   299.2  424.68   311.1   426.1   315.1  427.33   331.1  434.25     351  438.17
     363  438.54   378.9  438.15   398.9   439.3   430.6  443.16   446.3  444.03
   473.9  444.36   501.4  442.52   540.8  442.61   564.4  443.32   576.2  442.82
#Mann= 3 , 0 , 0
       0      .1       0   188.1    .045       0   203.1      .1       0
Bank Sta=188.1,203.1
XS Rating Curve= 0 ,0
Exp/Cntr=0.3,0.1

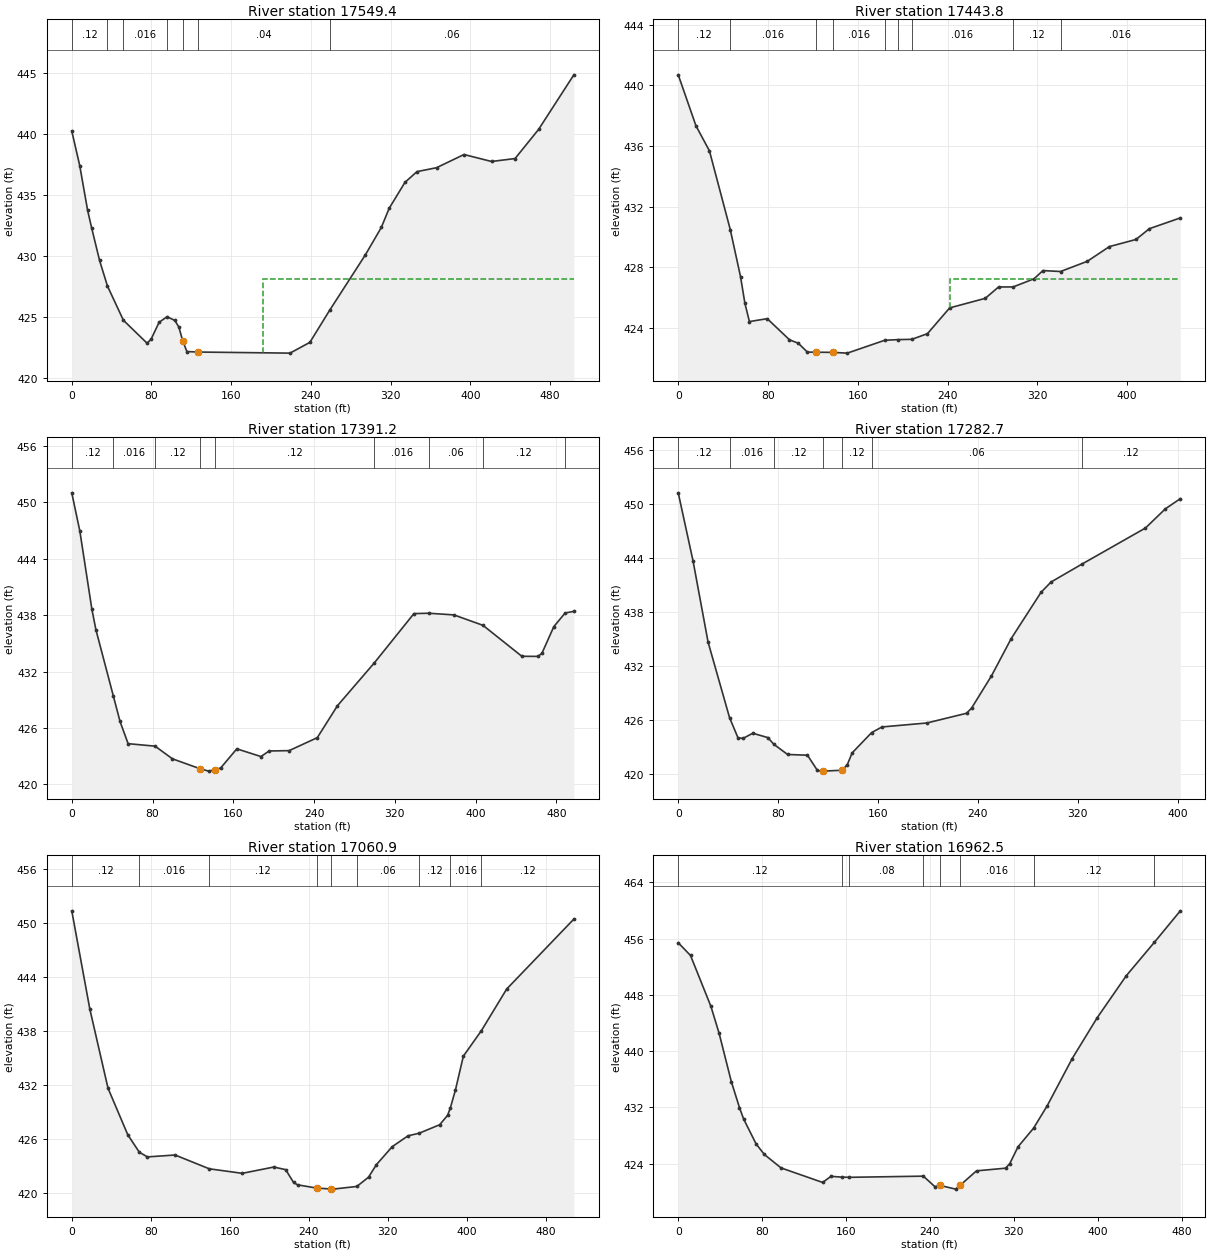
Type RM Length L Ch R = 1 ,17549.4 ,87.4,105.6,123.5
XS GIS Cut Line= 3
     2404071.353      386101.657     2404288.714      385837.074
     2404397.042      385717.421
#Sta/Elev= 30
       0  440.21       8  437.38    15.9  433.72    19.9   432.3    27.9  429.62
    35.8  427.53    51.8  424.73    75.6  422.85    79.6  423.18    87.6  424.56
    95.6  425.02   103.5  424.71   107.5  424.16   111.3  423.05   115.5  422.17
   126.3  422.13     219  422.04   238.9  422.92   258.8  425.55   294.6  430.08
   310.6  432.32   318.5  433.89   334.4  436.02   346.4  436.89     366  437.21
   393.6  438.29   421.2  437.72   444.8  437.96   468.4  440.34   503.8  444.81
#Mann= 7 ,-1 , 0
       0     .12       0    35.8     .06       0    51.8    .016       0
    95.6     .08       0   111.3    .045       0   126.3     .04       0
   258.8     .06       0
#XS Ineff= 2 , 0
                          191.78          428.07
Permanent Ineff=
       F       F
Bank Sta=111.3,126.3
XS Rating Curve= 0 ,0
Exp/Cntr=0.3,0.1

Type RM Length L Ch R = 1 ,17443.8 ,52.8,52.6,52.4
XS GIS Cut Line= 3
     2404074.935      386106.628     2404359.223      386081.671
     2404500.861      386003.185
#Sta/Elev= 30
       0  440.69    15.8  437.33    27.8  435.68   46.34430.4965    55.5  427.39
    59.4  425.63    63.4  424.43    79.3  424.62    99.1  423.23     107     423
     115  422.42   122.7  422.41   137.7   422.4   150.6  422.35  183.91423.1962
  195.37423.2388  208.09423.2599     222  423.63   241.8  425.33   273.5  425.96
   285.4  426.71  298.39426.7119     317  427.25   324.9  427.79  340.59427.7286
   364.4   428.4   384.1  429.37   407.8  429.84   419.7  430.55   447.3  431.26
#Mann= 9 ,-1 , 0
       0     .12       0   46.34    .016       0   122.7    .045       0
   137.7    .016       0  183.91     .04       0  195.37     .12       0
  208.09    .016       0  298.39     .12       0  340.59    .016       0
#XS Ineff= 2 , 0
                          241.98          427.24
Permanent Ineff=
       F       F
Bank Sta=122.7,137.7
XS Rating Curve= 0 ,0
Exp/Cntr=0.3,0.1

Type RM Length L Ch R = 1 ,17391.2 ,103.8,108.5,113.1
XS GIS Cut Line= 3
     2404077.105      386159.796     2404414.562      386128.329
     2404540.792      386032.699
#Sta/Elev= 30
       0  451.01       8  446.94    19.9  438.64    23.9  436.46    41.3429.3595
    47.8   426.7    55.8  424.34   82.52424.0745    99.7  422.73   126.9  421.68
   135.6  421.42   141.9  421.56   147.5  421.76   163.5  423.79   187.4  422.97
   195.4  423.56   215.3   423.6   243.2  424.98   263.2  428.38  299.59432.9182
   338.9  438.17   353.7438.2065   378.5  438.03  407.31436.9212   445.8  433.63
   461.6  433.62   465.6  433.93   477.5  436.79  488.69 438.235   497.3  438.41
#Mann= 9 ,-1 , 0
       0     .12       0    41.3    .016       0   82.52     .12       0
   126.9    .045       0   141.9     .12       0  299.59    .016       0
   353.7     .06       0  407.31     .12       0  488.69     .06       0
Bank Sta=126.9,141.9
XS Rating Curve= 0 ,0
Exp/Cntr=0.3,0.1

Type RM Length L Ch R = 1 ,17282.7 ,187.9,221.8,252.1
XS GIS Cut Line= 2
      2404072.62      386240.526     2404472.215      386285.303
#Sta/Elev= 30
       0  451.22    11.9  443.62    23.9  434.63   41.07426.2466    47.8  424.01
    51.8  423.92    59.7   424.5    71.7  424.02   76.72423.2552    87.6  422.14
   103.5  422.06   111.5  420.36   115.4  420.29   116.2  420.29   131.2  420.39
   135.4  421.01   139.3  422.32  154.94424.5797   163.2   425.2   199.1  425.64
   230.9  426.72   234.9  427.29   250.8  430.86   266.7  435.03   290.6  440.17
   298.6  441.31   323.2443.2888   374.2  447.31   390.2  449.45   402.1  450.57
#Mann= 7 ,-1 , 0
       0     .12       0   41.07    .016       0   76.72     .12       0
   116.2    .045       0   131.2     .12       0  154.94     .06       0
   323.2     .12       0
Bank Sta=116.2,131.2
XS Rating Curve= 0 ,0
Exp/Cntr=0.3,0.1

Type RM Length L Ch R = 1 ,17060.9 ,104.9,98.4,95.3
XS GIS Cut Line= 3
     2404062.204      386266.567     2404098.662      386270.474
     2404271.839      386709.276
#Sta/Elev= 30
       0  451.38    18.3  440.43    36.7  431.62    56.7  426.44   68.38424.4926
    76.6  423.97   104.6  424.18  139.26422.6436   172.6  422.14   204.6  422.84
   216.6  422.55   224.6  421.12   228.6  420.86   247.9   420.5   262.9  420.39
   264.5  420.38  288.69420.6795   300.5  421.71   308.5  423.11   324.5  425.11
   340.5  426.32  351.74426.6062   372.5  427.55   380.5  428.59  383.26429.3904
   388.5  431.42   396.5  435.19  414.79 438.035   440.4  442.67   508.4  450.46
#Mann= 9 ,-1 , 0
       0     .12       0   68.38    .016       0  139.26     .12       0
   247.9    .045       0   262.9     .12       0  288.69     .06       0
  351.74     .12       0  383.26    .016       0  414.79     .12       0
Bank Sta=247.9,262.9
XS Rating Curve= 0 ,0
Exp/Cntr=0.3,0.1

Type RM Length L Ch R = 1 ,16962.5 ,275,262.7,250.6
XS GIS Cut Line= 3
     2404016.631      386342.088     2404062.938      386383.787
     2404223.662      386767.869
#Sta/Elev= 30
       0  455.42    11.7  453.61    31.2  446.35      39  442.52    50.6  435.67
    58.4  431.96    62.3  430.36    74.2  426.81    82.1   425.3      98  423.39
   137.7  421.32   145.6  422.19  155.67422.0817  163.22422.0509  233.73422.2156
   244.7  420.72   249.5   420.9   264.5  420.37   268.5  420.89   284.4  422.97
   312.1  423.35   316.1     424     324   426.4  338.79429.0397   351.8  432.23
   375.6  438.94   399.4  444.74   427.1  450.71  453.99455.4858   478.7  459.96
#Mann= 8 ,-1 , 0
       0     .12       0  155.67    .016       0  163.22     .08       0
  233.73    .016       0   249.5    .045       0   268.5    .016       0
  338.79     .12       0  453.99     .06       0
Bank Sta=249.5,268.5
XS Rating Curve= 0 ,0
Exp/Cntr=0.3,0.1

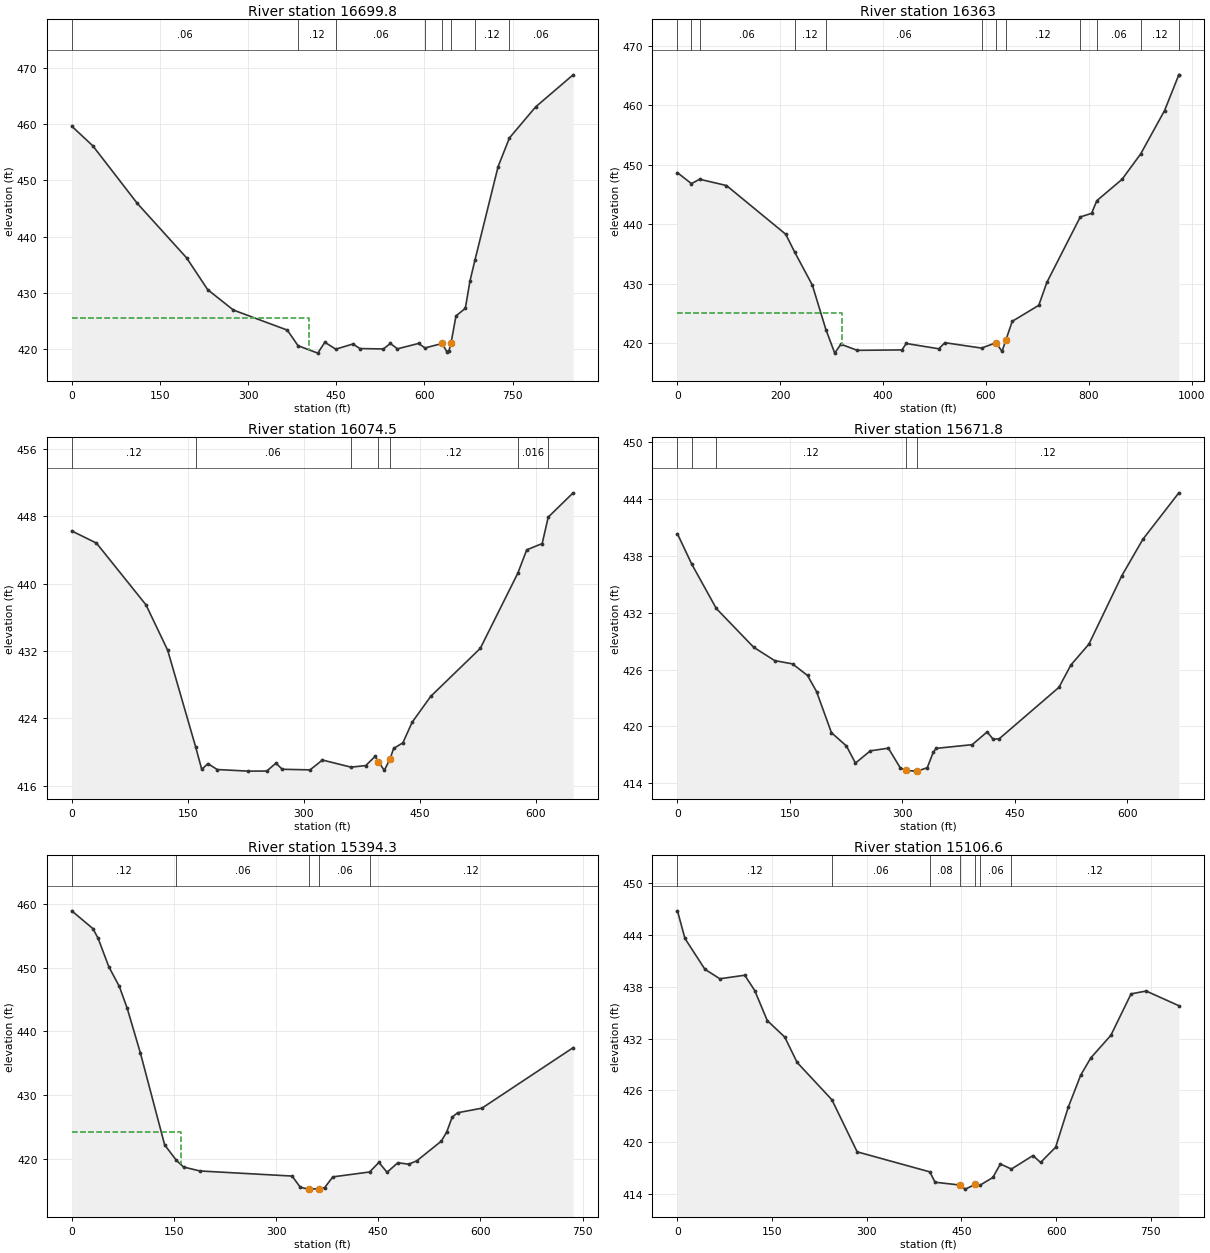
Type RM Length L Ch R = 1 ,16699.8 ,345,336.8,328.4
XS GIS Cut Line= 3
     2403712.174      386256.117     2403691.213      386486.457
     2404134.049      386922.784
#Sta/Elev= 30
       0  459.62    35.9  456.13   111.7   445.9   195.4  436.26   231.3  430.61
   275.1  426.99   366.8  423.43     385420.6673   418.6  419.35   430.6  421.28
  449.19420.0536   478.4  420.97   490.3  420.16   530.2  420.09   542.1  421.07
   554.1  420.11     590  421.07  600.98 420.269   630.4  421.07   637.8  419.63
   641.8  419.81   645.4  421.19   653.7  425.95   669.6   427.3   677.6  432.19
  686.03435.8813   725.4  452.46  744.62457.5279   789.2  463.04     853  468.73
#Mann= 8 ,-1 , 0
       0     .06       0     385     .12       0  449.19     .06       0
  600.98     .12       0   630.4    .045       0   645.4    .016       0
  686.03     .12       0  744.62     .06       0
#XS Ineff= 2 , 0
          403.08  425.61
Permanent Ineff=
       F       F
Bank Sta=630.4,645.4
XS Rating Curve= 0 ,0
Exp/Cntr=0.3,0.1

Type RM Length L Ch R = 1 ,16363   ,300.4,288.5,276.4
XS GIS Cut Line= 4
     2403173.112      386980.075      2403389.13      386845.832
     2403811.132      387029.554     2404071.549      387024.346
#Sta/Elev= 30
       0  448.65   27.26446.8089   43.12  447.55    95.4  446.49   210.6  438.31
  227.76 435.353   262.3  429.78  288.73422.3078   305.9  418.35   317.8  419.85
   349.6  418.82   436.8  418.89   444.8  419.97   508.3  419.08   520.2   420.1
  591.34419.1994   619.4  420.09   631.3  418.64   638.8  420.57   651.1  423.69
   702.7  426.38   718.5  430.24  783.42441.2149   805.4  441.82  815.62443.9459
   864.6  447.53  900.93451.8007   947.4  459.09  974.61464.9832   975.1  465.08
#Mann= 12 ,-1 , 0
       0     .06       0   27.26     .12       0   43.12     .06       0
  227.76     .12       0  288.73     .06       0  591.34     .12       0
   619.4    .045       0   638.8     .12       0  783.42    .016       0
  815.62     .06       0  900.93     .12       0  974.61     .06       0
#XS Ineff= 2 , 0
          319.64  425.15
Permanent Ineff=
       F       F
Bank Sta=619.4,638.8
XS Rating Curve= 0 ,0
Exp/Cntr=0.3,0.1

Type RM Length L Ch R = 1 ,16074.5 ,396.1,402.7,407.1
XS GIS Cut Line= 2
     2403347.842       387294.99     2403992.485      387229.573
#Sta/Elev= 30
       0  446.28      32  444.83      96  437.49     124   432.1  160.08420.6318
     168  417.94     176  418.62     188  417.92     228  417.73     252  417.74
     264  418.68     272  417.95     308  417.88     324  419.05  360.88418.2044
     380  418.39     392  419.48   396.3  418.85     404  417.82   411.3  419.17
     416  420.42     428   421.1     440  423.55     464  426.62     528  432.32
  576.44441.2423     588  444.03     608  444.78  615.81447.9173     648  450.81
#Mann= 7 ,-1 , 0
       0     .12       0  160.08     .06       0  360.88     .12       0
   396.3    .045       0   411.3     .12       0  576.44    .016       0
  615.81     .06       0
Bank Sta=396.3,411.3
XS Rating Curve= 0 ,0
Exp/Cntr=0.3,0.1

Type RM Length L Ch R = 1 ,15671.8 ,281.1,277.4,273.7
XS GIS Cut Line= 4
     2403326.757      387474.867     2403402.278      387493.096
     2403864.825      387601.474     2403936.439       387692.62
#Sta/Elev= 30
       0   440.3   19.02437.1138   51.81432.4322   101.6  428.35   129.6  426.94
   153.5  426.59   173.5  425.37   185.5  423.68   205.4  419.34   225.4  417.94
   237.4  416.14   257.3  417.43   281.3  417.71   297.3  415.62     305  415.37
   317.2  415.29     320   415.3   333.2  415.65   341.2  417.29   345.2  417.69
   393.1  418.08     413  419.42     421  418.66     429  418.69   508.8  424.12
   524.8  426.48   548.8  428.68   592.7  435.89   620.7  439.72   668.7  444.62
#Mann= 5 ,-1 , 0
       0     .12       0   19.02     .06       0   51.81     .12       0
     305    .045       0     320     .12       0
Bank Sta=305,320
XS Rating Curve= 0 ,0
Exp/Cntr=0.3,0.1

Type RM Length L Ch R = 1 ,15394.3 ,296.6,287.7,278.4
XS GIS Cut Line= 4
     2403203.366      387837.151     2403307.533      387785.068
     2403788.111      387820.028     2403876.543      387925.693
#Sta/Elev= 30
       0  458.91    31.1  456.12    38.8  454.58    54.4  450.15    69.9  447.04
    81.5   443.6   100.9  436.57   136.4   422.2  153.32419.8048   164.2  418.72
   188.1   418.1   323.5   417.3   335.5  415.55   347.4  415.25   348.5  415.26
   363.5  415.31   371.3  415.48   383.3  417.17  437.29417.9406     451  419.44
   462.9  417.89   478.8  419.39   494.8  419.16   506.7   419.7   542.6  422.78
   550.5  424.21   558.5  426.53   566.4  427.23   602.2  427.95   736.1  437.44
#Mann= 5 ,-1 , 0
       0     .12       0  153.32     .06       0   348.5    .045       0
   363.5     .06       0  437.29     .12       0
#XS Ineff= 2 , 0
          160.21  424.29
Permanent Ineff=
       F       F
Bank Sta=348.5,363.5
XS Rating Curve= 0 ,0
Exp/Cntr=0.3,0.1

Type RM Length L Ch R = 1 ,15106.6 ,257.4,247.7,238.3
XS GIS Cut Line= 4
     2403101.804      388110.589     2403346.595      388156.162
     2403754.147      388019.443     2403868.731      388035.068
#Sta/Elev= 30
       0   446.8    11.9   443.6    43.5  440.03    67.2  438.93   106.7  439.34
   122.5  437.56   142.3  434.09     170  432.18   189.7  429.23   244.7424.9177
   284.8  418.88  399.95416.5582   408.2  415.36     448  415.03     456  414.56
   471.9   415.1  478.79414.9852   499.8  415.91   511.7  417.47  529.26416.8879
   563.4  418.45   575.4  417.65   599.3  419.42   619.2  424.03   639.1  427.78
     655  429.76   686.8  432.38   718.8  437.18   742.7  437.51   794.5  435.81
#Mann= 7 ,-1 , 0
       0     .12       0   244.7     .06       0  399.95     .08       0
     448    .045       0   471.9     .08       0  478.79     .06       0
  529.26     .12       0
Bank Sta=448,471.9
XS Rating Curve= 0 ,0
Exp/Cntr=0.3,0.1

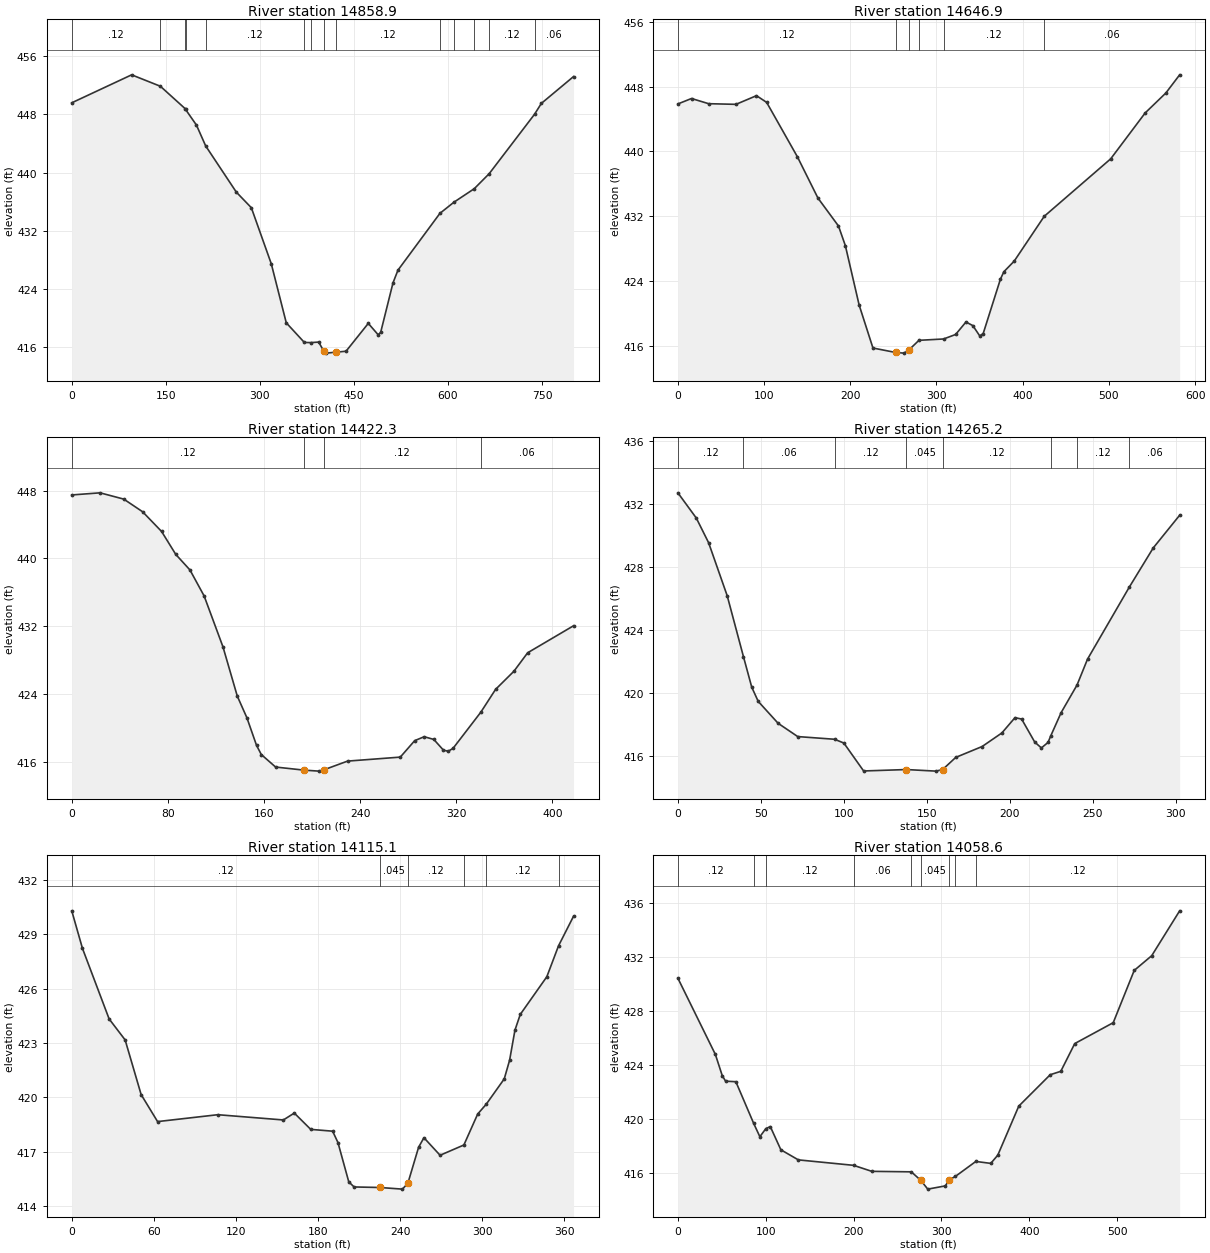
Type RM Length L Ch R = 1 ,14858.9 ,204,212,219.8
XS GIS Cut Line= 4
     2403408.818      388558.158     2403710.045      388274.633
     2403852.448      388143.842       2404036.7      388085.849
#Sta/Elev= 30
       0  449.59    95.5  453.44  141.32451.8688  180.66448.7993  181.43448.6876
   198.9  446.52  213.59443.6569   262.5   437.3   286.4  435.16   318.2  427.45
   342.1  419.33  370.93416.6297  381.41 416.606   393.8  416.68   401.7  415.47
   405.7  415.16   421.2  415.29   437.4  415.42   472.9  419.25   488.6  417.69
   492.6     418   512.3  424.82   520.2  426.57   587.2434.3908  609.57435.9249
  641.92437.7784  665.67439.8384  738.06448.0182   748.9  449.51   800.2   453.2
#Mann= 14 ,-1 , 0
       0     .12       0  141.32     .06       0  180.66     .12       0
  181.43     .06       0  213.59     .12       0  370.93     .06       0
  381.41     .12       0   401.7    .045       0   421.2     .12       0
   587.2     .06       0  609.57     .12       0  641.92     .06       0
  665.67     .12       0  738.06     .06       0
Bank Sta=401.7,421.2
XS Rating Curve= 0 ,0
Exp/Cntr=0.3,0.1

Type RM Length L Ch R = 1 ,14646.9 ,223,224.5,226
XS GIS Cut Line= 3
      2403615.82      388605.075     2403746.335      388477.776
     2404114.825      388322.828
#Sta/Elev= 30
       0  445.85    15.8  446.52    35.7  445.88    67.4   445.8    91.2  446.87
     103  446.04   138.7  439.32   162.5  434.24   186.3   430.8   194.3  428.37
   210.3  421.04   226.3  415.75   252.6   415.2   262.3  415.12   267.6  415.47
  279.65416.6991  308.23416.8648   322.2  417.42   334.2  418.96   342.2  418.51
   350.2  417.24   354.2  417.54   374.2  424.25   378.2  425.16   390.2  426.47
  425.01431.9937   502.1  439.08   542.1  444.74   566.1   447.2   582.1  449.44
#Mann= 6 ,-1 , 0
       0     .12       0   252.6    .045       0   267.6     .12       0
  279.65     .06       0  308.23     .12       0  425.01     .06       0
Bank Sta=252.6,267.6
XS Rating Curve= 0 ,0
Exp/Cntr=0.3,0.1

Type RM Length L Ch R = 1 ,14422.3 ,150.3,157.2,164
XS GIS Cut Line= 4
     2403701.757       388651.95     2403828.193      388681.492
     2404028.193      388612.742     2404077.498      388554.408
#Sta/Elev= 30
       0  447.48    23.6  447.73    43.3  446.99      59   445.5    74.8  443.18
    86.6  440.48    98.4  438.65   110.2  435.59   125.9  429.59   137.8   423.8
   145.8  421.25   153.8  418.01   157.8  416.92   169.7  415.45   193.1  415.09
   205.7  414.97   209.6  415.11   229.6  416.15   273.5  416.62   285.5  418.56
   293.4  419.02   301.4   418.7   309.4  417.44   313.4  417.31   317.4  417.65
  340.57421.9148   352.8  424.59   368.1  426.73   379.5   428.9   417.7  432.08
#Mann= 4 ,-1 , 0
       0     .12       0   193.1    .045       0   209.6     .12       0
  340.57     .06       0
Bank Sta=193.1,209.6
XS Rating Curve= 0 ,0
Exp/Cntr=0.3,0.1

Type RM Length L Ch R = 1 ,14265.2 ,150.1,150.1,150.1
XS GIS Cut Line= 3
     2403803.193      388798.853      2403846.23      388810.118
     2404103.887       388801.63
#Sta/Elev= 30
       0   432.7    11.1   431.1    18.5  429.54    29.7  426.18   39.52422.3097
    44.5  420.38    48.4  419.48    60.4  418.09    72.2  417.25    94.4417.0795
     100  416.84   111.9  415.07   137.7  415.16   155.5  415.06   159.5  415.16
   167.4  415.93   183.3  416.62   195.2  417.48   203.1  418.45   207.1  418.36
     215   416.9     219  416.53     223  416.88  224.74417.3172   230.9  418.77
  240.47420.5158   246.8  422.16  271.95426.7219   286.4  429.21   302.3  431.28
#Mann= 8 ,-1 , 0
       0     .12       0   39.52     .06       0    94.4     .12       0
   137.7    .045       0   159.5     .12       0  224.74     .06       0
  240.47     .12       0  271.95     .06       0
Bank Sta=137.7,159.5
XS Rating Curve= 0 ,0
Exp/Cntr=0.3,0.1

Type RM Length L Ch R = 1 ,14115.1 ,61,56.5,52
XS GIS Cut Line= 5
     2403791.387      388834.269     2403817.082      388878.019
     2403933.748      388955.103     2404035.832      388952.325
     2404104.582      388925.242
#Sta/Elev= 30
       0   430.3     7.8  428.23    27.3  424.33      39  423.17    50.7  420.15
    62.7  418.66   106.7  419.04   154.6  418.75   162.6  419.13   174.6  418.23
   190.6  418.13   194.5   417.5   202.4  415.33   206.3  415.05   225.2  415.02
   241.6  414.93   245.6  415.26   253.4  417.24   257.3  417.77   269.1   416.8
  286.49417.3674   296.6  419.08  302.82419.6187     316  421.02   319.9  422.05
   323.8  423.71   327.7  424.58   347.1  426.66  355.65428.3692   366.6     430
#Mann= 6 ,-1 , 0
       0     .12       0   225.2    .045       0   245.6     .12       0
  286.49     .06       0  302.82     .12       0  355.65     .06       0
Bank Sta=225.2,245.6
XS Rating Curve= 0 ,0
Exp/Cntr=0.3,0.1

Type RM Length L Ch R = 1 ,14058.6 ,77.5,76.2,75.1
XS GIS Cut Line= 4
     2403756.404      388852.499     2403787.871      388936.049
     2403957.359      389015.519     2404244.686      388950.155
#Sta/Elev= 30
       0  430.45    42.7  424.79    50.5  423.22    54.3  422.81      66  422.77
   86.11419.7008    93.3  418.69  100.16419.2932   105.2  419.44   117.2  417.72
   137.1  416.97  199.95416.5658   220.7  416.12  265.66416.0833   276.5  415.45
   284.4   414.8   304.4  415.04   308.7  415.48  315.82415.7428  339.12416.8541
   356.1  416.71   364.1  417.32     388  420.96   423.8  423.29   435.8  423.54
   451.7   425.6   495.5  427.15   519.4  431.03   539.3  432.12   571.1  435.45
#Mann= 9 ,-1 , 0
       0     .12       0   86.11     .06       0  100.16     .12       0
  199.95     .06       0  265.66     .12       0   276.5    .045       0
   308.7     .12       0  315.82     .06       0  339.12     .12       0
Bank Sta=276.5,308.7
XS Rating Curve= 0 ,0
Exp/Cntr=0.3,0.1