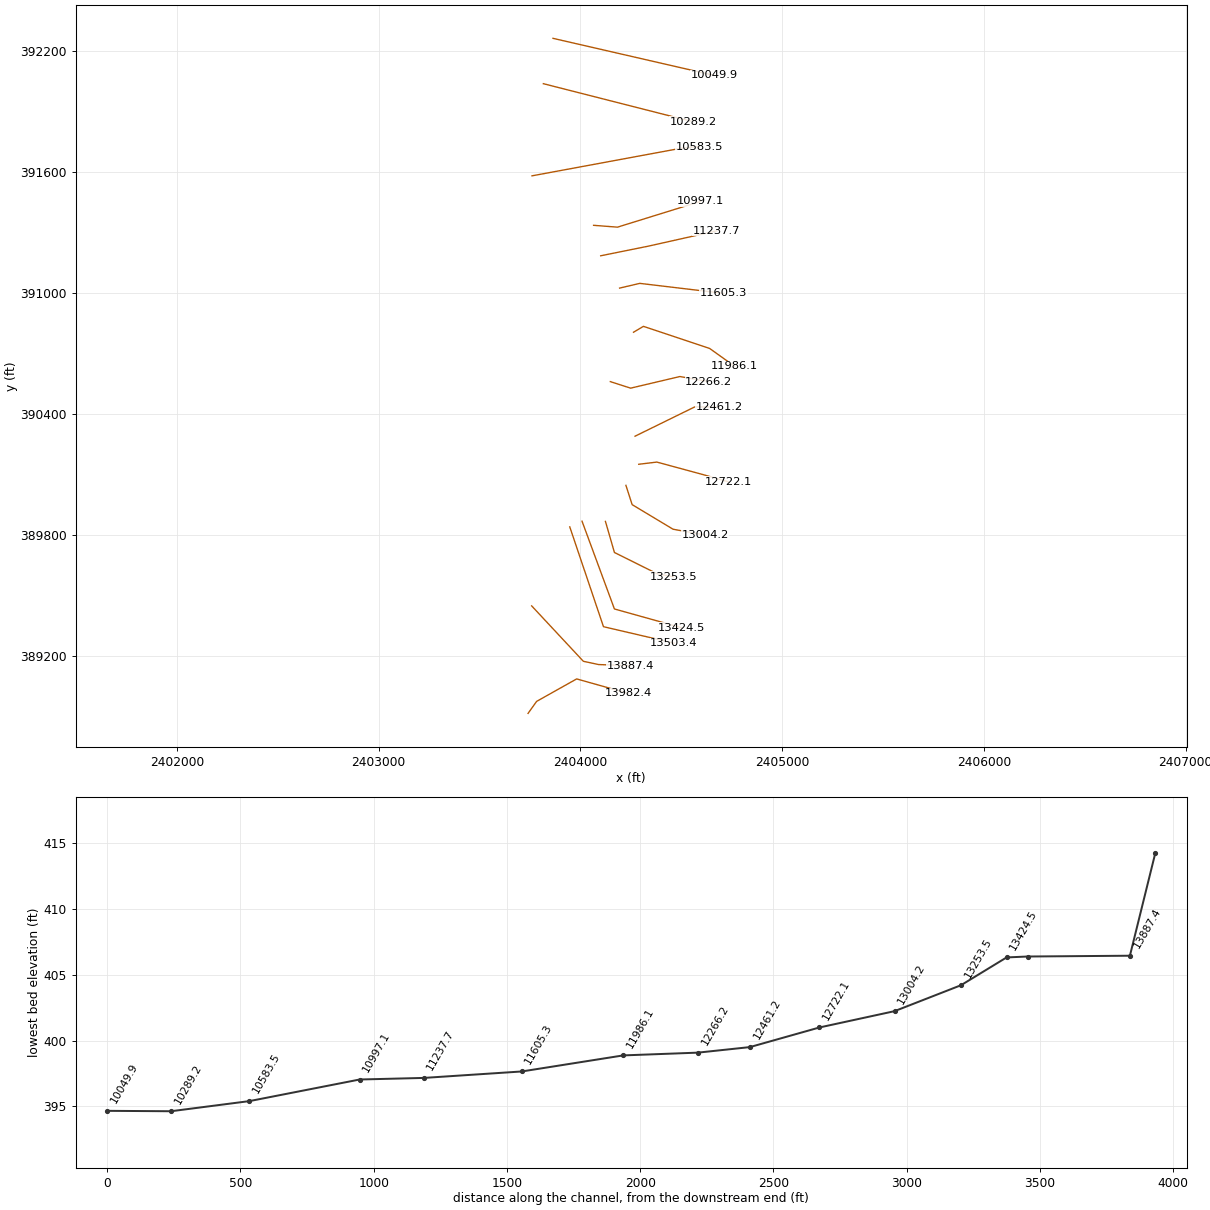
HEC-RAS study HARLANRUN.prj: HARLANRUN

--- HARLANRUN.g01 (geometry) --- (continued)

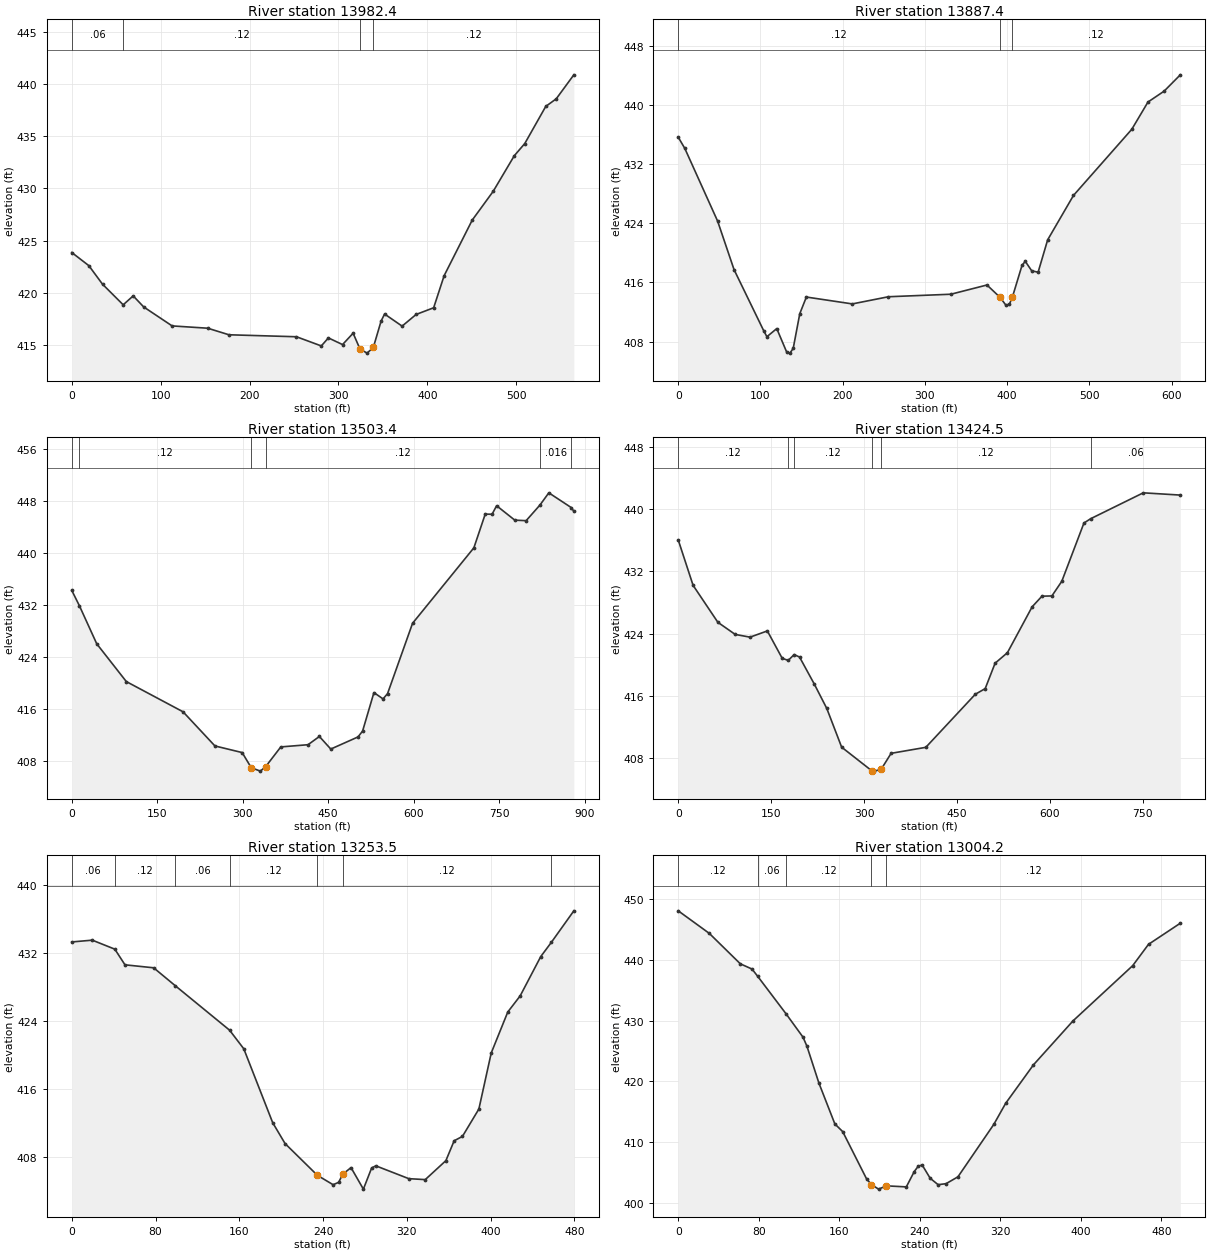
Type RM Length L Ch R = 1 ,13982.4 ,93.5,95,96.3
XS GIS Cut Line= 4
     2403740.693      388917.603      2403783.01      388977.021
     2403981.665      389088.436     2404235.832      389016.908
#Sta/Elev= 30
       0  423.86    19.2   422.6    34.6  420.82   57.85418.8437    69.1   419.7
    80.9  418.64   112.9  416.82   152.9   416.6   176.8  415.97   252.8  415.78
   280.7   414.9   288.7  415.67   304.6  415.03   316.5  416.12   324.2  414.61
   332.2  414.21   339.2  414.75     348  417.29   351.9  417.96   371.6   416.8
   387.4  417.92   407.1  418.56   418.9  421.64   450.5  426.97   474.1  429.73
   497.8  433.14   509.6  434.31   533.2  437.87     545   438.6   564.8   440.9
#Mann= 4 ,-1 , 0
       0     .06       0   57.85     .12       0   324.2    .045       0
   339.2     .12       0
Bank Sta=324.2,339.2
XS Rating Curve= 0 ,0
Exp/Cntr=0.3,0.1

Type RM Length L Ch R = 1 ,13887.4 ,407.2,383.9,192.1
XS GIS Cut Line= 4
     2403758.575      389450.372     2404014.651      389175.849
     2404090.606      389159.573     2404247.941      389154.148
#Sta/Elev= 30
       0  435.66       8  434.14    47.9   424.3    67.9  417.73   103.8   409.5
   107.8  408.66   119.8  409.76   131.8   406.6   135.8  406.44   139.8  407.08
   147.8  411.78   155.8  414.03   211.7   413.1   255.6  414.07   331.5  414.41
   375.4  415.66   391.3  413.99   398.7  412.89   402.6  413.04   406.3  414.01
   418.1  418.34     422  418.86   429.8  417.58   437.6  417.39   449.2  421.77
   480.6  427.78   551.5  436.73   571.2  440.42   590.8  441.89   610.5   444.1
#Mann= 3 ,-1 , 0
       0     .12       0   391.3    .045       0   406.3     .12       0
Bank Sta=391.3,406.3
XS Rating Curve= 0 ,0
Exp/Cntr=0.3,0.1

Type RM Length L Ch R = 1 ,13503.4 ,78.4,78.9,246.5
XS GIS Cut Line= 3
     2403947.377      389842.082     2404114.477       389347.29
      2404463.87       389265.91
#Sta/Elev= 30
       0  434.23   13.48 431.844    43.8     426    95.7  420.18   195.3  415.52
   251.2  410.26     299  409.24   314.9  406.91   330.9  406.38   340.1  407.06
   366.8  410.11   414.6  410.45   434.5  411.72   454.5  409.78   502.3  411.65
   510.3  412.55   530.2  418.48   546.2  417.51   554.1  418.32     598  429.16
   705.6  440.79   725.5  445.98   737.5  445.96   745.5  447.27   777.4  445.05
   797.3  444.97  821.54447.3795   837.1  449.26  876.88446.9632     881   446.4
#Mann= 6 ,-1 , 0
       0    .016       0   13.48     .12       0   314.9    .045       0
   340.1     .12       0  821.54    .016       0  876.88     .12       0
Bank Sta=314.9,340.1
XS Rating Curve= 0 ,0
Exp/Cntr=0.3,0.1

Type RM Length L Ch R = 1 ,13424.5 ,153,171,189
XS GIS Cut Line= 3
     2404008.141      389870.294     2404168.731      389435.181
     2404502.932      389341.865
#Sta/Elev= 30
       0  436.04      24   430.2      64  425.45      92  423.89     116  423.54
   143.9  424.34   167.9  420.82  177.65420.5519  187.19421.2979   195.9  420.98
   219.9  417.48   239.9  414.37   263.9  409.39   312.5  406.36   315.9  406.31
   327.5  406.52   343.8   408.6   399.8  409.37   479.8   416.2   495.7  416.92
   511.7  420.19   531.6  421.54   571.5  427.44   587.4  428.81   603.4  428.84
   619.4  430.72   655.2  438.22  666.04438.7713     751   442.1   810.8  441.81
#Mann= 6 ,-1 , 0
       0     .12       0  177.65     .06       0  187.19     .12       0
   312.5    .045       0   327.5     .12       0  666.04     .06       0
Bank Sta=312.5,327.5
XS Rating Curve= 0 ,0
Exp/Cntr=0.3,0.1

Type RM Length L Ch R = 1 ,13253.5 ,251.1,249.4,247.8
XS GIS Cut Line= 4
     2404124.243      389869.209     2404168.731      389715.129
     2404380.319      389609.877       2404461.7      389594.686
#Sta/Elev= 30
       0  433.27    19.6  433.48   41.13432.4203    50.8  430.58    78.2  430.23
   98.94428.1131  150.72422.8938   164.3   420.7   191.9  412.01   203.7  409.56
   234.6  405.82   249.6  404.72   254.9     405   258.8  405.96   266.7  406.73
   278.5   404.2   286.4  406.69   290.4  406.94   321.9  405.43   337.6  405.32
   357.3  407.55   365.2  409.89   373.1   410.4   388.8  413.62   400.6  420.21
   416.4  425.03   428.2  426.92   447.9  431.55  458.12433.2416   479.5  436.93
#Mann= 7 ,-1 , 0
       0     .06       0   41.13     .12       0   98.94     .06       0
  150.72     .12       0   234.6    .045       0   258.8     .12       0
  458.12     .06       0
Bank Sta=234.6,258.8
XS Rating Curve= 0 ,0
Exp/Cntr=0.3,0.1

Type RM Length L Ch R = 1 ,13004.2 ,275.7,282,288
XS GIS Cut Line= 4
     2404225.805      390047.811     2404256.549      389952.352
      2404459.57      389830.336     2404618.601        389801.5
#Sta/Elev= 30
       0  448.07    30.9  444.35    61.7  439.34    73.3  438.48   78.89437.2945
  107.06431.1193     124  427.25   127.9  425.75   139.8  419.68   155.6  412.97
   163.4   411.7   187.1  403.92   191.9  402.99     199  402.23   206.9  402.77
   226.6   402.6   234.5  405.13   238.5  406.02   242.4  406.19   250.3  404.02
   258.2  402.96   266.1  403.13   277.9  404.26   313.5  412.89   325.3  416.37
   352.9   422.7   392.3  429.96   451.5  439.04   467.2  442.55   498.8  446.03
#Mann= 5 ,-1 , 0
       0     .12       0   78.89     .06       0  107.06     .12       0
   191.9    .045       0   206.9     .12       0
Bank Sta=191.9,206.9
XS Rating Curve= 0 ,0
Exp/Cntr=0.3,0.1

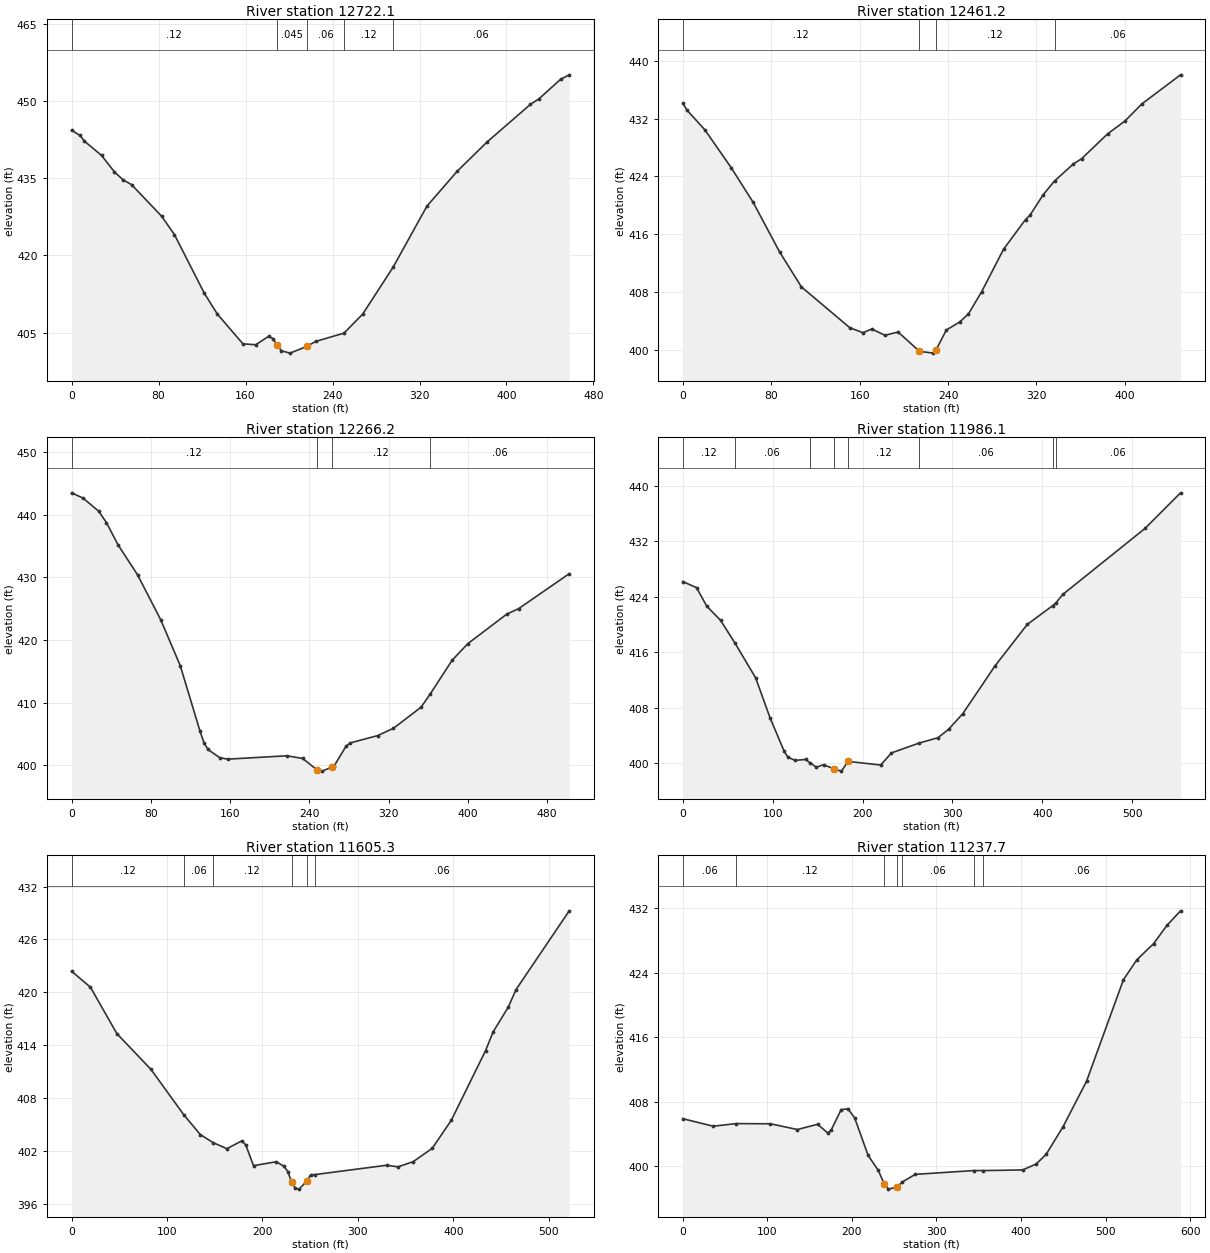
Type RM Length L Ch R = 1 ,12722.1 ,244.4,261,277.1
XS GIS Cut Line= 4
     2404289.174      390152.412     2404379.234      390163.262
     2404607.099      390101.413     2404732.967      390065.606
#Sta/Elev= 30
       0  444.34     7.9  443.32    11.8  442.23    27.6  439.44    39.4  436.25
    47.3  434.71    55.2  433.76    82.8  427.63    94.6  424.05   122.2   412.6
     134  408.61   157.6   402.8   169.4  402.62   181.2  404.26   185.2  403.81
   189.1  402.56     193  401.45   200.9  400.99   216.4  402.29   224.5  403.27
  250.52 404.873   267.8  408.59  295.91417.7696   326.8  429.57   354.6  436.35
   382.3  442.09     422  449.37   429.9  450.46   449.8  454.26   457.7  455.12
#Mann= 5 ,-1 , 0
       0     .12       0   189.1    .045       0   216.4     .06       0
  250.52     .12       0  295.91     .06       0
Bank Sta=189.1,216.4
XS Rating Curve= 0 ,0
Exp/Cntr=0.3,0.1

Type RM Length L Ch R = 1 ,12461.2 ,200,194.9,189.8
XS GIS Cut Line= 3
     2404270.944      390291.518     2404567.168      390436.917
     2404687.611      390435.832
#Sta/Elev= 30
       0  434.11       4  433.14    19.9  430.46    43.7  425.22    63.6  420.41
    87.5  413.54   107.3  408.68   151.1  403.02     163  402.33     171  402.85
   182.9  401.97   194.8  402.43   214.1  399.75   226.6   399.5   229.1  399.95
   238.5  402.71   250.5  403.81   258.4  404.92   270.4  408.01   290.2  413.89
   310.1  418.02   314.1   418.6     326  421.44  336.42423.3723   353.3  425.71
   361.1  426.48   384.4   429.9   399.9  431.65   415.5  434.06   450.4  438.08
#Mann= 4 ,-1 , 0
       0     .12       0   214.1    .045       0   229.1     .12       0
  336.42     .06       0
Bank Sta=214.1,229.1
XS Rating Curve= 0 ,0
Exp/Cntr=0.3,0.1

Type RM Length L Ch R = 1 ,12266.2 ,292.8,280.1,267.3
XS GIS Cut Line= 4
     2404148.372      390562.106     2404248.986      390529.725
     2404493.317      390587.302     2404636.653      390562.106
#Sta/Elev= 30
       0  443.48    11.7  442.63    27.4  440.55    35.2  438.73      47  435.16
    66.6   430.4      90  423.22   109.7   415.9   129.6  405.47   133.6  403.62
   137.6  402.54   149.5  401.23   157.5  400.99   217.3  401.53   233.2   401.1
   247.5  399.31   253.1  399.08   262.5  399.73   265.1  399.93     277  403.06
     281  403.57   308.9  404.75   324.8  405.91   352.7  409.28  362.15411.4404
   384.2  416.81     400  419.43   439.3  424.14   451.1     425   502.2  430.58
#Mann= 4 ,-1 , 0
       0     .12       0   247.5    .045       0   262.5     .12       0
  362.15     .06       0
Bank Sta=247.5,262.5
XS Rating Curve= 0 ,0
Exp/Cntr=0.3,0.1

Type RM Length L Ch R = 1 ,11986.1 ,369,380.8,383.6
XS GIS Cut Line= 4
     2404263.349      390806.926     2404312.558      390836.065
     2404640.656      390726.553     2404763.349      390638.957
#Sta/Elev= 30
       0  426.18    15.2  425.31    26.7  422.62    41.9  420.61   57.68 417.388
      81  412.31      97  406.56   112.8  401.72   116.8  400.89   124.8  400.42
   136.7  400.55  141.09400.0961   148.6  399.44   156.6  399.79   168.7  399.18
   176.5  398.87   183.7  400.27   220.2  399.75   232.1  401.49  262.61402.9039
   283.8  403.68   295.7  404.89   311.6  407.17   347.4  414.04   383.2     420
  411.34422.6966  414.85423.0739   422.9  424.34   514.2  433.83   553.8  438.97
#Mann= 8 ,-1 , 0
       0     .12       0   57.68     .06       0  141.09     .12       0
   168.7    .045       0   183.7     .12       0  262.61     .06       0
  411.34     .12       0  414.85     .06       0
Bank Sta=168.7,183.7
XS Rating Curve= 0 ,0
Exp/Cntr=0.3,0.1

Type RM Length L Ch R = 1 ,11605.3 ,357.1,367.6,374.1
XS GIS Cut Line= 3
     2404194.338      391025.676     2404294.599      391049.113
     2404709.963      390999.634
#Sta/Elev= 30
       0  422.39    19.8  420.57    47.5   415.3    83.2  411.24  117.39406.1174
   134.8  403.85   148.3402.9262   162.7  402.24   178.7  403.15   182.6  402.63
   190.6  400.31   214.5  400.76   222.5  400.24   226.5  399.65   230.4  398.48
   234.4  397.73   238.4  397.65   246.4  398.58   250.4  399.27  255.13399.3037
     330  400.36     342  400.18   357.9  400.77   377.8  402.28   397.8  405.47
   433.6  413.36   441.6   415.5   457.5  418.32   465.5  420.29   521.3  429.24
#Mann= 6 ,-1 , 0
       0     .12       0  117.39     .06       0   148.3     .12       0
   230.4    .045       0   246.4     .12       0  255.13     .06       0
Bank Sta=230.4,246.4
XS Rating Curve= 0 ,0
Exp/Cntr=0.3,0.1

Type RM Length L Ch R = 1 ,11237.7 ,238.5,240.6,242.9
XS GIS Cut Line= 3
     2404100.588      391185.832      2404338.87      391234.009
     2404676.109       391309.53
#Sta/Elev= 30
       0  405.89    35.9  404.96      63 405.284   103.6  405.26   135.5  404.55
   159.4   405.2   171.4  404.12   175.4  404.48   187.3  407.02   195.3  407.12
   203.2     406   219.2  401.33   231.2  399.48   238.3  397.78   243.1  397.16
   253.3  397.42  259.59398.0464   274.9  398.99   344.4 399.465   355.1 399.458
     402  399.54   417.9  400.27   429.8  401.48   449.7  404.89   477.5  410.53
   521.2  423.13     537  425.59   556.9   427.6   572.8  429.88   588.7  431.66
#Mann= 7 ,-1 , 0
       0     .06       0      63     .12       0   238.3    .045       0
   253.3     .12       0  259.59     .06       0   344.4     .12       0
   355.1     .06       0
Bank Sta=238.3,253.3
XS Rating Curve= 0 ,0
Exp/Cntr=0.3,0.1

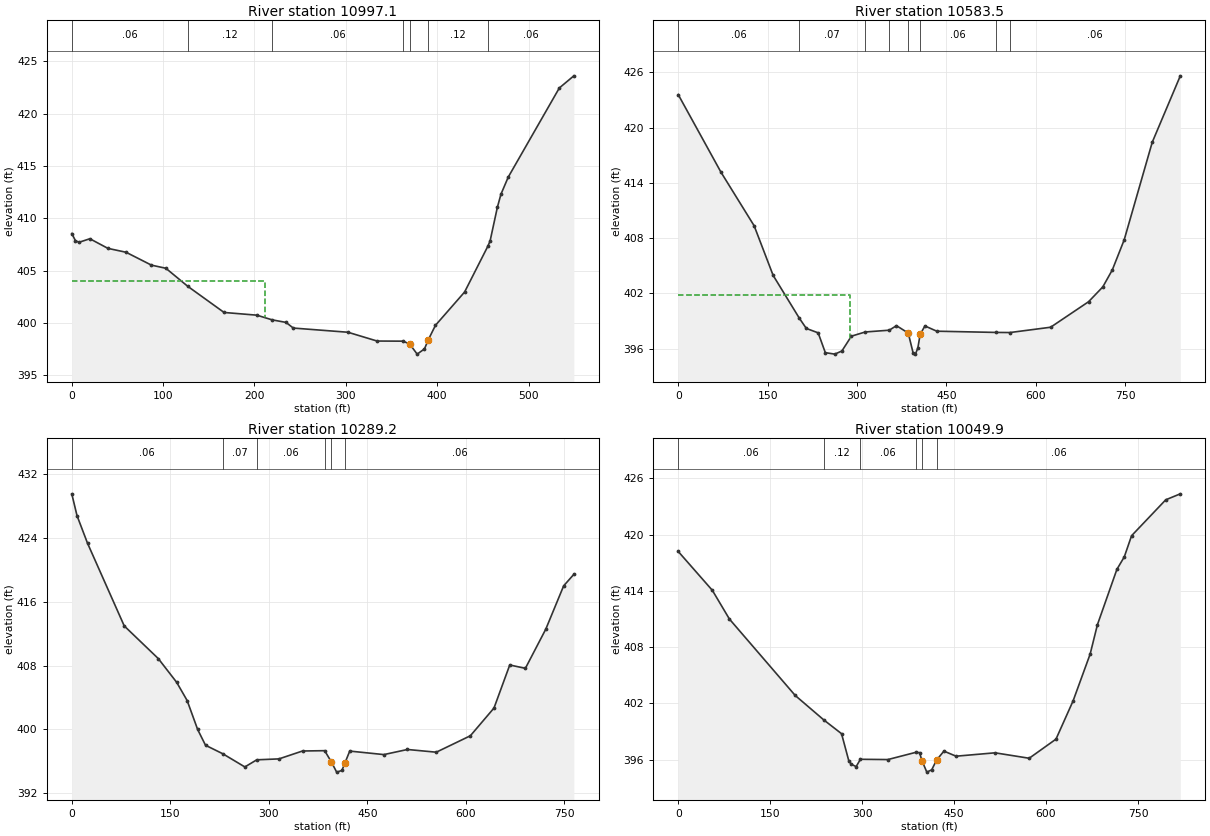
Type RM Length L Ch R = 1 ,10997.1 ,416,413.6,411
XS GIS Cut Line= 3
     2404065.432      391336.874     2404183.922      391327.759
      2404595.38      391455.363
#Sta/Elev= 30
       0  408.56       4  407.88     7.9  407.72    19.8  408.06    39.6  407.14
    59.4  406.77    87.2  405.54     103  405.24  126.91403.5209   166.7  401.02
   202.6  400.76   219.4 400.312   234.5  400.07   242.5  399.53   302.3  399.13
   334.2  398.29     363 398.278   370.1  397.98   378.1  397.04   386.1  397.54
   390.1  398.38   398.1  399.79     430  402.97  455.43407.3398   457.9  407.84
   465.9  411.07   469.8  412.31   477.8  413.95   533.7  422.46   549.6  423.62
#Mann= 7 ,-1 , 0
       0     .06       0  126.91     .12       0   219.4     .06       0
     363     .12       0   370.1    .045       0   390.1     .12       0
  455.43     .06       0
#XS Ineff= 2 , 0
          211.81  404.07
Permanent Ineff=
       F       F
Bank Sta=370.1,390.1
XS Rating Curve= 0 ,0
Exp/Cntr=0.3,0.1

Type RM Length L Ch R = 1 ,10583.5 ,304,294.3,284.5
XS GIS Cut Line= 3
     2403760.342      391582.178     2404496.422      391718.384
     2404590.172      391727.499
#Sta/Elev= 30
       0  423.58    71.7  415.16   127.4  409.34   159.3  403.95   203.1  399.32
     215  398.19   234.9  397.71   246.9  395.56   262.8   395.4   274.7  395.74
   290.7  397.35  313.89397.8047  354.26 397.999   366.3  398.49   386.1  397.69
   394.2  395.55   398.2  395.41   402.2  396.06   406.1  397.55   414.1  398.46
     434  397.89  533.87397.7559  556.94397.7447   625.1  398.32   688.8  401.09
   712.7   402.7   728.7  404.55   748.6  407.81   795.7  418.41   842.8  425.62
#Mann= 8 ,-1 , 0
       0     .06       0   203.1     .07       0  313.89     .06       0
  354.26     .12       0   386.1    .045       0   406.1     .06       0
  533.87     .12       0  556.94     .06       0
#XS Ineff= 2 , 0
          287.55  401.79
Permanent Ineff=
       F       F
Bank Sta=386.1,406.1
XS Rating Curve= 0 ,0
Exp/Cntr=0.3,0.1

Type RM Length L Ch R = 1 ,10289.2 ,238.8,239.4,239.9
XS GIS Cut Line= 3
     2403816.414      392038.944     2404482.099      391869.426
      2404557.62      391851.196
#Sta/Elev= 30
       0  429.54       8   426.8      24  423.34    79.9  412.97   131.8  408.87
   159.8  405.89   175.7  403.61   191.7  399.98   203.7     398  230.06396.9308
   263.6  395.28   281.7396.1743   315.5  396.29   351.4  397.28  385.13397.3208
   395.4   395.9   403.4  394.63   411.4  394.84   416.2  395.82   423.3  397.27
   475.3  396.83   511.2  397.47   555.1  397.13     607  399.19     643  402.67
     667  408.07   690.8  407.65   721.9  412.57   749.1     418   764.6  419.44
#Mann= 6 ,-1 , 0
       0     .06       0  230.06     .07       0   281.7     .06       0
  385.13     .12       0   395.4    .045       0   416.2     .06       0
Bank Sta=395.4,416.2
XS Rating Curve= 0 ,0
Exp/Cntr=0.3,0.1

Type RM Length L Ch R = 1 ,10049.9 ,233.5,231.6,229.2
XS GIS Cut Line= 3
     2403864.236      392263.731     2404263.327      392171.987
     2404662.417      392080.242
#Sta/Elev= 30
       0   418.2    55.7  414.05    83.5  410.99   190.8  402.84  237.28400.2375
   266.4  398.76   278.3  395.85   282.3   395.5   290.2  395.25  297.18396.0294
   341.9     396  387.27396.7668   393.6  396.74   397.6  395.88   405.5  394.66
   413.5  394.91   421.4  395.95   433.4   396.9   453.2  396.36   516.8  396.72
   572.5  396.14   616.2  398.18   644.1  402.26   671.9  407.25   683.8  410.39
   715.6   416.3   727.6  417.62   739.5  419.88   795.2  423.71     819  424.35
#Mann= 6 ,-1 , 0
       0     .06       0  237.28     .12       0  297.18     .06       0
  387.27     .12       0   397.6    .045       0   421.4     .06       0
Bank Sta=397.6,421.4
XS Rating Curve= 0 ,0
Exp/Cntr=0.3,0.1