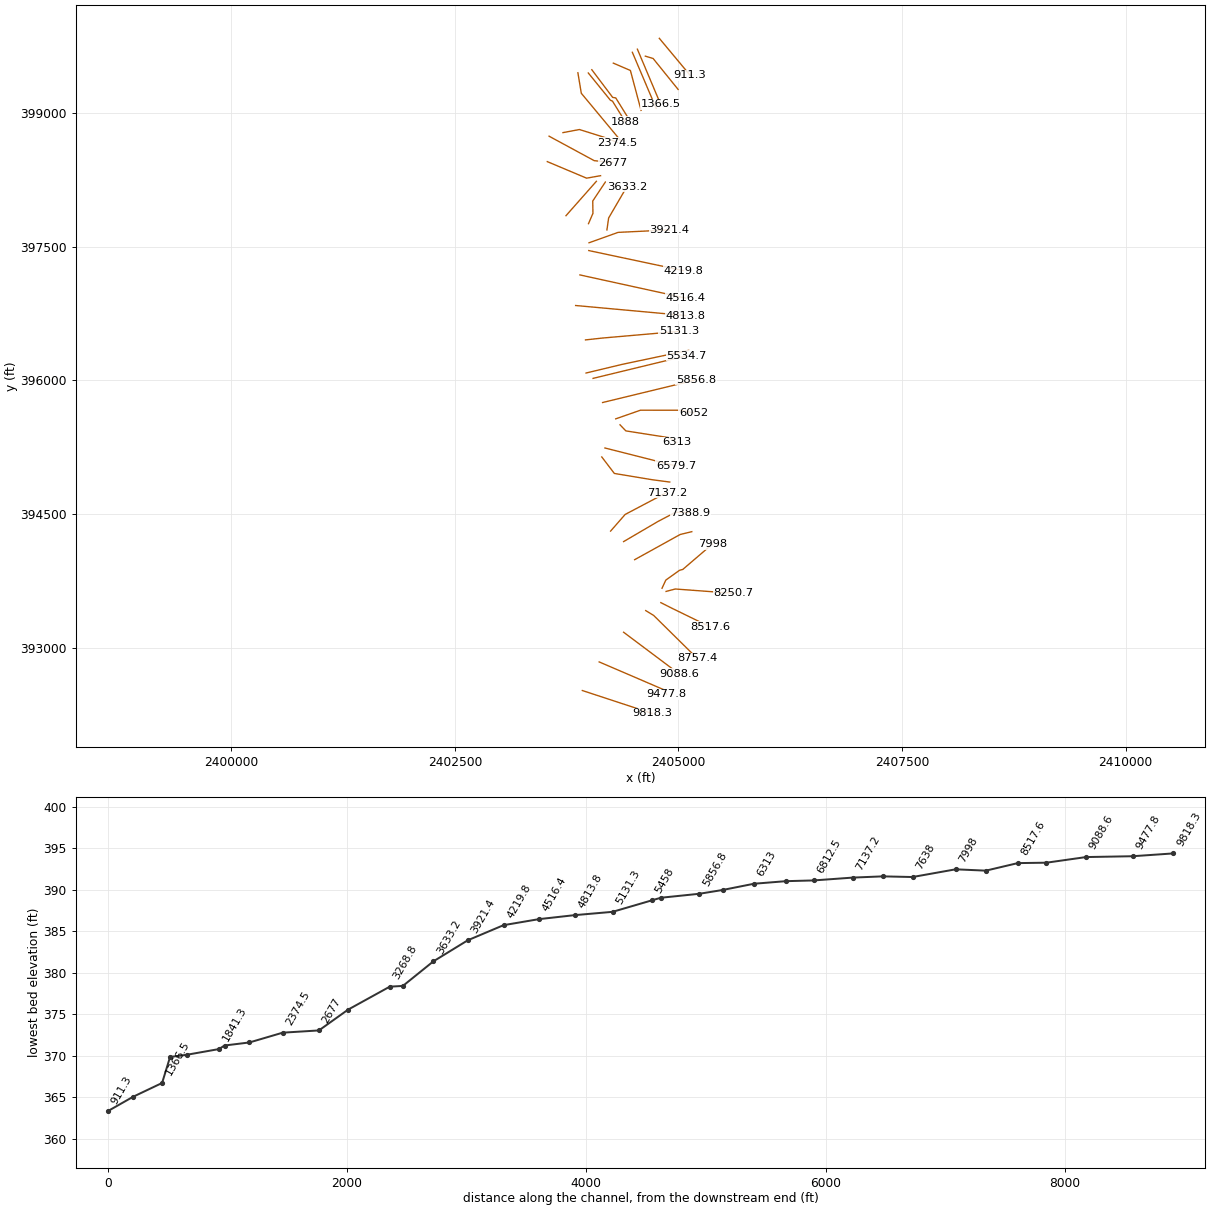
HEC-RAS study HARLANRUN.prj: HARLANRUN

--- HARLANRUN.g01 (geometry) --- (continued)

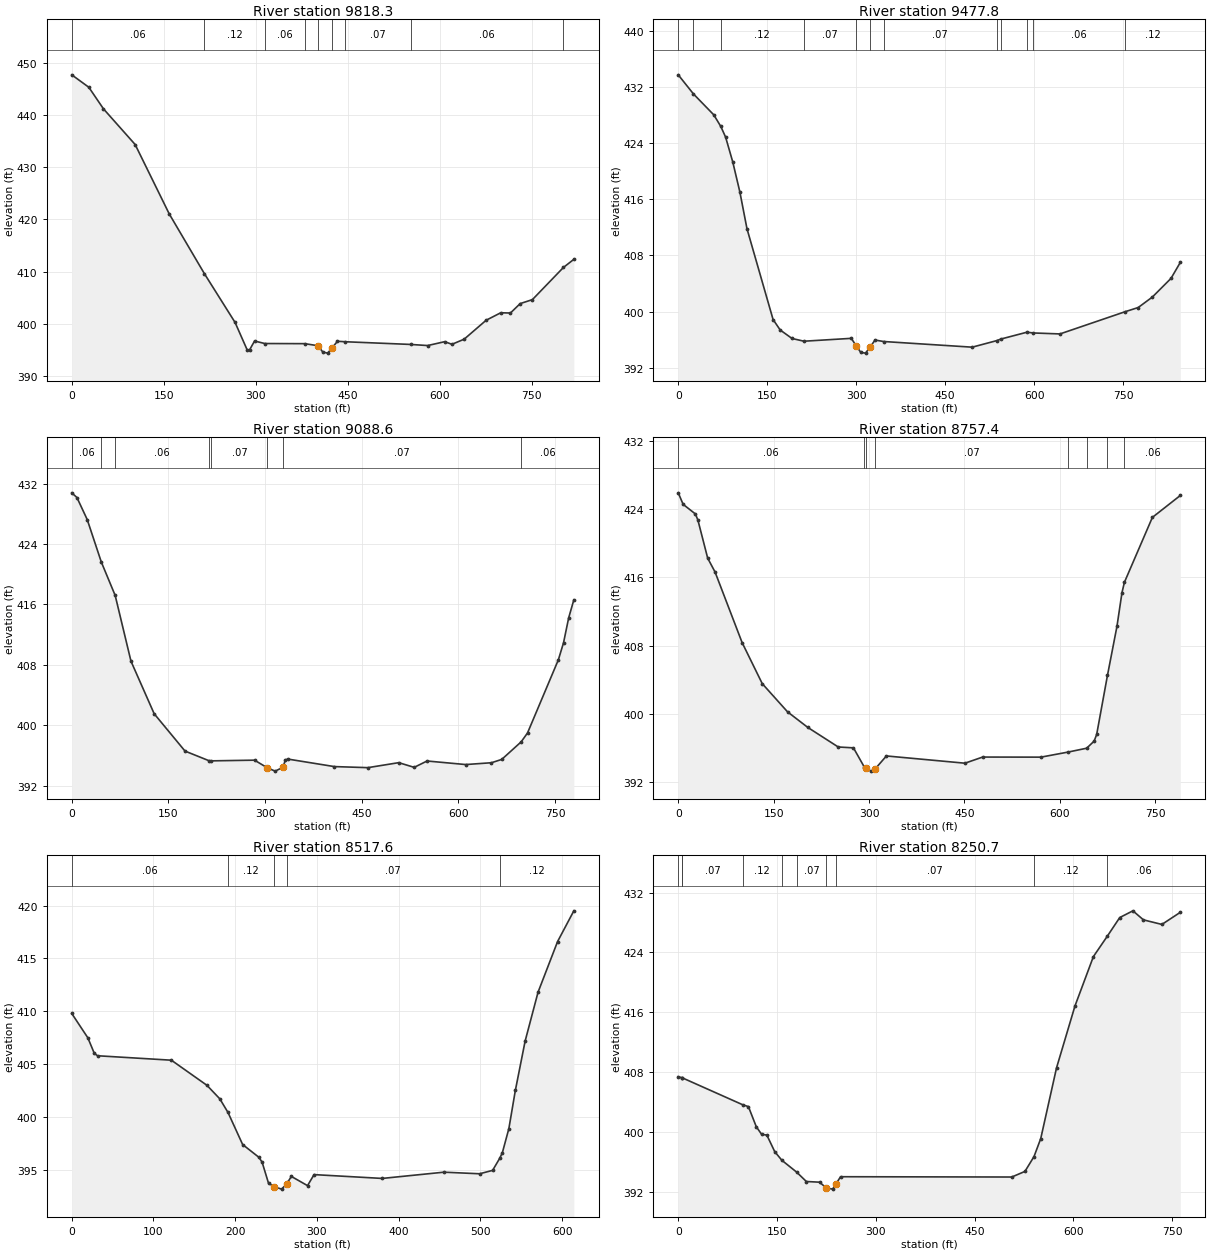
Type RM Length L Ch R = 1 ,9818.3  ,342.5,340.5,338.4
XS GIS Cut Line= 3
     2403924.937      392524.621     2404313.906      392396.584
     2404702.875      392268.547
#Sta/Elev= 30
       0  447.66    27.8  445.28    51.7  441.15   103.4  434.32     159  421.04
  216.25409.6241   266.4  400.27   286.2     395   290.2  395.06   298.2  396.72
  314.87396.2373  380.01396.2115   401.6  395.82   409.5  394.61   417.4   394.4
   425.1  395.47   433.4  396.67   445.9396.5795  552.77396.0626   580.5  395.85
   608.3  396.59   620.2  396.09   640.1  397.07   675.9  400.69   699.7  402.12
   715.6  402.08   731.5  403.88   751.4  404.64  802.09410.8042     819  412.35
#Mann= 9 ,-1 , 0
       0     .06       0  216.25     .12       0  314.87     .06       0
  380.01     .12       0   401.6    .045       0   425.1     .06       0
   445.9     .07       0  552.77     .06       0  802.09     .12       0
Bank Sta=401.6,425.1
XS Rating Curve= 0 ,0
Exp/Cntr=0.3,0.1

Type RM Length L Ch R = 1 ,9477.8  ,393.3,389.2,384.1
XS GIS Cut Line= 3
     2404112.767      392845.311     2404836.038      392533.934
     2404865.805      392482.898
#Sta/Elev= 30
       0  433.79   25.73431.0532      60  428.07   71.76426.4196    79.9  424.89
    91.9  421.36   103.9  417.07   115.9  411.82   159.9  398.86   171.9  397.36
   191.9  396.15  211.95395.7611   291.8  396.17   299.8  395.13   307.8  394.16
   315.8  394.06   323.8  394.96   331.8  395.93  346.25395.7188   495.6  394.91
  536.67395.8369  544.45396.0806  588.03397.0489  598.15396.9401   643.6   396.8
  753.56 399.976   775.5  400.57   799.3  402.06   830.8  404.73   846.5  407.01
#Mann= 12 ,-1 , 0
       0     .12       0   25.73     .06       0   71.76     .12       0
  211.95     .07       0   299.8    .045       0   323.8     .12       0
  346.25     .07       0  536.67     .12       0  544.45     .06       0
  588.03     .12       0  598.15     .06       0  753.56     .12       0
Bank Sta=299.8,323.8
XS Rating Curve= 0 ,0
Exp/Cntr=0.3,0.1

Type RM Length L Ch R = 1 ,9088.6  ,334.3,331.3,328
XS GIS Cut Line= 2
     2404386.205      393177.993      2405009.31      392710.001
#Sta/Elev= 30
       0  430.77       8  430.15      24  427.23   45.88  421.61   67.38417.1979
    91.9   408.5   127.9  401.55   175.8  396.61   212.3395.3612  216.43395.3173
   283.7  395.41   303.7  394.39   315.7  393.96   327.7  394.46   331.7  395.46
   335.7  395.55   407.6  394.56   459.6  394.42   507.5  395.08   531.5  394.46
   551.5   395.3   611.4  394.83   651.4  395.07   667.4  395.51  697.49397.8281
   707.4  399.01   755.3  408.69   763.3  410.94   771.3  414.24   779.3  416.62
#Mann= 8 ,-1 , 0
       0     .06       0   45.88     .12       0   67.38     .06       0
   212.3     .12       0  216.43     .07       0   303.7    .045       0
   327.7     .07       0  697.49     .06       0
Bank Sta=303.7,327.7
XS Rating Curve= 0 ,0
Exp/Cntr=0.3,0.1

Type RM Length L Ch R = 1 ,8757.4  ,232.3,239.7,247.2
XS GIS Cut Line= 3
     2404633.601      393420.398     2404722.576      393366.144
      2405209.83      392884.481
#Sta/Elev= 30
       0  425.92     7.7  424.57      27  423.44    30.9  422.73    46.3  418.26
    57.9  416.63   100.4  408.36   132.1  403.54   171.9  400.23   203.8   398.4
   251.6  396.11   275.5  396.01  292.22393.8012   294.5  393.61   303.4  393.28
   309.5  393.53   327.3  395.06   450.8  394.21   478.6  394.93   570.3  394.92
  612.56395.5092  642.16395.9668   653.9   396.8   657.9  397.58  674.84404.5018
   689.8  410.26   697.7  414.22  701.55415.4327   745.5  423.04   789.4  425.61
#Mann= 8 ,-1 , 0
       0     .06       0  292.22     .07       0   294.5    .045       0
   309.5     .07       0  612.56     .12       0  642.16     .06       0
  674.84     .12       0  701.55     .06       0
Bank Sta=294.5,309.5
XS Rating Curve= 0 ,0
Exp/Cntr=0.3,0.1

Type RM Length L Ch R = 1 ,8517.6  ,259.5,266.9,275.3
XS GIS Cut Line= 3
     2404802.871      393509.374     2404936.335      393442.099
     2405354.087      393238.106
#Sta/Elev= 30
       0  409.81    19.7  407.51    27.5  406.06    31.5  405.82   121.9   405.4
   165.4  403.03   181.2  401.75  191.21400.4633   209.1  397.44   228.9  396.24
   232.9  395.78   240.8  393.78   247.9  393.46   256.7  393.23   262.9  393.71
   268.7  394.43   288.5  393.56   296.5   394.6   379.9  394.24   455.4  394.83
   499.1  394.68     515     395   523.7396.1431   526.9  396.66   534.9  398.95
   542.8  402.54   554.8  407.21   570.6  411.82   594.5   416.6   614.4   419.5
#Mann= 5 ,-1 , 0
       0     .06       0  191.21     .12       0   247.9    .045       0
   262.9     .07       0   523.7     .12       0
Bank Sta=247.9,262.9
XS Rating Curve= 0 ,0
Exp/Cntr=0.3,0.1

Type RM Length L Ch R = 1 ,8250.7  ,242.3,252.7,262.2
XS GIS Cut Line= 3
     2404861.465      393635.242     2404964.559      393662.537
     2405618.685      393613.647
#Sta/Elev= 30
       0  407.36    5.81407.2236    5.95  407.22   97.98403.6082   106.6  403.36
   118.6  400.66   126.6  399.66   134.6  399.55   146.6  397.33  157.42396.1775
  179.68394.6076   194.6  393.34   214.6  393.25   224.9  392.48   234.6  392.32
   239.9  393.07   246.6  393.98   506.6  393.94   526.6  394.69  540.38396.6758
   550.6  399.08   574.6  408.55   602.6  416.83   630.6  423.44  651.93426.1929
   670.6  428.66   690.6  429.56   706.6  428.35   734.6  427.74   762.6  429.36
#Mann= 10 ,-1 , 0
       0     .08       0    5.81     .06       0    5.95     .07       0
   97.98     .12       0  157.42     .06       0  179.68     .07       0
   224.9    .045       0   239.9     .07       0  540.38     .12       0
  651.93     .06       0
Bank Sta=224.9,239.9
XS Rating Curve= 0 ,0
Exp/Cntr=0.3,0.1

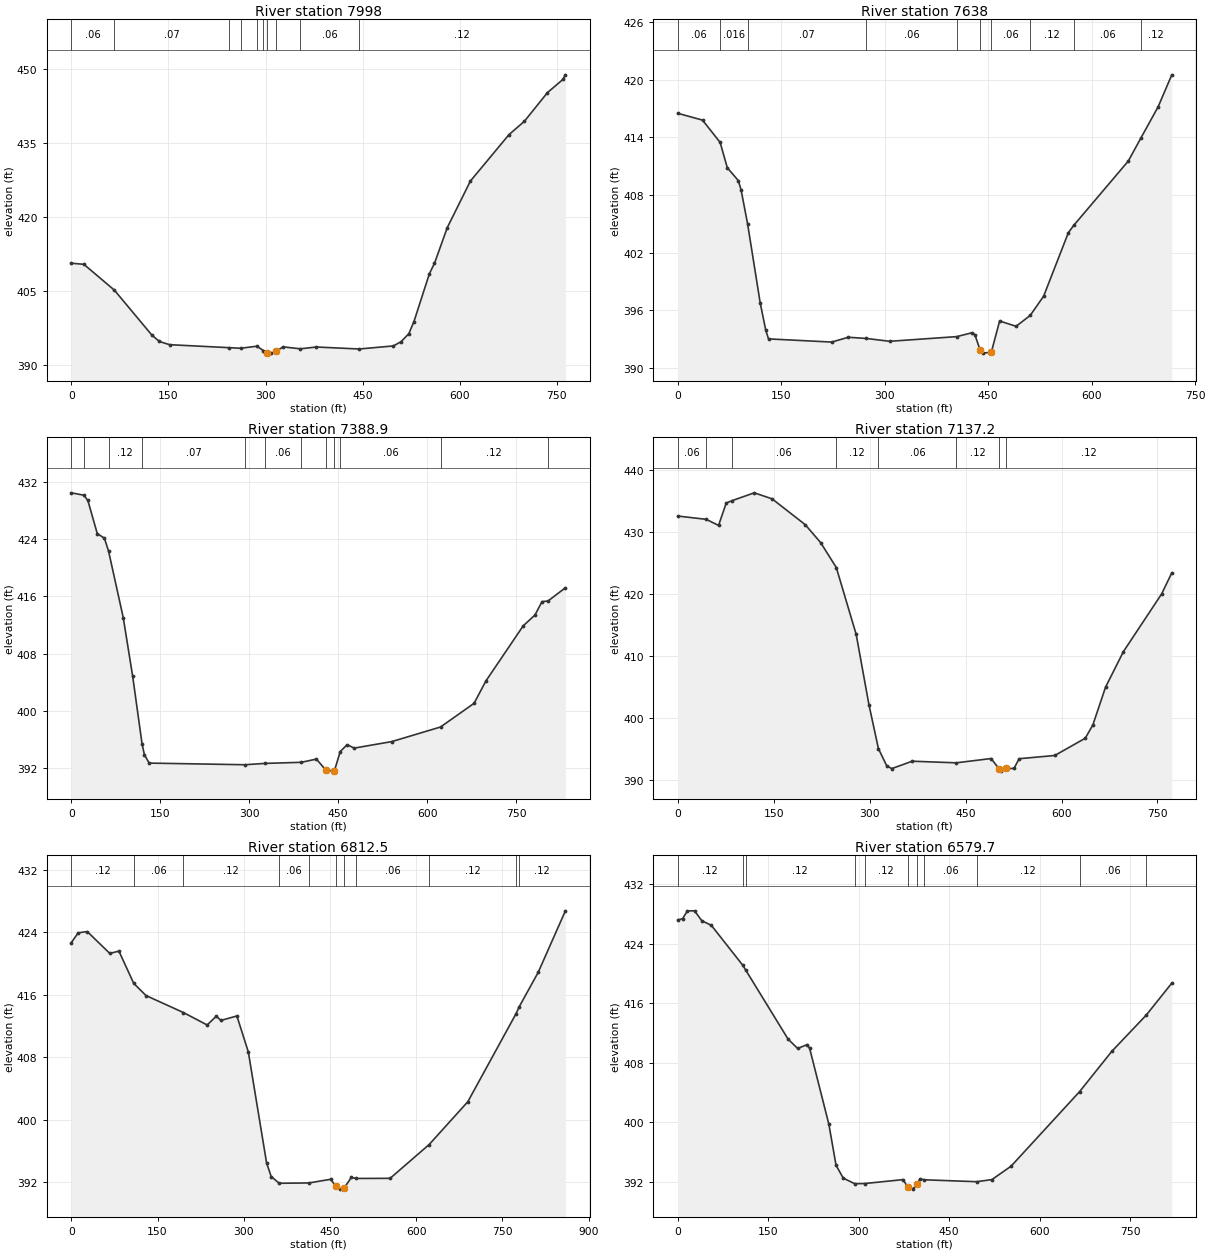
Type RM Length L Ch R = 1 ,7998    ,355.6,360,363.6
XS GIS Cut Line= 5
     2404815.892      393671.049      2404858.21      393762.195
     2405011.959      393872.249     2405048.097      393881.552
     2405379.101      394165.731
#Sta/Elev= 30
       0  410.69    19.3  410.47   66.43405.2377   124.1  396.17   135.9  394.84
   151.7  394.19  243.18 393.589  261.28393.4674  286.48393.8788  296.61393.0006
   301.7  392.56   308.2  392.48   316.7  392.85   326.9  393.75  353.64393.3546
   378.4  393.72  444.54393.3168   497.4  393.94   509.3   394.8   521.2  396.41
   529.2  398.88     553  408.56   560.9  410.68   580.7  417.92   616.4  427.34
   675.9  436.73   699.7  439.43   735.4  445.25   759.2  447.91   763.1  448.85
#Mann= 10 ,-1 , 0
       0     .06       0   66.43     .07       0  243.18     .12       0
  261.28     .06       0  286.48     .12       0  296.61     .07       0
   301.7    .045       0   316.7     .07       0  353.64     .06       0
  444.54     .12       0
Bank Sta=301.7,316.7
XS Rating Curve= 0 ,0
Exp/Cntr=0.3,0.1

Type RM Length L Ch R = 1 ,7638    ,248.2,249.1,248.9
XS GIS Cut Line= 3
     2404509.655      393990.852       2405018.8      394273.262
     2405149.009      394304.729
#Sta/Elev= 30
       0  416.49    35.9  415.78   61.46413.4614    71.8  410.83    87.7   409.5
    91.7  408.56  101.16405.0279   119.6  396.74   127.6  393.93   131.6  393.03
   223.3   392.7   247.2   393.2  273.46393.0761   307.1  392.78  404.45393.2665
   426.7  393.67   430.7  393.47   438.4  391.86   442.6  391.55   454.6  391.65
   466.6  394.89   490.5  394.34  510.93395.4698   530.4  397.47   566.3  404.08
  574.41404.8657   653.1  411.52  671.49413.9286   696.5  417.18   716.2  420.49
#Mann= 10 ,-1 , 0
       0     .06       0   61.46    .016       0  101.16     .07       0
  273.46     .06       0  404.45     .12       0   438.4    .045       0
   454.6     .06       0  510.93     .12       0  574.41     .06       0
  671.49     .12       0
Bank Sta=438.4,454.6
XS Rating Curve= 0 ,0
Exp/Cntr=0.3,0.1

Type RM Length L Ch R = 1 ,7388.9  ,253.5,251.7,250.5
XS GIS Cut Line= 4
     2404386.306      394193.508     2404773.727      394420.889
     2404966.944      394522.397     2405132.733      394519.573
#Sta/Elev= 30
       0  430.44   21.02430.1085    27.8  429.38    43.7  424.75    55.7  424.12
   62.86422.2694    87.5  413.04   103.4  404.86  119.26395.4202   123.2  393.92
   131.2  392.75  292.83392.5205  326.22392.7056  387.94392.8607   413.4  393.31
   428.8  391.81   441.3  391.63   443.8  391.71  453.51394.3558   465.1  395.32
     477  394.84   540.5  395.75  622.73397.7851   679.3  401.09   699.1  404.19
   762.2   411.9     782   413.4   793.8  415.26  804.06415.3605   833.3   417.2
#Mann= 12 ,-1 , 0
       0     .12       0   21.02    .016       0   62.86     .12       0
  119.26     .07       0  292.83     .12       0  326.22     .06       0
  387.94     .12       0   428.8    .045       0   443.8     .12       0
  453.51     .06       0  622.73     .12       0  804.06     .06       0
Bank Sta=428.8,443.8
XS Rating Curve= 0 ,0
Exp/Cntr=0.3,0.1

Type RM Length L Ch R = 1 ,7137.2  ,339.4,324.6,309.7
XS GIS Cut Line= 3
      2404241.08      394311.564     2404403.566      394497.872
     2404867.976      394743.097
#Sta/Elev= 30
       0   432.6   44.51432.0659    63.8  431.09    75.8   434.7   84.99435.0826
   119.6  436.34   147.5  435.37   199.4   431.2   223.3  428.33  247.86424.3018
     279  413.51   298.9  402.19  313.75395.1042   326.8  392.32   334.7  391.89
   366.6  393.08  435.45392.8181   489.9  393.51   502.2  391.88   505.8  391.48
   513.8  391.92   525.7  391.91   533.7  393.48   589.4     394   637.1  396.78
     649  398.93   668.9  405.03   696.8  410.75   756.5  420.04   772.4  423.44
#Mann= 8 ,-1 , 0
       0     .06       0   44.51    .016       0   84.99     .06       0
  247.86     .12       0  313.75     .06       0  435.45     .12       0
   502.2    .045       0   513.8     .12       0
Bank Sta=502.2,513.8
XS Rating Curve= 0 ,0
Exp/Cntr=0.3,0.1

Type RM Length L Ch R = 1 ,6812.5  ,234.9,232.8,231.2
XS GIS Cut Line= 4
     2404142.122      395142.293     2404282.747      394957.397
     2404710.641      394886.327     2404902.539      394861.043
#Sta/Elev= 30
       0  422.68    11.8  423.92    27.6  424.09    66.9  421.29    82.7  421.59
  108.55 417.455   129.9   415.9  194.84413.7333   236.3  412.14   252.2  413.26
   260.2  412.72     288  413.29   307.9  408.69   339.7  394.48   347.7  392.75
   361.6  391.89  413.35391.9295   451.2   392.4   460.1   391.5   467.1  391.14
   475.1  391.32     487  392.63   495.8392.5042   554.6  392.52  622.54396.8452
   689.8  402.32  773.86413.6004  779.31414.4813   812.2  418.86   859.6  426.74
#Mann= 11 ,-1 , 0
       0     .12       0  108.55     .06       0  194.84     .12       0
   361.6     .06       0  413.35     .12       0   460.1    .045       0
   475.1     .12       0   495.8     .06       0  622.54     .12       0
  773.86     .06       0  779.31     .12       0
Bank Sta=460.1,475.1
XS Rating Curve= 0 ,0
Exp/Cntr=0.3,0.1

Type RM Length L Ch R = 1 ,6579.7  ,264.5,266.8,268.6
XS GIS Cut Line= 3
     2404177.313      395242.892      2404574.21      395142.082
     2404971.108      395041.273
#Sta/Elev= 30
       0  427.19       8  427.35    15.9   428.4    27.8  428.41    39.8  427.09
    55.7  426.46  107.65421.1162  113.02420.4106   182.9  411.19   198.8  409.93
   214.7  410.46   218.7  409.93   250.5  399.76   262.4  394.26   274.3  392.53
   293.4 391.778  309.72391.7981   373.7  392.33   381.2  391.31   389.6  391.05
   396.2  391.71   401.6  392.44  408.07 392.305  495.65392.0462   520.8  392.33
   552.6  394.13  666.08 404.134   719.6  409.55  776.53414.3998     819   418.7
#Mann= 11 ,-1 , 0
       0     .12       0  107.65     .06       0  113.02     .12       0
   293.4     .06       0  309.72     .12       0   381.2    .045       0
   396.2     .12       0  408.07     .06       0  495.65     .12       0
  666.08     .06       0  776.53     .12       0
Bank Sta=381.2,396.2
XS Rating Curve= 0 ,0
Exp/Cntr=0.3,0.1

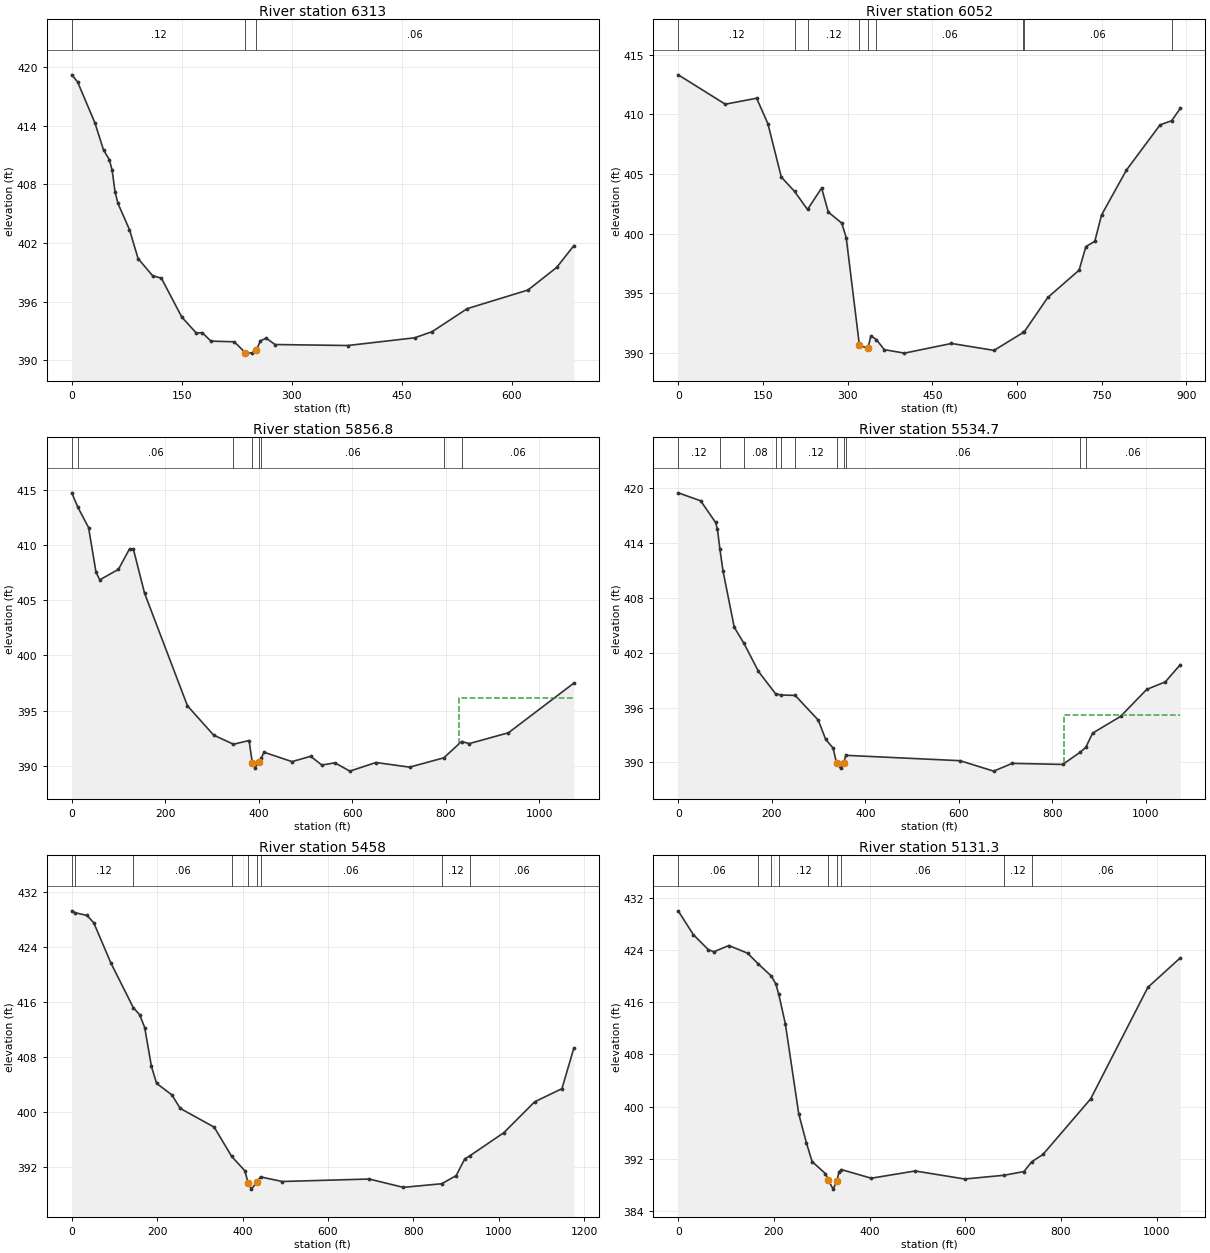
Type RM Length L Ch R = 1 ,6313    ,257.5,260.9,264.4
XS GIS Cut Line= 4
     2404346.057      395502.646     2404411.351      395434.405
      2404901.83      395357.247     2404979.955      395305.163
#Sta/Elev= 30
       0  419.22     7.9   418.5    31.5  414.32    43.3  411.53    51.2  410.55
    55.1  409.44      59  407.26      63  406.06    78.7  403.38    90.5  400.41
   110.3  398.66   122.2  398.41   150.1  394.43   169.9  392.79   177.9  392.84
   189.8  391.97   221.6   391.9   236.7  390.79   245.4  390.74   251.7  391.05
   257.3     392   265.2  392.27   277.2  391.62   376.5  391.52   467.8  392.31
   491.6  392.94   539.3  395.29   622.3   397.2   661.4  399.51   684.8  401.74
#Mann= 3 ,-1 , 0
       0     .12       0   236.7    .045       0   251.7     .06       0
Bank Sta=236.7,251.7
XS Rating Curve= 0 ,0
Exp/Cntr=0.3,0.1

Type RM Length L Ch R = 1 ,6052    ,189.8,195.2,200.6
XS GIS Cut Line= 4
     2404298.372      395569.376     2404575.441      395666.275
     2405027.539      395665.731     2405168.164      395637.085
#Sta/Elev= 30
       0   413.3    83.3  410.84   138.8  411.34   158.7  409.22   182.5  404.74
  205.98403.5336  228.95402.0215   253.9  403.82   265.8   401.8   289.6  400.88
   297.5  399.65   320.8  390.66   335.8  390.39   341.1  391.43  350.85391.1274
   364.9  390.28   400.6  389.99   483.9   390.8   559.2  390.22  611.27391.7282
  612.39391.7478   654.4  394.65   709.9  396.94   721.8  398.91   737.7  399.36
   749.6  401.56   793.5  405.31   853.3  409.11  873.61409.4533   889.1  410.49
#Mann= 9 ,-1 , 0
       0     .12       0  205.98     .06       0  228.95     .12       0
   320.8    .045       0   335.8     .12       0  350.85     .06       0
  611.27     .12       0  612.39     .06       0  873.61     .12       0
Bank Sta=320.8,335.8
XS Rating Curve= 0 ,0
Exp/Cntr=0.3,0.1

Type RM Length L Ch R = 1 ,5856.8  ,321.6,322.1,321.6
XS GIS Cut Line= 2
     2404151.396      395752.212     2405194.799      396005.684
#Sta/Elev= 30
       0   414.7    13.1413.3927    35.9  411.56    51.9  407.51    59.9  406.83
    99.8  407.78   123.7  409.64   131.7  409.62   155.7  405.62   247.5  395.43
   303.4  392.79  345.78391.9614   379.2   392.3   386.2  390.27   391.2  389.85
   401.2  390.32  405.54390.7401   411.1  391.24     471  390.39   510.9  390.87
   534.9  390.08   562.8  390.28   594.8  389.53   650.6  390.31   722.5  389.89
  795.86390.7346  833.53392.2095   850.2  392.02     934     393  1073.8  397.49
#Mann= 8 ,-1 , 0
       0     .12       0    13.1     .06       0  345.78     .12       0
   386.2    .045       0   401.2     .12       0  405.54     .06       0
  795.86     .12       0  833.53     .06       0
#XS Ineff= 2 , 0
                          828.75          396.17
Permanent Ineff=
       F       F
Bank Sta=386.2,401.2
XS Rating Curve= 0 ,0
Exp/Cntr=0.3,0.1

Type RM Length L Ch R = 1 ,5534.7  ,77,76.7,76.2
XS GIS Cut Line= 2
     2404045.059      396022.959     2405088.462      396276.431
#Sta/Elev= 30
       0  419.47    47.9   418.6    79.8  416.24    83.8   415.5   89.13413.3115
    95.8  410.92   119.8  404.78  140.57 403.013   171.6  399.95  208.15397.5045
  219.69397.3757  250.19397.3228   299.4  394.63   315.3  392.53   331.3  391.56
   338.5  389.95   347.3  389.36   353.5  389.89  358.43 390.778   602.7  390.19
   674.6  389.05   714.5   389.9   822.3  389.78  859.03391.0949  871.73391.6503
   886.1   393.2     946  395.03  1001.9  397.98  1041.8  398.81  1073.8  400.69
#Mann= 11 ,-1 , 0
       0     .12       0   89.13     .06       0  140.57     .08       0
  208.15     .06       0  219.69     .08       0  250.19     .12       0
   338.5    .045       0   353.5     .12       0  358.43     .06       0
  859.03     .12       0  871.73     .06       0
#XS Ineff= 2 , 0
                          825.67          395.18
Permanent Ineff=
       F       F
Bank Sta=338.5,353.5
XS Rating Curve= 0 ,0
Exp/Cntr=0.3,0.1

Type RM Length L Ch R = 1 ,5458    ,329.9,326.7,323.7
XS GIS Cut Line= 3
     2403966.261      396082.908     2404375.606       396181.03
     2405114.269      396337.137
#Sta/Elev= 30
       0  429.23    7.37 428.959    35.7  428.56    51.6  427.48    91.3  421.68
  144.11415.1445   158.8  414.13   170.8  412.25   186.6  406.58   198.6  404.13
   234.3  402.45   254.2  400.47   333.6  397.75  374.55393.4863   405.1  391.42
     413  389.67   420.9  388.73   432.9  389.72  442.03390.5146   492.8  389.84
   696.6   390.2   776.5  388.99  866.58389.5142   900.3   390.7   920.3  393.12
  931.83393.5598  1012.1  396.95    1084  401.43    1148  403.35  1175.9  409.25
#Mann= 9 ,-1 , 0
       0     .06       0    7.37     .12       0  144.11     .06       0
  374.55     .12       0     413    .045       0   432.9     .12       0
  442.03     .06       0  866.58     .12       0  931.83     .06       0
Bank Sta=413,432.9
XS Rating Curve= 0 ,0
Exp/Cntr=0.3,0.1

Type RM Length L Ch R = 1 ,5131.3  ,321.5,317.5,313.4
XS GIS Cut Line= 3
     2403960.163      396454.122     2404151.135      396474.955
     2405005.302      396549.608
#Sta/Elev= 30
       0  429.96    31.4  426.33    62.7  424.03    74.5  423.69   105.8  424.65
   145.1  423.47  167.31421.8328  194.47419.9819   204.1  418.75  210.21417.1541
     224  412.63   251.9  398.87   267.9  394.44   279.8  391.57   307.8  389.72
   313.8  388.73   323.7  387.35   331.7   388.6   335.7   389.9  340.85390.3416
   403.5  389.02   495.2  390.13   598.9   388.9  680.61389.4702   722.5  390.04
  738.97391.5386   762.4  392.66   862.1  401.17   981.7  418.25  1049.5  422.76
#Mann= 9 ,-1 , 0
       0     .06       0  167.31     .12       0  194.47     .06       0
  210.21     .12       0   313.8    .045       0   331.7     .12       0
  340.85     .06       0  680.61     .12       0  738.97     .06       0
Bank Sta=313.8,331.7
XS Rating Curve= 0 ,0
Exp/Cntr=0.3,0.1

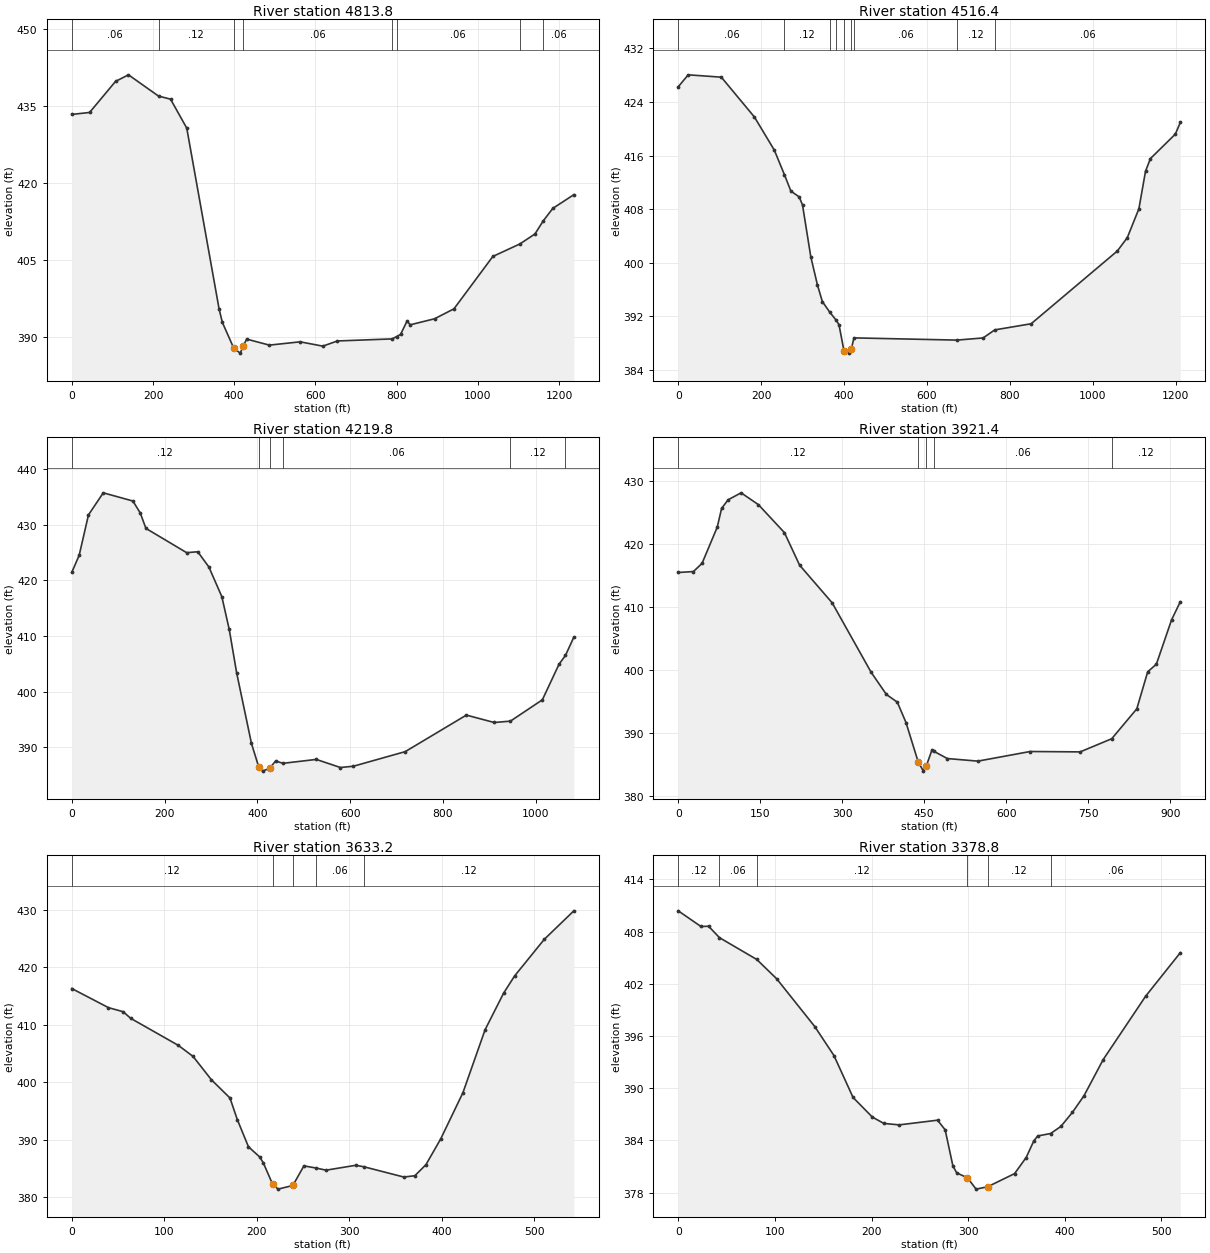
Type RM Length L Ch R = 1 ,4813.8  ,300.2,297.4,294.6
XS GIS Cut Line= 2
     2403849.918      396839.511      2405080.88      396726.755
#Sta/Elev= 30
       0  433.44    43.9  433.82   107.7  439.87   139.6  441.15  213.61437.0097
   243.2  436.41   283.1  430.77   362.9  395.47   370.8  392.92   398.8  387.92
   414.7  386.95   422.7  388.42   430.6  389.68   486.5  388.51   562.2  389.15
   618.1  388.31     654  389.32  788.82389.7196  799.61390.1761   809.5  390.59
   825.4  393.19   833.4  392.47   893.2  393.64     941  395.58  1036.7  405.78
 1103.18408.2108  1140.4  410.16 1160.69412.7005  1184.3  415.14  1236.1  417.81
#Mann= 8 ,-1 , 0
       0     .06       0  213.61     .12       0   398.8    .045       0
   422.7     .06       0  788.82     .12       0  799.61     .06       0
 1103.18     .12       0 1160.69     .06       0
Bank Sta=398.8,422.7
XS Rating Curve= 0 ,0
Exp/Cntr=0.3,0.1

Type RM Length L Ch R = 1 ,4516.4  ,296.4,296.6,296.8
XS GIS Cut Line= 2
     2403897.315      397182.377     2405079.955      396922.872
#Sta/Elev= 30
       0  426.27      24  428.06   103.9  427.71   183.8  421.75   231.8   416.8
  256.16413.1241   271.7  410.68   291.7  409.82   299.7  408.61   319.7  400.86
   335.7  396.66   347.6  394.17  365.58392.5774   379.9391.4652   387.6  390.73
   399.6  386.85   411.6  386.47   417.3  387.07  423.77388.7483  672.14388.4158
   735.3  388.74  763.39389.9433   851.1  390.86  1058.9  401.73  1082.9  403.72
  1110.9  408.04  1126.9  413.65  1138.8  415.55  1198.8   419.2  1210.8  420.94
#Mann= 9 ,-1 , 0
       0     .06       0  256.16     .12       0  365.58     .06       0
   379.9     .12       0   399.6    .045       0   417.3     .12       0
  423.77     .06       0  672.14     .12       0  763.39     .06       0
Bank Sta=399.6,417.3
XS Rating Curve= 0 ,0
Exp/Cntr=0.3,0.1

Type RM Length L Ch R = 1 ,4219.8  ,293,298.4,304
XS GIS Cut Line= 2
     2403996.911       397455.22     2405055.649      397230.163
#Sta/Elev= 30
       0  421.41      16   424.5      36  431.74    67.9   435.7   131.8  434.23
   147.8  432.06   159.8  429.32   247.6  424.96   271.6  425.12   295.6  422.39
   323.5  417.06   339.5  411.17   355.5  403.36   387.4  390.71   403.4   386.4
   411.4  385.74   426.6  386.26   439.4  387.55  455.45387.1455   527.2  387.84
   579.1  386.39   607.1  386.62   718.9  389.24   850.7   395.8   910.6  394.47
  945.67394.7137  1014.5  398.54  1050.4  404.92 1064.39406.5186  1082.4   409.8
#Mann= 6 ,-1 , 0
       0     .12       0   403.4    .045       0   426.6     .12       0
  455.45     .06       0  945.67     .12       0 1064.39     .06       0
Bank Sta=403.4,426.6
XS Rating Curve= 0 ,0
Exp/Cntr=0.3,0.1

Type RM Length L Ch R = 1 ,3921.4  ,265,288.2,310.9
XS GIS Cut Line= 3
     2403999.928      397542.591     2404324.746      397658.983
     2404897.663      397686.761
#Sta/Elev= 30
       0  415.51    27.8  415.66    43.6  416.97    71.4  422.73    79.3  425.69
    91.2  427.07     115  428.18   146.7   426.3   194.3  421.85   222.1  416.67
   281.6  410.69     353  399.63   380.9  396.11   400.8  394.89   416.7  391.65
     439  385.39   448.6  383.92     454  384.79   464.5  387.34  468.27387.0478
   492.4  385.92   548.2  385.51   643.8  387.04   735.4  386.98  793.11389.0716
     839  393.83   858.9  399.71   874.8  400.93   902.7     408   918.6  410.86
#Mann= 5 ,-1 , 0
       0     .12       0     439    .045       0     454     .12       0
  468.27     .06       0  793.11     .12       0
Bank Sta=439,454
XS Rating Curve= 0 ,0
Exp/Cntr=0.3,0.1

Type RM Length L Ch R = 1 ,3633.2  ,255.5,254.4,252.9
XS GIS Cut Line= 3
     2404199.746      397686.327     2404218.844      397820.007
     2404423.705      398172.438
#Sta/Elev= 30
       0   416.3    39.7  412.97    55.6  412.26    63.6  411.12   115.2   406.4
   131.1  404.48     151   400.4     171  397.24     179  393.45     191  388.74
     203  386.99     207  385.96     217  382.26     223  381.37     239  382.01
   250.9  385.42  263.57385.0614   274.9  384.67   306.9  385.52     316385.2552
   358.8  383.48   370.8   383.7   382.8  385.62   398.8  390.12   422.8  398.16
   446.8  409.14   466.8   415.5   478.7   418.5   510.7  424.86   542.7  429.83
#Mann= 5 ,-1 , 0
       0     .12       0     217    .045       0     239     .12       0
  263.57     .06       0     316     .12       0
Bank Sta=217,239
XS Rating Curve= 0 ,0
Exp/Cntr=0.3,0.1

Type RM Length L Ch R = 1 ,3378.8  ,113,109.9,106.8
XS GIS Cut Line= 4
     2403993.511      397756.876     2404043.424      397871.894
     2404041.254      398010.783     2404182.313      398223.456
#Sta/Elev= 30
       0  410.38    23.5  408.58    31.4  408.61   42.69407.2957    81.3  404.79
   101.9  402.57   141.3  397.08   161.1  393.76   180.9  388.94   200.8  386.69
   212.7  385.96   228.6  385.79   268.3  386.33   276.2  385.22   284.2  381.07
   288.2  380.27   299.3  379.71   308.2  378.41   320.1  378.68     348  380.19
     360  382.04     368  383.97     372  384.52  385.29384.7961   395.9  385.61
   407.8  387.22   419.8  389.13   439.7  393.29   483.6  400.57   519.5  405.57
#Mann= 6 ,-1 , 0
       0     .12       0   42.69     .06       0    81.3     .12       0
   299.3    .045       0   320.1     .12       0  385.29     .06       0
Bank Sta=299.3,320.1
XS Rating Curve= 0 ,0
Exp/Cntr=0.3,0.1

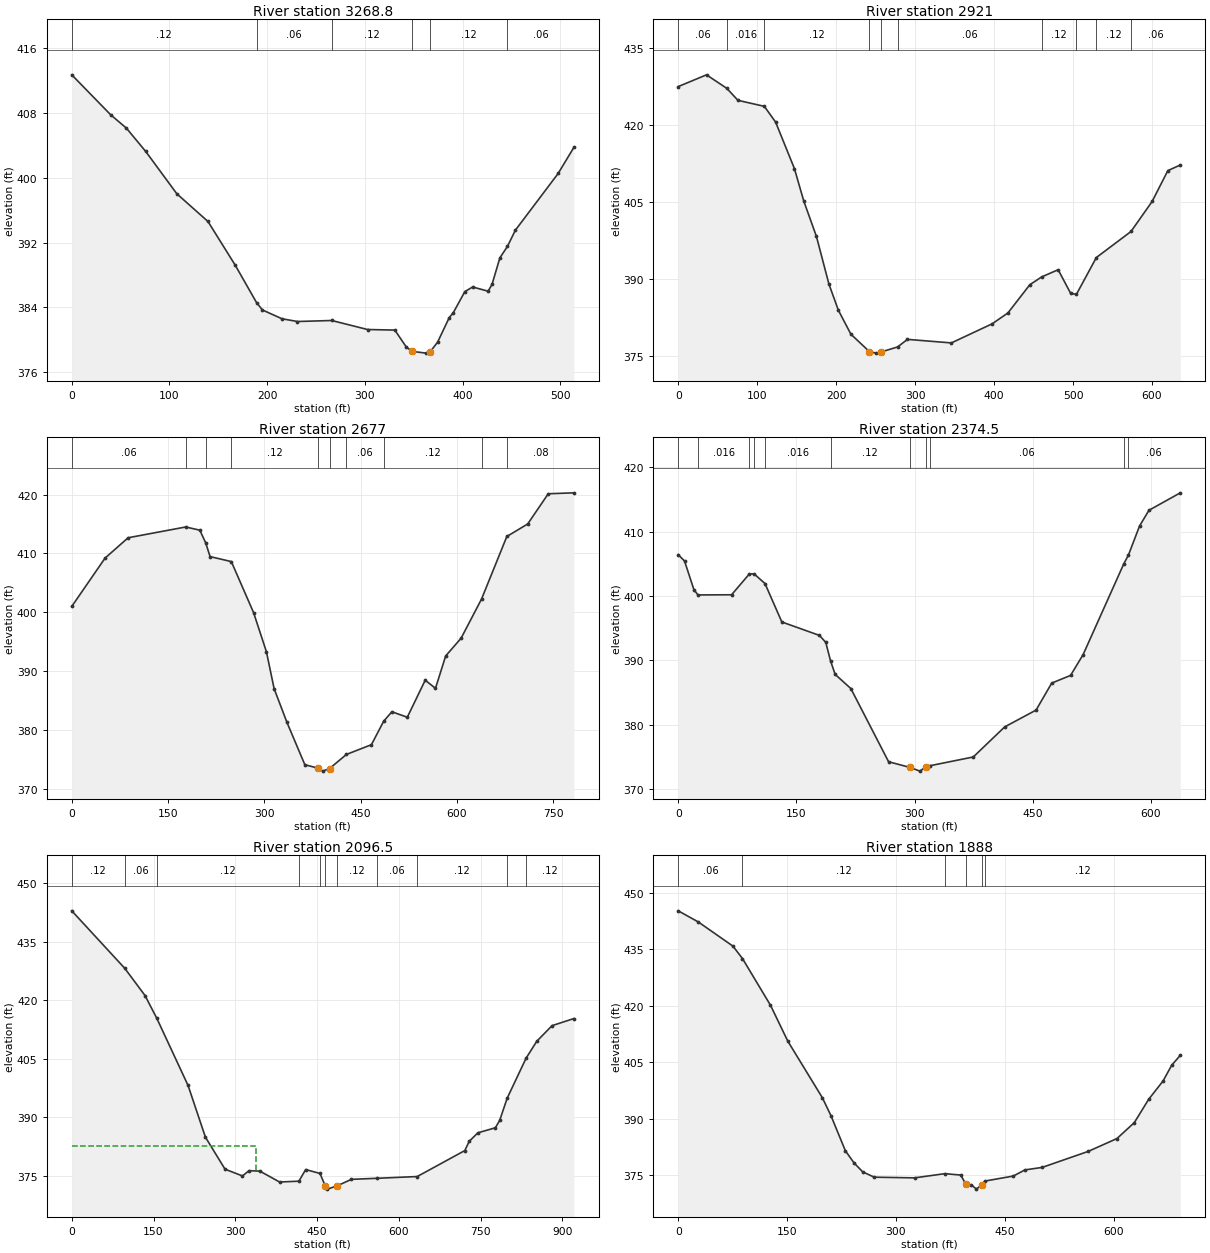
Type RM Length L Ch R = 1 ,3268.8  ,378,347.8,317.5
XS GIS Cut Line= 2
     2403741.775      397845.852     2404081.643      398231.112
#Sta/Elev= 30
       0  412.74    39.8   407.8    55.8  406.16    75.7  403.26   107.5  398.03
   139.4   394.6   167.3  389.19  189.07384.5761   195.1  383.66   215.1  382.57
     231  382.23  266.05382.3556   302.7  381.24   330.6  381.17   342.5  379.05
   348.4  378.54   362.4  378.32   366.4  378.43   374.4  379.68   386.3  382.72
   390.3  383.29   402.2  385.92   410.2   386.5   426.1  385.98   430.1  386.83
   438.1   390.1   445.9391.5328     454  393.53   497.8  400.55   513.8  403.76
#Mann= 6 ,-1 , 0
       0     .12       0  189.07     .06       0  266.05     .12       0
   348.4    .045       0   366.4     .12       0   445.9     .06       0
Bank Sta=348.4,366.4
XS Rating Curve= 0 ,0
Exp/Cntr=0.3,0.1

Type RM Length L Ch R = 1 ,2921    ,246.4,244,241.7
XS GIS Cut Line= 3
     2403532.747      398452.189     2403972.316      398266.622
     2404128.566        398294.4
#Sta/Elev= 30
       0  427.49    35.8  429.78   61.49427.1486    75.6  424.81  109.02423.6389
   123.3  420.57   147.1  411.52     159  405.17     175  398.29   190.8  389.02
   202.8   383.9   218.7  379.23     242  375.86   250.5  375.55     257  375.78
   277.7376.7485   290.3  378.23   345.9  377.54   397.6  381.27   417.5  383.38
   445.3  388.89  460.26390.4037   481.1   391.8     497  387.18  504.25387.0096
  529.48394.1765  573.36399.2524   600.1   405.1     620  411.11   635.8  412.21
#Mann= 10 ,-1 , 0
       0     .06       0   61.49    .016       0  109.02     .12       0
     242    .045       0     257     .12       0   277.7     .06       0
  460.26     .12       0  504.25     .06       0  529.48     .12       0
  573.36     .06       0
Bank Sta=242,257
XS Rating Curve= 0 ,0
Exp/Cntr=0.3,0.1

Type RM Length L Ch R = 1 ,2677    ,296.9,302.4,307.1
XS GIS Cut Line= 3
     2403552.727       398736.87     2404057.819      398462.802
     2404264.417      398441.969
#Sta/Elev= 30
       0  401.01    51.9  409.22    87.8  412.67  177.54414.5009   199.5  413.96
  208.65 411.811   215.5  409.47  248.63 408.624   283.3  399.95   303.3  393.31
   315.3  387.04   335.2  381.34   363.2  374.12   383.1  373.57   391.1  373.04
   401.7  373.48  427.89  375.87   466.9  377.53  486.02381.5206   498.8  383.12
   522.8  382.19   550.7  388.48   566.7   387.1   582.6   392.6   606.6  395.61
  638.48402.2605   677.9 412.887   710.4  415.01   742.4  420.14   782.3   420.3
#Mann= 10 ,-1 , 0
       0     .06       0  177.54     .12       0  208.65    .016       0
  248.63     .12       0   383.1    .045       0   401.7     .12       0
  427.89     .06       0  486.02     .12       0  638.48     .06       0
   677.9     .08       0
Bank Sta=383.1,401.7
XS Rating Curve= 0 ,0
Exp/Cntr=0.3,0.1

Type RM Length L Ch R = 1 ,2374.5  ,290.9,278,264.7
XS GIS Cut Line= 4
     2403708.427      398777.038     2403892.455      398811.761
     2404200.271      398715.002     2404317.802      398665.927
#Sta/Elev= 30
       0  406.42       8  405.44    19.9  400.98   25.06400.1639    67.7  400.19
   90.29403.4294   96.29403.4369  110.14401.9326   131.5  395.96   179.3  393.87
   187.3  392.78  193.28389.9237   199.2  387.81   219.1  385.61     267  374.23
     294  373.35   306.8  372.77   314.8  373.48  319.38373.6064   374.5  374.97
   414.3  379.64   454.2  382.26   474.1  386.46     498  387.65   513.9  390.88
  565.73405.0469  571.29406.3118   585.6  410.89   597.5  413.33   637.3  416.04
#Mann= 11 ,-1 , 0
       0     .06       0   25.06    .016       0   90.29     .06       0
   96.29     .12       0  110.14    .016       0  193.28     .12       0
     294    .045       0   314.8     .12       0  319.38     .06       0
  565.73     .12       0  571.29     .06       0
Bank Sta=294,314.8
XS Rating Curve= 0 ,0
Exp/Cntr=0.3,0.1

Type RM Length L Ch R = 1 ,2096.5  ,203.7,208.5,213.6
XS GIS Cut Line= 3
     2403875.094      399448.045     2403913.253      399218.001
     2404352.524      398688.497
#Sta/Elev= 30
       0  442.94   97.33428.1874   134.4  421.22  156.09415.3675   213.4  398.16
   245.2  384.92   281.2   376.7   313.2  374.97   325.2  376.32   345.2   376.2
   381.2  373.42  416.71373.6238   429.2  376.61  455.42375.6103   465.2  372.37
   469.2  371.59   487.4  372.47   513.2   374.1  560.64374.3706  633.85374.8187
   721.2  381.48   729.2  383.85   745.2  386.03   777.2  387.32   785.2  389.23
  798.82394.8888  833.52 405.146   853.2   409.5   881.2   413.5   921.2  415.32
#Mann= 11 ,-1 , 0
       0     .12       0   97.33     .06       0  156.09     .12       0
  416.71    .016       0  455.42     .12       0   465.2    .045       0
   487.4     .12       0  560.64     .06       0  633.85     .12       0
  798.82     .06       0  833.52     .12       0
#XS Ineff= 2 , 0
           338.9  382.76
Permanent Ineff=
       F       F
Bank Sta=465.2,487.4
XS Rating Curve= 0 ,0
Exp/Cntr=0.3,0.1

Type RM Length L Ch R = 1 ,1888    ,40,46.7,51.4
XS GIS Cut Line= 4
     2403991.487      399445.401     2404238.867      399139.863
     2404261.783       399130.14     2404405.794      398897.241
#Sta/Elev= 30
       0  445.28    27.8   442.3    75.4  435.88   88.49432.5858   127.1  420.16
   150.9  410.62   198.6  395.54   210.5  390.74   230.3  381.43   242.2  378.21
   254.1  375.83     270   374.4   325.6  374.22  367.44375.3335   389.2  374.96
   396.5  372.49   403.8  372.36   410.9  371.22     418  372.36  422.39373.3624
   461.7   374.7   477.6  376.33   501.4     377   564.9  381.26   604.5  384.68
   628.4  388.91   648.2  395.12     668  399.99   679.9  404.18   691.8  406.84
#Mann= 6 ,-1 , 0
       0     .06       0   88.49     .12       0  367.44    .016       0
   396.5    .045       0     418    .016       0  422.39     .12       0
Bank Sta=396.5,418
XS Rating Curve= 0 ,0
Exp/Cntr=0.3,0.1

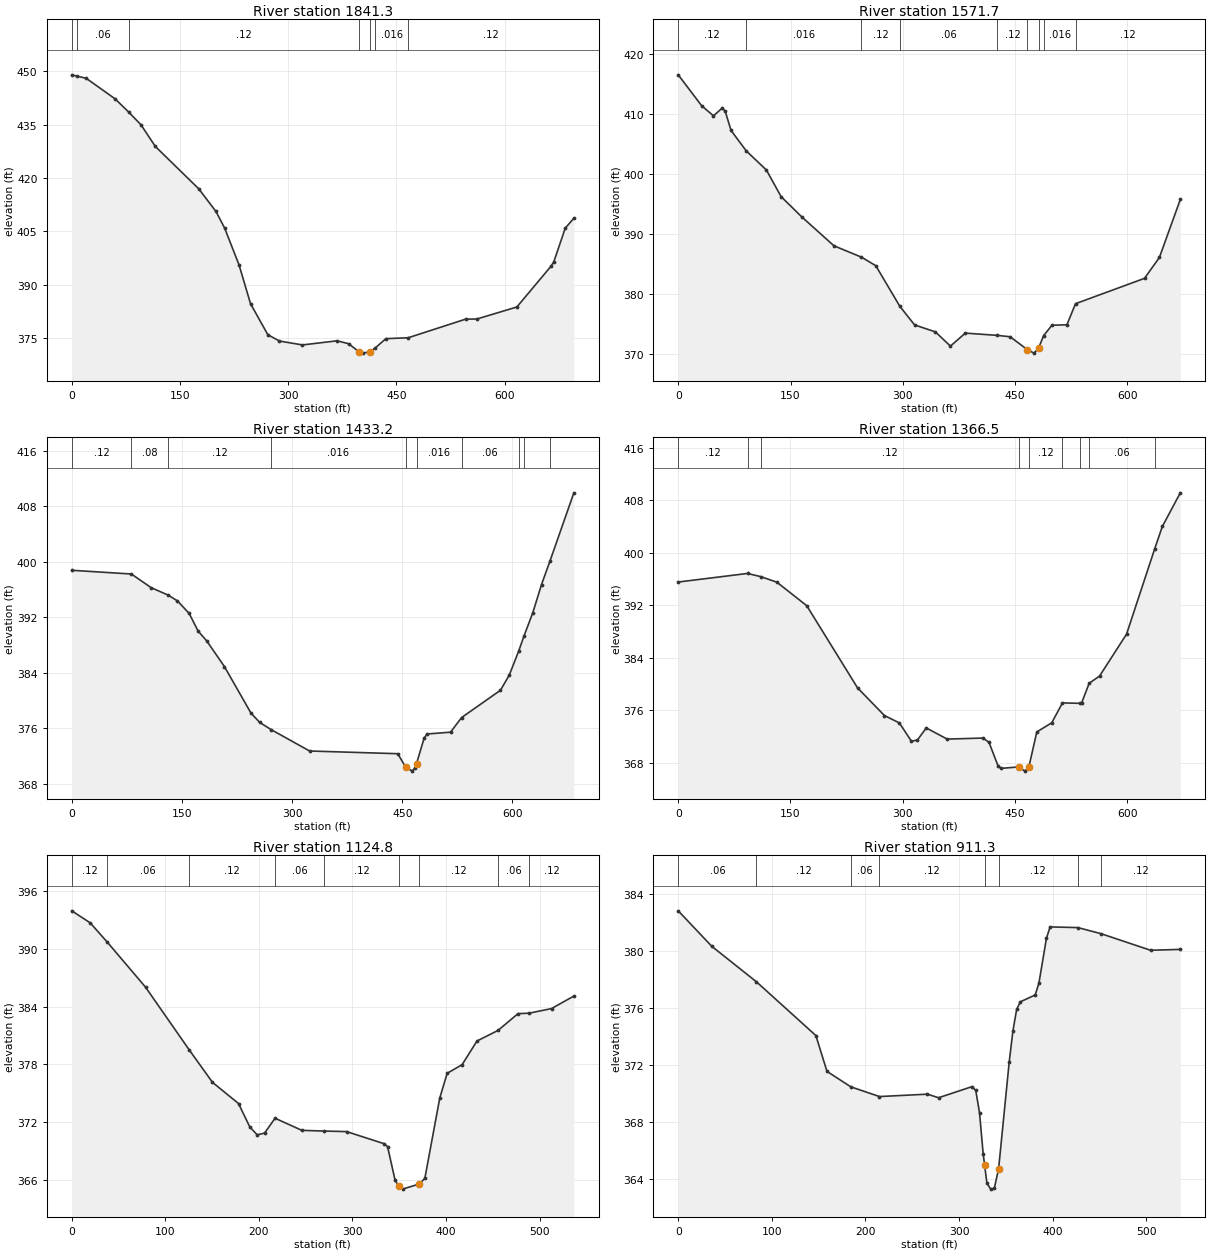
Type RM Length L Ch R = 1 ,1841.3  ,290.9,269.6,249.9
XS GIS Cut Line= 4
     2404030.794      399481.876     2404263.867      399171.981
     2404299.023       399165.47     2404442.252      398933.699
#Sta/Elev= 30
       0  448.96    7.45448.5751      20  447.99      60  442.22   78.87438.5047
    95.9  434.93   115.9  428.83   175.9  416.97   199.9  410.58   211.9  405.91
   231.9  395.56   247.8  384.67   271.8  375.96   287.8  374.19   319.8  373.09
   367.8  374.25   383.8  373.43   398.6   371.1   403.6  370.79   413.6  371.19
  420.89372.2785   435.4  374.85  466.23375.1015   545.9  380.33   561.7  380.38
     617  383.75   664.4  395.21   668.3  396.48   684.1   405.9     696  408.68
#Mann= 7 ,-1 , 0
       0     .12       0    7.45     .06       0   78.87     .12       0
   398.6    .045       0   413.6     .12       0  420.89    .016       0
  466.23     .12       0
Bank Sta=398.6,413.6
XS Rating Curve= 0 ,0
Exp/Cntr=0.3,0.1

Type RM Length L Ch R = 1 ,1571.7  ,135.2,138.5,141.5
XS GIS Cut Line= 3
     2404271.289      399555.922     2404462.261      399473.456
     2404581.619      399026.408
#Sta/Elev= 30
       0  416.54    31.4  411.36    47.1   409.7    58.9  411.01    62.8  410.44
    70.6  407.25   90.81403.8571   117.8  400.65   137.4  396.22   164.8  392.86
     208  388.01  244.78386.1158   263.9  384.69  296.02377.9131   315.7  374.81
   343.6  373.64   363.6  371.27   383.5  373.44  426.42 373.062   443.4  372.83
   466.4  370.68   475.3   370.1   481.4  370.94   488.1373.0147   499.2  374.75
   519.2  374.83   530.7 378.348   622.9  382.58   642.8  386.07   670.7  395.74
#Mann= 9 ,-1 , 0
       0     .12       0   90.81    .016       0  244.78     .12       0
  296.02     .06       0  426.42     .12       0   466.4    .045       0
   481.4     .12       0   488.1    .016       0   530.7     .12       0
Bank Sta=466.4,481.4
XS Rating Curve= 0 ,0
Exp/Cntr=0.3,0.1

Type RM Length L Ch R = 1 ,1433.2  ,68,66.7,66.5
XS GIS Cut Line= 2
     2404483.962      399677.449     2404750.889      399048.109
#Sta/Elev= 30
       0  398.77   81.17398.2369   107.9  396.28   131.6395.1765   143.9  394.36
   159.9  392.55   171.9  390.03   183.9  388.58   207.9  384.89   243.9  378.22
   255.8  376.86  271.83375.7984   323.8  372.74   443.8  372.35   454.4  370.46
   463.7  369.84   467.7  370.35   469.4  370.93   479.7  374.57   483.7  375.19
   515.7  375.45  530.81 377.561   583.7  381.49   595.7  383.68  608.42 387.108
  615.96389.3699   627.6  392.62   639.6  396.72  650.96 400.058   683.6  409.93
#Mann= 10 ,-1 , 0
       0     .12       0   81.17     .08       0   131.6     .12       0
  271.83    .016       0   454.4    .045       0   469.4    .016       0
  530.81     .06       0  608.42     .12       0  615.96     .06       0
  650.96     .12       0
Bank Sta=454.4,469.4
XS Rating Curve= 0 ,0
Exp/Cntr=0.3,0.1

Type RM Length L Ch R = 1 ,1366.5  ,230.9,241.7,247.5
XS GIS Cut Line= 2
     2404540.386      399712.172     2404800.803      399093.682
#Sta/Elev= 30
       0  395.51   92.61396.8158  110.23396.3332   131.8  395.49   171.8   391.9
   239.7  379.38   275.6  375.17   295.6  374.04   311.6  371.27   319.6  371.42
   331.5  373.28   359.5  371.58   407.4  371.74   415.4  371.08   427.4  367.52
   431.4  367.12   455.4  367.34   463.4   366.7  468.54  367.28   479.3  372.67
   499.3  374.07  513.58377.0953  536.92377.0308   539.3  377.12  549.27380.0815
   563.2  381.19   599.2  387.56   636.9 400.582   647.1  403.98   671.1   409.1
#Mann= 9 ,-1 , 0
       0     .12       0   92.61     .08       0  110.23     .12       0
   455.4    .045       0  468.54     .12       0  513.58    .016       0
  536.92     .12       0  549.27     .06       0   636.9     .12       0
Bank Sta=455.4,468.54
XS Rating Curve= 0 ,0
Exp/Cntr=0.3,0.1

Type RM Length L Ch R = 1 ,1124.8  ,212.6,213.4,214.2
XS GIS Cut Line= 3
     2404629.362      399634.047     2404716.167      399608.005
     2404996.115      399260.783
#Sta/Elev= 30
       0  393.97    19.7  392.72   37.67390.7486    78.8  386.04  125.33379.5418
   150.4  376.14   178.2  373.94   190.2  371.52   198.2  370.68   206.1  370.87
  217.26372.4095   245.9  371.15  269.98371.0764   293.7  371.02   333.6  369.77
   337.5  369.46   345.5  365.99   349.5  365.32   353.5  365.04   371.6  365.58
   377.4  366.18   393.3  374.51   401.2  377.08   417.2  377.98   433.1  380.44
  455.52 381.536   476.9  383.28  488.91383.3301   512.8  383.81   536.6  385.11
#Mann= 9 ,-1 , 0
       0     .12       0   37.67     .06       0  125.33     .12       0
  217.26     .06       0  269.98     .12       0   349.5    .045       0
   371.6     .12       0  455.52     .06       0  488.91     .12       0
Bank Sta=349.5,371.6
XS Rating Curve= 0 ,0
Exp/Cntr=0.3,0.1

Type RM Length L Ch R = 1 ,911.3   ,334,304.6,274.4
XS GIS Cut Line= 2
     2404785.612      399833.699     2405128.494      399421.373
#Sta/Elev= 30
       0  382.84    35.8  380.35   83.52377.8549     147  374.08   158.9  371.56
  184.36 370.476  214.97369.7929   266.2  369.96   278.1  369.71   313.8  370.49
   317.8  370.22   321.8  368.67   325.7  365.79   327.2  365.01   329.7  363.72
   333.7  363.29   337.6  363.34   342.2  364.71   353.5   372.2   357.5   374.4
   361.5  375.92   365.5  376.45   381.3  376.93   385.3  377.77   393.3  380.91
   397.2  381.71  426.92 381.662  451.55 381.236   504.5  380.07   536.3  380.13
#Mann= 8 ,-1 , 0
       0     .06       0   83.52     .12       0  184.36     .06       0
  214.97     .12       0   327.2    .045       0   342.2     .12       0
  426.92     .06       0  451.55     .12       0
Bank Sta=327.2,342.2
XS Rating Curve= 0 ,0
Exp/Cntr=0.3,0.1