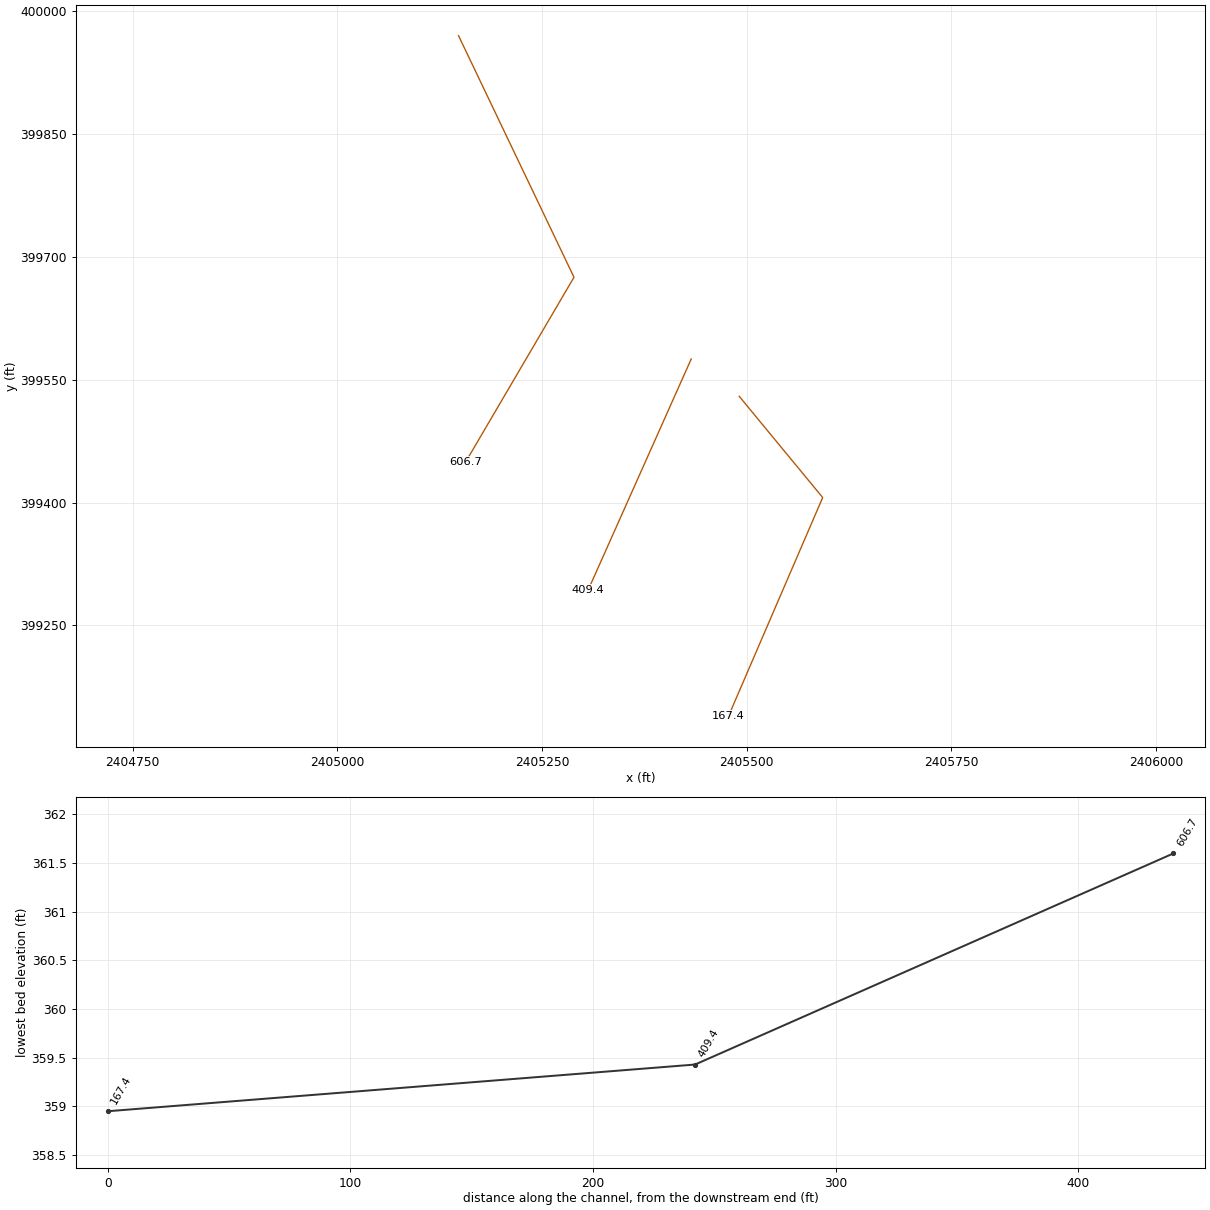
HEC-RAS study HARLANRUN.prj: HARLANRUN

--- HARLANRUN.g01 (geometry) --- (continued)

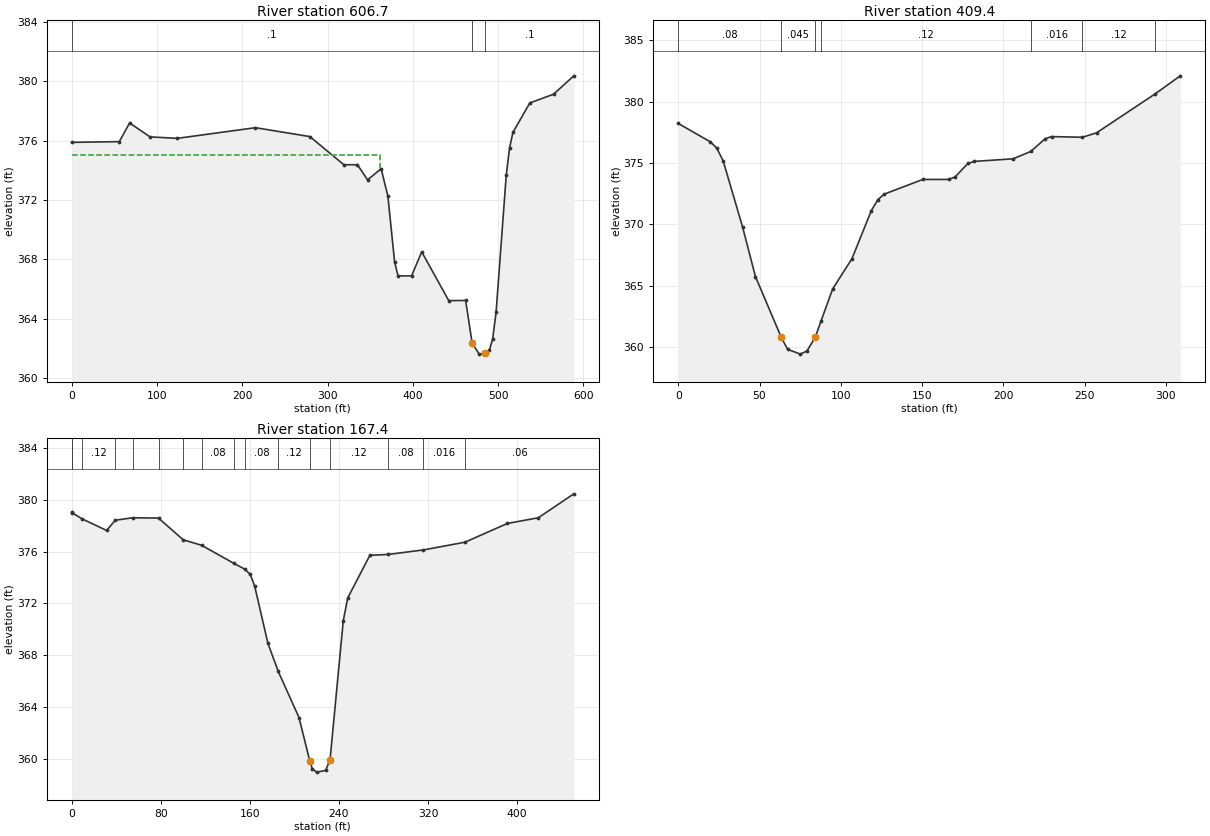
Type RM Length L Ch R = 1 ,606.7   ,194.7,197.2,199.7
XS GIS Cut Line= 3
     2405148.025      399970.418     2405289.084      399675.279
     2405156.705      399449.585
#Sta/Elev= 30
       0  375.89    55.8  375.94    67.8   377.2    91.8  376.26   123.7  376.16
   215.4  376.88   279.2  376.28   319.1  374.38     335  374.38   346.9  373.36
   362.8  374.11   370.7  372.27   378.6  367.82   382.6  366.88   398.5  366.88
   410.4   368.5   442.1  365.21   461.9  365.22   469.5  362.35   477.8   361.6
   484.5  361.66   489.7  361.86   493.6  362.63   497.6  364.41   509.5  373.66
   513.4  375.51   517.4  376.57   537.2  378.55     565  379.14   588.8  380.38
#Mann= 3 , 0 , 0
       0      .1       0   469.5    .045       0   484.5      .1       0
#XS Ineff= 2 , 0
          361.23  375.02
Permanent Ineff=
       F       F
Bank Sta=469.5,484.5
XS Rating Curve= 0 ,0
Exp/Cntr=0.3,0.1

Type RM Length L Ch R = 1 ,409.4   ,241.7,242.1,242.3
XS GIS Cut Line= 2
     2405432.313      399575.453     2405306.445      399293.335
#Sta/Elev= 30
       0  378.22    19.8  376.72    23.8   376.2    27.7  375.15    39.6  369.78
    47.5  365.75    63.4  360.79    67.3  359.82    75.2  359.43    79.2  359.69
    84.3  360.81   87.86362.1226      95  364.74   106.9  367.21   118.8  371.12
   122.8  372.01   126.7  372.46   150.5  373.66   166.3  373.66   170.3  373.86
   178.2  374.96   182.2  375.13     206  375.34  216.86 375.938   225.8  376.98
   229.7  377.15  248.72 377.096   257.4  377.46  293.08380.5984   308.9   382.1
#Mann= 7 ,-1 , 0
       0     .08       0    63.4    .045       0    84.3     .08       0
   87.86     .12       0  216.86    .016       0  248.72     .12       0
  293.08     .06       0
Bank Sta=63.4,84.3
XS Rating Curve= 0 ,0
Exp/Cntr=0.3,0.1

Type RM Length L Ch R = 1 ,167.4   ,162.1,167.4,172.6
XS GIS Cut Line= 3
     2405490.907       399529.88     2405592.903      399406.182
     2405477.886      399139.255
#Sta/Elev= 30
       0  379.02     .33379.0014    9.17378.5303    31.3  377.63   39.12378.4209
   54.65378.6092   77.91378.5859  100.12 376.907   116.7376.4792   145.6375.0862
  155.49374.6333   160.3  374.23   164.3  373.33   176.2   368.9  185.46 366.736
   204.1  363.17   213.9  359.78   216.1   359.2     220  358.95     228  359.08
     232   359.9   243.9  370.66   247.9  372.42   267.8  375.71  283.99375.7724
   315.9376.1245  353.21376.7215   391.3  378.17   419.1  378.61     451  380.46
#Mann= 16 ,-1 , 0
       0     .12       0     .33     .08       0    9.17     .12       0
   39.12     .08       0   54.65     .12       0   77.91     .08       0
  100.12     .12       0   116.7     .08       0   145.6     .12       0
  155.49     .08       0  185.46     .12       0   213.9    .045       0
     232     .12       0  283.99     .08       0   315.9    .016       0
  353.21     .06       0
Bank Sta=213.9,232
XS Rating Curve= 0 ,0
Exp/Cntr=0.3,0.1

Chan Stop Cuts=-1
Use User Specified Reach Order=0
Composite Channel Slope=5